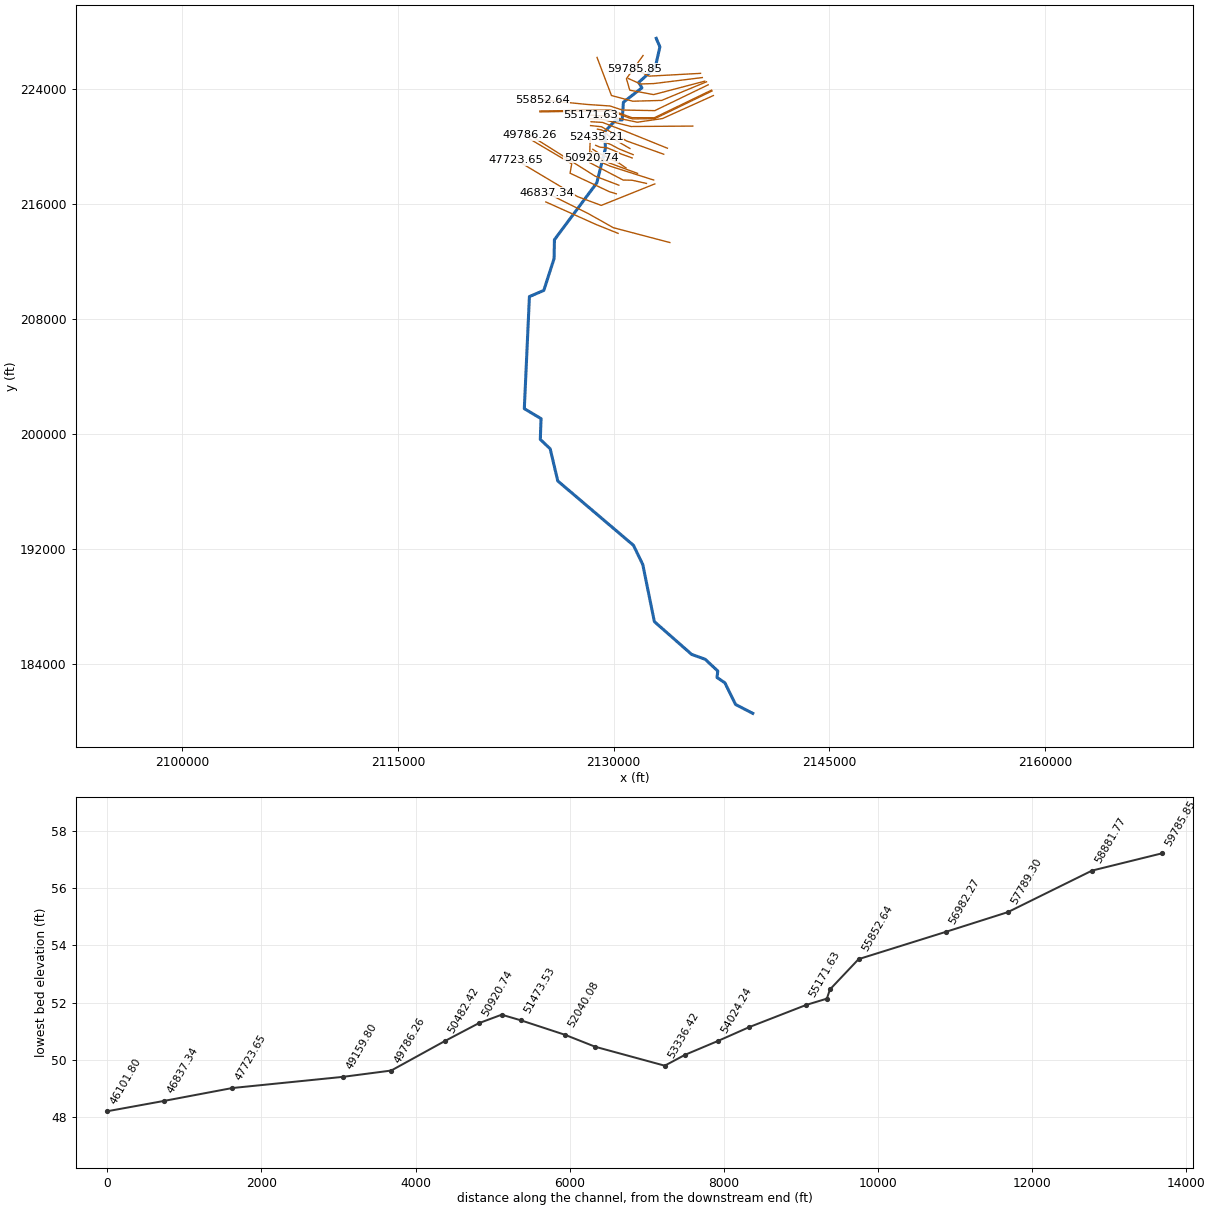
--- bogue.prj (project) ---

Proj Title=NCFM-Bogue Swamp - Detailed Study
Current Plan=p01
Default Exp/Contr=.3,.1
English Units
Geom File=g01
Flow File=f01
Plan File=p01
Y Axis Title=Elevation
X Axis Title(PF)=Main Channel Distance
X Axis Title(XS)=Station
BEGIN DESCRIPTION:
ogue Swamp - Detialed Study
END DESCRIPTION:

--- bogue.p01 (plan) ---

Plan Title=BOGUE SWAMP DETAILED STUDY
Version=September 1998 Version 2.2
Short Identifier=BOGUE
Geom File=g01
Flow File=f01
Interactive Comp Mode
Subcritical Flow
K Sum by GR= 0
Std Step Tol= 0.01
Critical Tol= 0.01
Num of Std Step Trials= 20
Max Error Tol= 0.3
Flow Tol Ratio= 0.001
Log Output Level= 0
Friction Slope Method= 1
Parabolic Critical Depth
Global Vel Dist= 0 , 0 , 0
Global Log Level= 0
Encroach Param=-1 ,0,0, 2
Encroach River=Bogue Swamp
Encroach Reach=Bogue
Encroach Node=59785.85
       1 3565.48 3705.24
Encroach Node=58881.77
       1 4320.42  4512.6
Encroach Node=57789.30
       1 4971.33 5118.01
Encroach Node=56982.27
       1 5687.64 5875.99
Encroach Node=55852.64
       1 6366.04 6513.84
Encroach Node=55479.94
       1    6620    6810
Encroach Node=55460
       1    6620    6810
Encroach Node=55440.40
       1    6620    6810
Encroach Node=55171.63
       1 6652.62 6866.13
Encroach Node=54436.00
       1    5295  5464.6
Encroach Node=54024.24
       1    4080 4251.28
Encroach Node=53600.32
       1    4110    4350
Encroach Node=53336.42
       1 1881.05 2134.71
Encroach Node=52435.21
       1 2068.67 2280.21
Encroach Node=52040.08
       1  1977.6 2205.46
Encroach Node=51473.53
       1 1799.28 2000.15
Encroach Node=51219.90
       1 2730.26 2920.71
Encroach Node=50920.74
       1 3928.82  4165.5
Encroach Node=50482.42
       1 3484.33 3827.59
Encroach Node=49786.26
       1 1515.42 1781.79
Encroach Node=49159.80
       1 1506.06 1861.69
Encroach Node=47723.65
       1 5003.36 5523.47
Encroach Node=46837.34
       1 6561.82 7593.99
Encroach Node=46101.80
       1 3280.53 4177.57
Encroach Node=45277.63
       1 2748.88 3661.83
Encroach Node=44694.61
       1 2858.28 3712.25
Encroach Node=43818.17
       1  2895.7 3829.39
Encroach Node=43206.24
       1 3141.66 3966.11
Encroach Node=42733.79
       1 3024.45 3731.45
Encroach Node=42315.44
       1  2949.5  2988.5
Encroach Node=42160
       1  2949.5  2988.5
Encroach Node=42005.40
       1  2949.5  2988.5
Encroach Node=41721.81
       1 2951.69 3384.89
Encroach Node=41321.74
       1 2968.79 3546.97
Encroach Node=40591.90
       1 2953.69 3685.23
Encroach Node=40258.85
       1 3060.83 3802.24
Encroach Node=40206.33
       1  3181.4 3824.53
Encroach Node=40184
       4      .7
Encroach Node=40161.92
       1  3181.4 3824.53
Encroach Node=40125.57
       1 3175.86  3857.7
Encroach Node=39588.22
       4      .9
Encroach Node=39075.48
       4      .9
Encroach Node=38109.30
       4      .9
Encroach Node=37497.73
       1 4339.03 4937.73
Encroach Node=37211.47
       1    4586    4650
Encroach Node=37144
       1    4586    4650
Encroach Node=37076.90
       1    4586    4650
Encroach Node=36770.22
       1 4606.29 4973.07
Encroach Node=36333.70
       1 4654.04 5428.71
Encroach Node=35906.50
       1 4457.35 5163.68
Encroach Node=35271.50
       1 4320.25  4998.9
Encroach Node=34852.32
       1 4596.36 5115.67
Encroach Node=34316.72
       1    2760    2860
Encroach Node=34256
       1    2760    2860
Encroach Node=34195.50
       1    2760    2860
Encroach Node=33836.40
       1  2833.1 3342.92
Encroach Node=33562.88
       1 2521.72 3204.74
Encroach Node=33139.04
       1 2882.23 3586.08
Encroach Node=32839.21
       1 3011.18 3641.98
Encroach Node=32269.70
       1 2786.51 3343.11
Encroach Node=31633.88
       1 2751.21 3468.74
Encroach Node=31093.04
       1 2700.11 3548.61
Encroach Node=30612.16
       1 2953.15 3719.07
Encroach Node=29533.27
       1    2766 3759.12
Encroach Node=29014.22
       1 2699.96 3744.45
Encroach Node=28570.84
       1 2710.54 3668.64
Encroach Node=27693.46
       1 2677.34 3502.89
Encroach Node=26773.30
       1 2453.15 3484.53
Encroach Node=26102.94
       1 2891.28 4090.82
Encroach Node=25330.65
       1 3036.68 4371.66
Encroach Node=24855.06
       1 2800.86  4282.8
Encroach Node=23996.60
       1 4164.43 5540.15
Encroach Node=23247.32
       1 4185.58 5686.42
Encroach Node=21959.80
       1 5175.33 6425.39
Encroach Node=21297.87
       1 5320.52 6651.12
Encroach Node=20130.08
       1 6857.34 8553.74
Encroach Node=19036.77
       1 6895.96 8645.58
Encroach Node=18342.15
       1 7250.18 9215.83
Encroach Node=17619.70
       1    824510216.42
Encroach Node=16354.30
       1    8305 10383.9
Encroach Node=15733.83
       1    847010398.05
Encroach Node=14881.69
       1 9867.52   11770
Encroach Node=13690.40
       1 4804.18 6843.89
Encroach Node=12360.89
       1 5184.02  8123.9
Encroach Node=11053.41
       1   1099514075.91
Encroach Node=10428.73
       1    6125 9205.51
Encroach Node=9320.684
       1    5360    8450
Encroach Node=8453.612
       1    4760    8280

--- bogue.f01 (steady flow) ---

Flow Title=Bogue Swamp Flow data
Version=Version 3.0.1  Mar 2001
Number of Profiles= 5
Profile Names=100 YR,FW,500 YR,10 YR,50 YR
River Rch & RM=Bogue Swamp,Bogue           ,59785.85
     900     900    1500     400     700
River Rch & RM=Bogue Swamp,Bogue           ,58881.77
     960     960    1540     410     770
River Rch & RM=Bogue Swamp,Bogue           ,56982.27
    1120    1120    1780     490     890
River Rch & RM=Bogue Swamp,Bogue           ,50920.74
    1180    1180    1870     510     940
River Rch & RM=Bogue Swamp,Bogue           ,50482.42
    1440    1440    2260     640    1160
River Rch & RM=Bogue Swamp,Bogue           ,45277.63
    1600    1600    2500     720    1290
River Rch & RM=Bogue Swamp,Bogue           ,43818.17
    1930    1930    2990     880    1560
River Rch & RM=Bogue Swamp,Bogue           ,38109.30
    1990    1990    3080     910    1610
River Rch & RM=Bogue Swamp,Bogue           ,37497.73
    2330    2330    3570    1080    1890
River Rch & RM=Bogue Swamp,Bogue           ,30612.16
    2460    2460    3740    1150    2000
River Rch & RM=Bogue Swamp,Bogue           ,29533.27
    2820    2820    4290    1330    2300
River Rch & RM=Bogue Swamp,Bogue           ,26102.94
    2840    2840    4310    1340    2310
River Rch & RM=Bogue Swamp,Bogue           ,25330.65
    3090    3090    4670    1460    2520
River Rch & RM=Bogue Swamp,Bogue           ,8453.612
    3710    3710    5560    1790    3040
Boundary for River Rch & Prof#=Bogue Swamp,Bogue           , 1
Up Type= 0
Dn Type= 3
Dn Slope=.0021
Boundary for River Rch & Prof#=Bogue Swamp,Bogue           , 2
Up Type= 0
Dn Type= 3
Dn Slope=.0021
Boundary for River Rch & Prof#=Bogue Swamp,Bogue           , 3
Up Type= 0
Dn Type= 3
Dn Slope=.0021
Boundary for River Rch & Prof#=Bogue Swamp,Bogue           , 4
Up Type= 0
Dn Type= 3
Dn Slope=.0021
Boundary for River Rch & Prof#=Bogue Swamp,Bogue           , 5
Up Type= 0
Dn Type= 3
Dn Slope=.0021
DSS Import GetInterval= 0
DSS Import GetPeak= 0
DSS Import FillOption= 0

--- bogue.g01 (geometry) ---

Geom Title=Bogue Swamp Geometric Data
Version=Version 3.0.1  Mar 2001

River Reach=Bogue Swamp     ,Bogue
Reach XY= 30
     2132955.385      227489.847       2133209.5      226892.094
      2132885.25      225455.219       2131736.5      224426.547
       2131959.5       224049.25       2130672.5      223046.297
      2130587.75      221816.516        2130156.      221829.813
      2129375.75      221000.594      2129423.75       219834.25
     2128821.973      217437.804      2125876.25      213484.641
        2125852.      212172.516       2125136.5      209959.297
        2124136.      209529.031        2123781.      201736.359
       2124944.5      201042.531      2124893.25      199598.125
      2125580.25      198944.344       2126108.5      196707.516
       2131373.5      192230.922     2132021.016      190892.051
     2132825.628      186926.068     2135416.773      184647.422
     2136360.784      184307.579     2137235.784       183489.87
       2137183.5      183040.094      2137731.25      182668.969
        2138472.      181164.594       2139670.5      180545.594

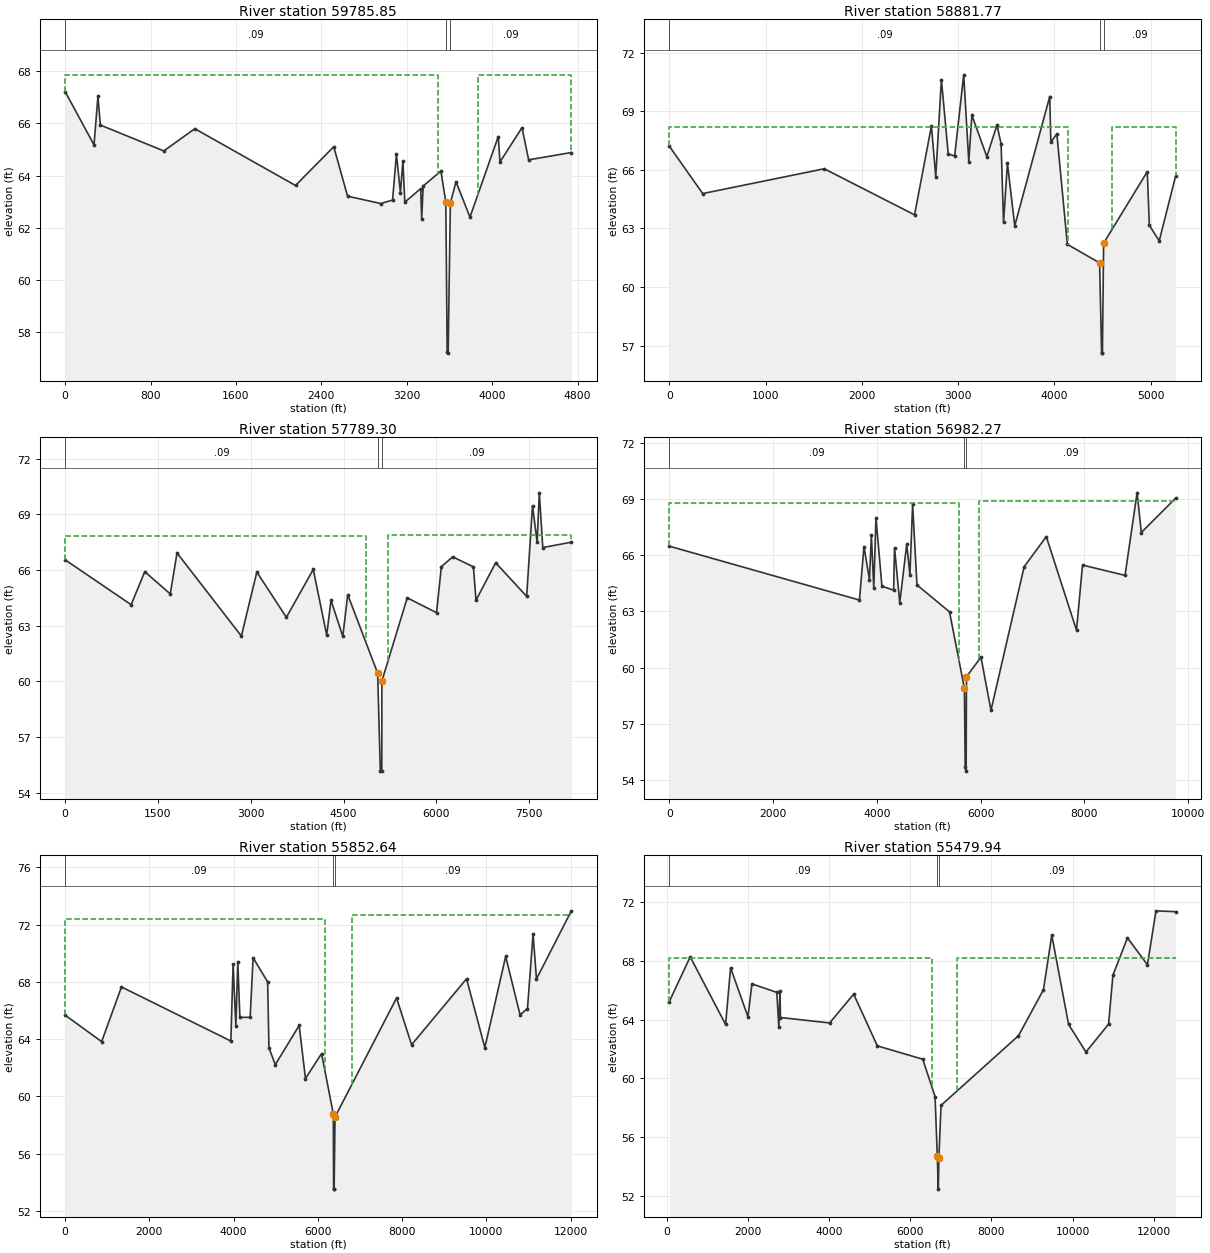
Type RM Length L Ch R = 1 ,59785.85,814.4,904.08,843.6
XS GIS Cut Line= 3
     2136036.397      225054.783     2132453.553      224859.609
     2131429.124      225388.543
#Sta/Elev= 30
       0   67.21  270.85   65.17  307.45   67.03  330.11   65.93  924.39   64.94
 1214.71   65.79 2157.71   63.62  2515.8    65.1 2645.53   63.21 2955.31   62.93
 3066.58   63.06 3102.96   64.81 3140.28   63.35 3163.64   64.56 3181.56   62.98
 3330.07    63.5 3339.36   62.35 3353.67    63.6 3519.56   64.17 3565.48   62.99
 3578.09   57.26 3587.36   57.21 3607.96   62.95 3660.96   63.76 3791.68   62.41
 4056.57   65.49 4072.72   64.52 4279.08   65.83  4341.1    64.6 4741.08   64.88
#Mann= 3 , 0 , 0
       0     .09       0 3565.48     .06       0 3607.96     .09       0
#XS Ineff= 2 , 0
         3488.91   67.83 3862.31           67.85
Permanent Ineff=
       F       F
Bank Sta=3565.48,3607.96
XS Rating Curve= 0
Exp/Cntr=.3,.1

Type RM Length L Ch R = 1 ,58881.77,808.93,1092.47,670.8
XS GIS Cut Line= 4
     2136161.866      224762.022     2132788.137      224343.791
     2131854.089      224315.909     2131011.229      224698.006
#Sta/Elev= 30
       0   67.21  347.31   64.78  1610.1   66.05 2548.22   63.69 2723.38   68.24
 2768.42   65.65    2827   70.62 2897.99   66.82 2964.67    66.7  3058.8   70.86
 3111.65   66.42 3143.66    68.8 3298.89   66.67  3404.5   68.29    3447   67.33
 3472.57   63.31  3513.1   66.33 3589.05   63.13 3952.73   69.75 3963.99   67.42
  4026.7   67.83 4135.72   62.18 4470.53   61.23 4491.47   56.61 4499.87   56.61
  4512.6   62.24 4965.86    65.9 4987.73   63.15  5090.4   62.36 5259.44   65.66
#Mann= 3 , 0 , 0
       0     .09       0 4470.53     .06       0  4512.6     .09       0
#XS Ineff= 2 , 0
         4144.69   68.21 4599.77           68.21
Permanent Ineff=
       F       F
Bank Sta=4470.53,4512.6
XS Rating Curve= 0
Exp/Cntr=.3,.1

Type RM Length L Ch R = 1 ,57789.30,792.77,807.03,754.79
XS GIS Cut Line= 5
     2136329.159      224511.083     2132774.196      223577.034
     2131115.214      223883.737     2130882.086      224684.994
     2132039.067      226294.915
#Sta/Elev= 30
       0   66.55 1067.24   64.13 1287.16   65.91 1699.09   64.71 1808.27   66.92
    2848   62.44 3097.92   65.89  3575.3   63.45 4009.75   66.03 4226.88   62.49
 4296.11   64.37 4487.11   62.42 4566.61   64.67 5050.03   60.44 5093.21   55.18
 5117.23   55.16 5118.01   60.01 5528.22    64.5 6001.66    63.7 6079.34   66.18
 6262.89   66.71 6597.27   66.17 6639.23   64.37 6956.88   66.39 7457.78   64.58
 7552.11   69.47 7626.83    67.5 7662.09   70.16 7718.29   67.21 8179.75    67.5
#Mann= 3 , 0 , 0
       0     .09       0 5050.03     .06       0 5118.01     .09       0
#XS Ineff= 2 , 0
         4854.14   67.83 5215.87            67.9
Permanent Ineff=
       F       F
Bank Sta=5050.03,5118.01
XS Rating Curve= 0
Exp/Cntr=.3,.1

Type RM Length L Ch R = 1 ,56982.27,867.09,1129.62,923.28
XS GIS Cut Line= 5
     2136454.628       224469.26     2133331.838      223172.745
     2131324.329       223116.98     2129841.635      223512.612
     2128838.329      226160.642
#Sta/Elev= 30
       0   66.49 3664.75   63.61 3751.77   66.47 3857.73    64.7 3894.56   67.08
 3940.89   64.25    3983      68 4098.17   64.35 4323.26   64.14 4340.88    66.4
 4441.27   63.46 4576.27    66.6 4637.27   64.96 4689.35   68.74 4772.85   64.42
 5400.36   62.98 5687.64   58.89 5702.18   54.69 5720.75   54.47 5726.66   59.51
 6006.66   60.56 6199.34   57.72 6838.72   65.39 7265.37      67 7847.75      62
 7963.71   65.48 8782.83   64.93 9015.27   69.34 9096.82   67.22 9755.81   69.05
#Mann= 3 , 0 , 0
       0     .09       0 5687.64     .06       0 5726.66     .09       0
#XS Ineff= 2 , 0
         5589.26   68.78 5974.33            68.9
Permanent Ineff=
       F       F
Bank Sta=5687.64,5726.66
XS Rating Curve= 0
Exp/Cntr=.3,.1

Type RM Length L Ch R = 1 ,55852.64,347.95,372.71,433.56
XS GIS Cut Line= 6
     2136569.172      224257.714     2132854.733      222461.563
     2130587.991      222504.671     2129747.393       222784.87
     2128152.412      222892.639     2125030.702      223201.577
#Sta/Elev= 30
       0   65.68  867.21   63.83 1338.24   67.65 3934.34   63.87 3986.85   69.23
 4052.75   64.93 4099.18   69.42 4148.32   65.52 4392.34   65.53    4462   69.69
 4807.49      68 4837.81    63.4 4988.77   62.22  5555.5   64.96 5704.68   61.25
 6087.09   62.99 6366.15   58.77 6372.84   53.53 6385.34   53.52 6406.23   58.56
 7867.06   66.88 8223.45   63.61 9527.81   68.22 9962.24   63.4110456.31   69.78
10798.52    65.710974.12   66.1411106.66   71.3511187.85   68.2112015.41   72.97
#Mann= 3 , 0 , 0
       0     .09       0 6366.15     .06       0 6406.23     .09       0
#XS Ineff= 2 , 0
         6175.03   72.38 6803.15           72.66
Permanent Ineff=
       F       F
Bank Sta=6366.15,6406.23
XS Rating Curve= 0
Exp/Cntr=.5,.3

Type RM Length L Ch R = 1 ,55479.94,42.96,39.54,38.09
XS GIS Cut Line= 6
        2136808.      223890.919     2132820.121      221966.291
     2131264.622      221972.739     2129896.106      222472.433
     2129744.585      222504.671     2124863.704      222436.971
#Sta/Elev= 30
      57   65.22  572.73   68.27 1445.09   63.67 1568.09   67.52 1996.65   64.19
 2094.38   66.43 2707.51   65.85 2758.03   63.47 2785.97   65.94 2797.67   64.14
 4009.93   63.77 4602.93   65.73 5186.24   62.21 6305.59    61.3 6609.39   58.76
    6664    54.7    6689   52.46    6703   54.56    6756   58.16 8665.94    62.9
 9281.04   66.03  9486.3   69.74 9901.14   63.6710328.93   61.7910886.25   63.69
 10993.7   67.0211352.08   69.56 11844.3   67.7312055.41    71.412536.94   71.34
#Mann= 3 , 0 , 0
      57     .09       0    6664     .06       0    6703     .09       0
#XS Ineff= 2 , 0
      57 6526.08   68.17    7157      57   68.22
Permanent Ineff=
       F       F
Bank Sta=6664,6703
XS Rating Curve= 0
Exp/Cntr=.5,.3

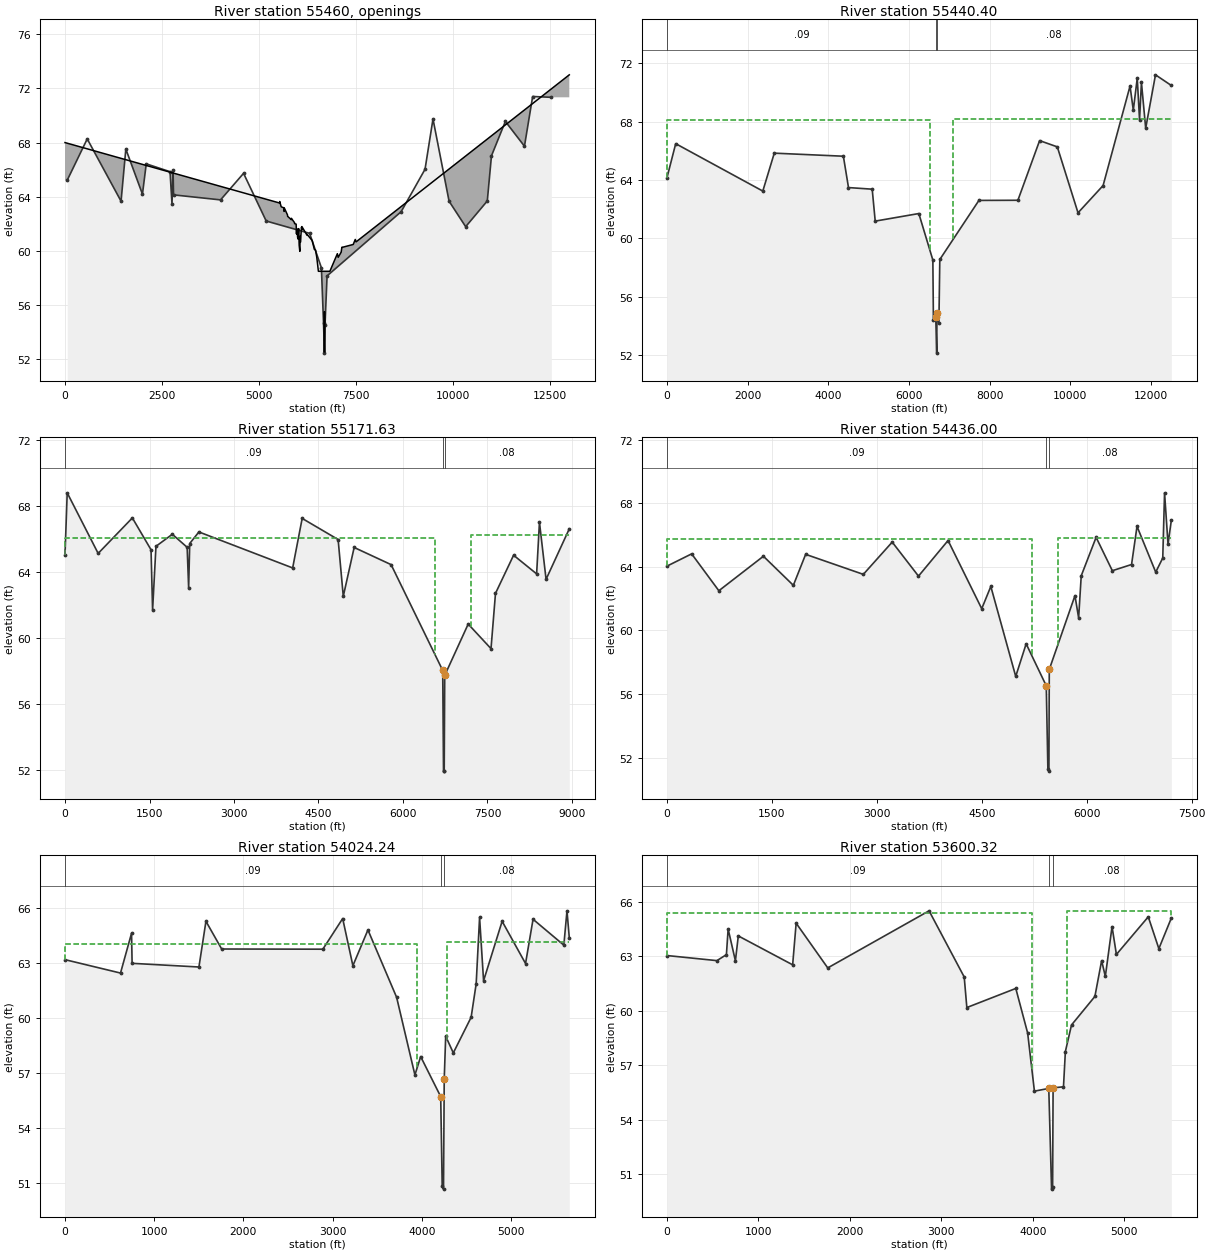
Type RM Length L Ch R = 4 ,55460   ,,,
BEGIN DESCRIPTION:
Unknown Road 2-36" CMPs - Structure #73
END DESCRIPTION:
Bridge Culvert--1,0,-1,-1, 0
Deck Dist Width WeirC Skew NumUp NumDn MinLoCord MaxHiCord MaxSubmerge Is_Ogee
10,20,2.6,0, 52, 52, 58.5, , .95, 0, 0,0,,
       0 5531.88 5535.34 5573.39 5644.89  5648.8 5657.38 5735.77 5738.12 5832.43
 5835.29 5916.69 5918.14 5958.69 5967.32 5975.27    5977 5990.77 5992.42 5995.07
 6007.61 6023.24 6024.02 6036.42 6053.21 6061.99 6065.07 6068.42  6096.8 6105.51
 6106.81 6236.93 6239.05 6372.79 6427.12  6459.5 6489.78 6532.32 6736.64 6736.64
 6741.36 6741.36  6827.7 7021.27 7042.13 7120.01 7136.61 7136.85 7430.02 7482.14
    7503   13000
      68   63.54   63.65   63.26   63.18   62.92   63.15   62.66   62.56   62.31
   62.41   62.09   62.02   61.98   61.26   61.64   61.65   61.22   61.24   61.03
   60.88   61.65   61.64   60.43   59.97   61.09   61.04   60.64   61.76   61.59
    61.8   61.17   61.23   60.77   60.12   60.06   59.54    58.5    58.5    58.5
    58.5    58.5    58.5    59.8   59.53   59.92   60.27   60.26   60.48   60.85
   60.67      73
                                                                                
                                                                                
                                                                                
                                                                                
                                                                                
                
       0 5531.88 5535.34 5573.39 5644.89  5648.8 5657.38 5735.77 5738.12 5832.43
 5835.29 5916.69 5918.14 5958.69 5967.32 5975.27    5977 5990.77 5992.42 5995.07
 6007.61 6023.24 6024.02 6036.42 6053.21 6061.99 6065.07 6068.42  6096.8 6105.51
 6106.81 6236.93 6239.05 6372.79 6427.12  6459.5 6489.78 6532.32 6736.64 6736.64
 6741.36 6741.36  6827.7 7021.27 7042.13 7120.01 7136.61 7136.85 7430.02 7482.14
    7503   13000
      68   63.54   63.65   63.26   63.18   62.92   63.15   62.66   62.56   62.31
   62.41   62.09   62.02   61.98   61.26   61.64   61.65   61.22   61.24   61.03
   60.88   61.65   61.64   60.43   59.97   61.09   61.04   60.64   61.76   61.59
    61.8   61.17   61.23   60.77   60.12   60.06   59.54    58.5    58.5    58.5
    58.5    58.5    58.5    59.8   59.53   59.92   60.27   60.26   60.48   60.85
   60.67      73
                                                                                
                                                                                
                                                                                
                                                                                
                                                                                
                
BR Coef=-1 , 1 , 0 ,, 0 ,,,.8,-1,1.2,0,
WSPro=,,,, 1 ,,,, 0 ,,,, 0 ,,,,-1 ,-1 ,-1 , 0 , 0 , 0 , 0 , 0
Multiple Barrel Culv=1,3,,20,.024,.9,1,2,3,52.53,52.51, 2,Culvert #1  , 0 ,10
    6687    6687    6691    6691
Culvert Bottom n=.024
BC Mult= 1 ,0,6680,0,6680
BC Mult= 2 ,6680,6700,6680,6700
BC Mult= 1 ,6700,12650,6700,12650
BR U #Sta/Elev= 30
      57   65.22  572.73   68.27 1445.09   63.67 1568.09   67.52 1996.65   64.19
 2094.38   66.43 2707.51   65.85 2758.03   63.47 2785.97   65.94 2797.67   64.14
 4009.93   63.77 4602.93   65.73 5186.24   62.21 6305.59    61.3 6609.39   58.76
    6664    54.7    6689   52.46    6703   54.56    6756   58.16 8665.94    62.9
 9281.04   66.03  9486.3   69.74 9901.14   63.6710328.93   61.7910886.25   63.69
 10993.7   67.0211352.08   69.56 11844.3   67.7312055.41    71.412536.94   71.34
BR U #Mann= 3
      57     .09    6664     .05    6703     .09
BR D #Sta/Elev= 30
       0   64.18  215.02    66.5 2375.06   63.25 2659.71   65.85 4373.03   65.64
 4500.13   63.49 5088.06   63.38 5162.67   61.19 6244.19   61.71 6592.22   58.52
    6606   54.42    6664   54.62    6688   52.14    6694   54.89    6742   54.19
  6764.6   58.56 7734.46   62.61  8701.2   62.62 9239.81   66.71  9678.7   66.28
10192.13   61.7610814.24   63.6311482.28   70.4511563.21    68.811661.09   70.99
11717.91   68.1411764.61    70.711870.26   67.5612113.36   71.2212505.99   70.49
BR D #Mann= 3
       0     .09    6664     .05    6694     .08
BC Design=,, 0 ,, 0 ,,,,,,

Type RM Length L Ch R = 1 ,55440.40,273.78,268.77,284.31
XS GIS Cut Line= 6
     2136830.567      223826.442     2132858.807      221905.038
     2131319.427      221885.695     2131114.714      221937.277
     2129759.093      222449.866     2124866.928      222375.718
#Sta/Elev= 30
       0   64.18  215.02    66.5 2375.06   63.25 2659.71   65.85 4373.03   65.64
 4500.13   63.49 5088.06   63.38 5162.67   61.19 6244.19   61.71 6592.22   58.52
    6606   54.42    6664   54.62    6688   52.14    6694   54.89    6742   54.19
  6764.6   58.56 7734.46   62.61  8701.2   62.62 9239.81   66.71  9678.7   66.28
10192.13   61.7610814.24   63.6311482.28   70.4511563.21    68.811661.09   70.99
11717.91   68.1411764.61    70.711870.26   67.5612113.36   71.2212505.99   70.49
#Mann= 3 , 0 , 0
       0     .09       0    6664     .06       0    6694     .08       0
#XS Ineff= 2 , 0
       0 6519.69   68.14    7100       0   68.19
Permanent Ineff=
       F       F
Bank Sta=6664,6694
XS Rating Curve= 0
Exp/Cntr=.5,.3

Type RM Length L Ch R = 1 ,55171.63,563.65,735.63,653.25
XS GIS Cut Line= 5
     2136930.213      223510.213     2133387.808        221910.9
     2131639.026      221656.803     2129695.935      222060.368
     2128384.918      222145.869
#Sta/Elev= 30
       0   65.01   39.05   68.78  588.53   65.11 1195.67   67.26 1527.25   65.33
 1554.88   61.68 1614.75   65.54 1905.28   66.27 2168.25   65.48 2194.88   63.01
 2213.93   65.71 2376.89   66.41  4041.4   64.23 4210.24   67.23 4848.46   65.95
 4939.98   62.51 5132.87   65.47 5788.91   64.43  6705.2   58.02 6719.27   51.92
 6731.66   51.94 6741.01   57.72 7157.55   60.83 7562.46   59.34 7642.06   62.69
 7963.31      65 8372.21   63.87 8422.46      67  8539.9   63.54  8952.2    66.6
#Mann= 3 , 0 , 0
       0     .09       0  6705.2     .06       0 6741.01     .08       0
#XS Ineff= 2 , 0
       0 6569.43   66.06    7200       0   66.22
Permanent Ineff=
       F       F
Bank Sta=6705.2,6741.01
XS Rating Curve= 0
Exp/Cntr=.3,.1

Type RM Length L Ch R = 1 ,54436.00,346.35,411.76,348.41
XS GIS Cut Line= 4
     2135495.315       221387.76     2131205.567      221357.866
     2129172.795      221866.059     2128349.336      221897.402
#Sta/Elev= 30
       0   64.05  351.96   64.82  740.85    62.5 1377.86   64.67 1805.75   62.84
 1981.65   64.79 2806.12   63.53 3219.11   65.56 3594.79   63.42 4017.56   65.66
 4498.87   61.37 4628.75   62.77 4984.86   57.11 5133.94   59.16 5421.35   56.52
 5444.48   51.31 5459.34   51.15  5464.6   57.55 5831.78   62.19 5884.23   60.79
 5921.31   63.44 6133.99   65.86 6366.04   63.76 6640.76   64.15  6718.8   66.55
  6986.2   63.67 7086.79   64.56 7112.51   68.66 7162.24   65.43 7209.24   66.93
#Mann= 3 , 0 , 0
       0     .09       0 5421.35     .06       0  5464.6     .08       0
#XS Ineff= 2 , 0
          5218.2   65.73 5582.26           65.84
Permanent Ineff=
       F       F
Bank Sta=5421.35,5464.6
XS Rating Curve= 0
Exp/Cntr=.3,.1

Type RM Length L Ch R = 1 ,54024.24,416.6,423.91,424.68
XS GIS Cut Line= 4
     2133731.586      219848.234     2130846.843      221014.088
     2129217.636      221641.856     2128423.233      221690.826
#Sta/Elev= 30
       0   63.16  622.26   62.43  745.96    64.6  752.24   62.96 1501.39   62.76
 1580.02   65.25 1756.31   63.74 2890.54   63.73 3112.82    65.4 3227.28   62.83
 3395.92   64.78 3717.47   61.11 3922.64   56.88    3987   57.88 4211.71    55.7
 4228.44   50.85 4243.14   50.66 4251.28   56.66  4267.7   58.99 4353.01   58.08
 4552.83   60.02  4609.5   61.85 4647.59   65.46 4692.29   62.01 4900.44   65.25
 5162.83   62.95 5246.94   65.36 5592.12   63.95 5627.38   65.82  5653.3   64.35
#Mann= 3 , 0 , 0
       0     .09       0 4211.71     .06       0 4251.28     .08       0
#XS Ineff= 2 , 0
         3941.66      64 4284.71           64.12
Permanent Ineff=
       F       F
Bank Sta=4211.71,4251.28
XS Rating Curve= 0
Exp/Cntr=.3,.1

Type RM Length L Ch R = 1 ,53600.32,303.14,263.91,183.56
XS GIS Cut Line= 4
     2133477.489      219429.722     2130891.683      220356.427
     2129142.901      221342.919     2128388.064      221421.822
#Sta/Elev= 30
       0   63.03  545.51   62.75   649.3   63.08  668.04   64.49  747.56   62.74
  779.16   64.11  1373.5   62.52 1411.68   64.81 1757.12   62.35  2865.1   65.49
 3249.26   61.85 3277.95   60.17 3813.25   61.22 3942.68   58.77  4016.8   55.57
 4173.82   55.72 4204.28   50.18 4215.75   50.28 4221.04   55.75 4334.59   55.81
 4355.28   57.75 4422.32   59.21 4678.05   60.78 4751.66   62.75  4792.1   61.88
 4865.54   64.62  4913.2   63.09  5261.6   65.16 5377.36   63.41 5513.63   65.09
#Mann= 3 , 0 , 0
       0     .09       0 4173.82     .06       0 4221.04     .08       0
#XS Ineff= 2 , 0
         3990.67   65.39 4375.73           65.48
Permanent Ineff=
       F       F
Bank Sta=4173.82,4221.04
XS Rating Curve= 0
Exp/Cntr=.3,.1

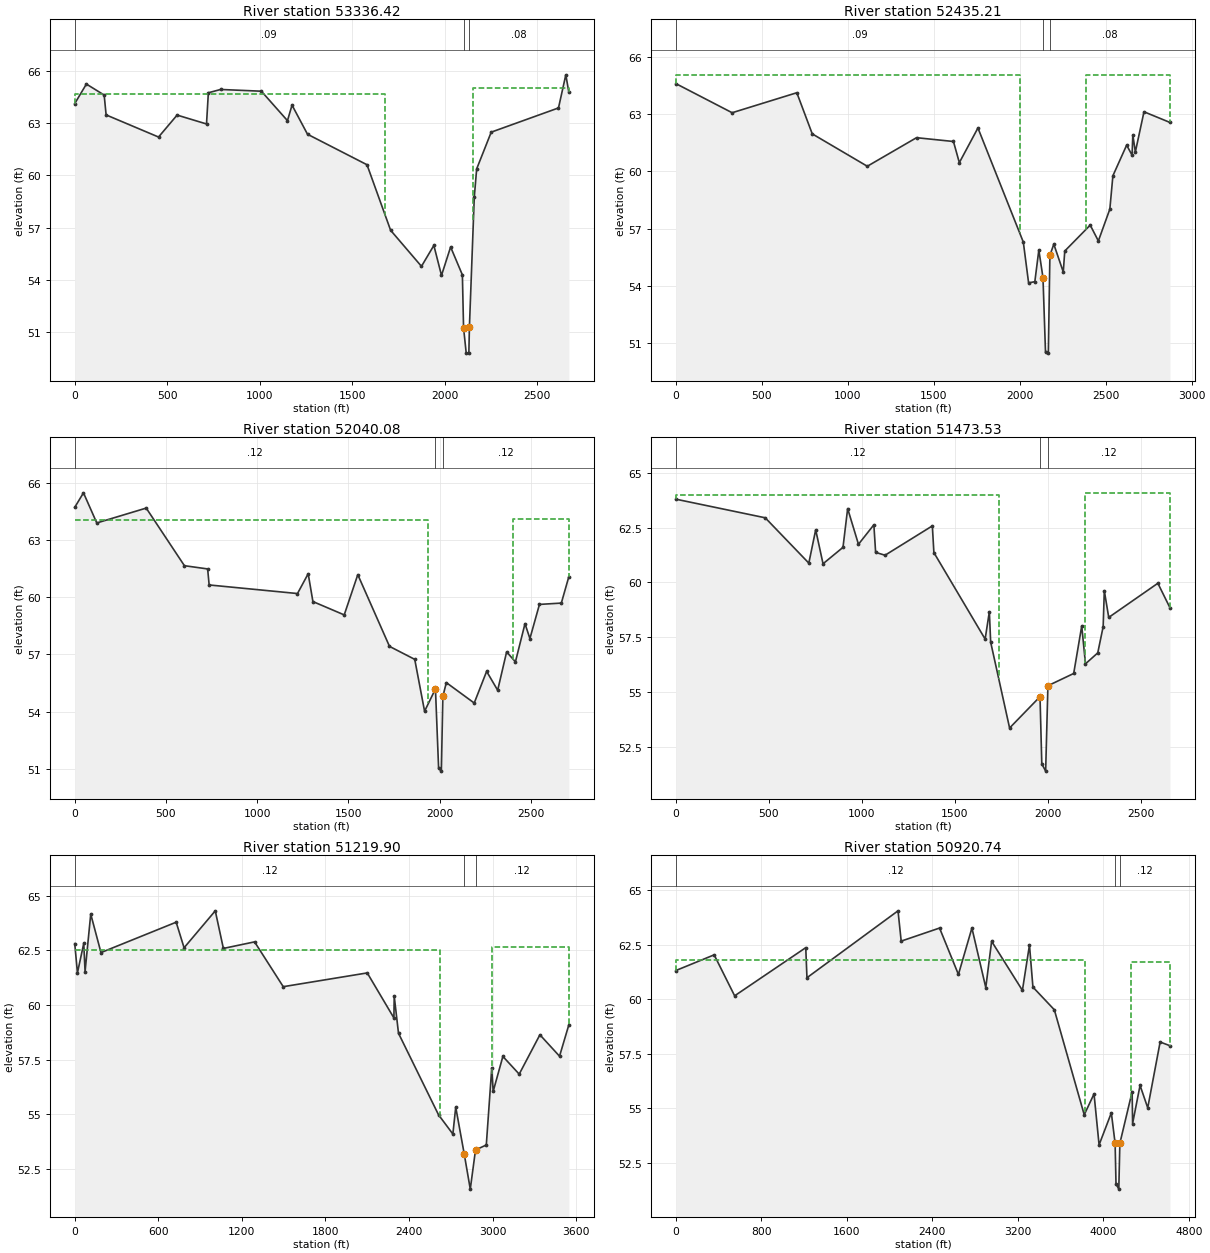
Type RM Length L Ch R = 1 ,53336.42,520.54,901.2,713.88
BEGIN DESCRIPTION:
54290  Survey Cross Section #113
END DESCRIPTION:
XS GIS Cut Line= 6
     2131125.406      219830.527     2130378.359      220261.177
     2129604.945      220735.772     2129394.014      221008.225
     2129139.139      221122.479     2128866.686      221175.212
#Sta/Elev= 30
       0   64.12   62.96   65.24  159.12   64.61  169.66   63.47  453.23    62.2
  553.63   63.46  712.68   62.95  722.65   64.74  788.99   64.93 1009.38   64.83
 1150.57   63.14 1175.26   64.03 1258.98   62.36 1580.71   60.61 1708.45   56.85
 1875.31   54.78  1942.3   55.98 1983.65   54.26 2032.97   55.89 2096.62   54.29
 2102.99   51.26  2117.3    49.8  2131.6    49.8 2134.71   51.32 2160.91   58.74
 2173.85   60.37 2252.55   62.48 2616.48   63.87 2656.08   65.77  2672.6   64.76
#Mann= 3 , 0 , 0
       0     .09       0 2102.99     .06       0 2134.71     .08       0
#XS Ineff= 2 , 0
         1680.28   64.67 2156.36           64.99
Permanent Ineff=
       F       F
Bank Sta=2102.99,2134.71
XS Rating Curve= 0
Exp/Cntr=.3,.1

Type RM Length L Ch R = 1 ,52435.21,346.61,395.13,427.2
XS GIS Cut Line= 6
     2131353.915      219399.876     2130378.359      219795.371
     2129798.298      220102.979     2129402.803      220261.177
     2129077.617      220375.432      2128770.01      220621.518
#Sta/Elev= 30
       0   64.61  327.45   63.08  703.61   64.13  793.36   61.97 1113.54   60.27
 1399.76   61.77 1614.58   61.57 1648.79   60.46 1756.95   62.28 2020.87   56.29
 2051.59   54.15 2087.85   54.21 2111.13   55.87 2135.25   54.43 2149.95    50.5
 2166.39   50.46 2175.48   55.59 2198.23   56.18  2253.3   54.72 2261.95   55.82
 2409.94   57.18 2457.37   56.35 2524.16   58.02 2541.85   59.77 2621.91   61.38
 2653.41   60.85 2657.76   61.92  2672.5   61.02 2722.72   63.13 2873.82   62.57
#Mann= 3 , 0 , 0
       0     .09       0 2135.25     .06       0 2175.48     .08       0
#XS Ineff= 2 , 0
         1998.83   65.05  2383.9           65.07
Permanent Ineff=
       F       F
Bank Sta=2135.25,2175.48
XS Rating Curve= 0
Exp/Cntr=.3,.1

Type RM Length L Ch R = 1 ,52040.08,571.61,566.55,452.77
XS GIS Cut Line= 6
     2131283.604      219171.367     2130501.402      219452.609
     2129938.919      219716.272     2129517.057      219883.259
     2129051.251      219918.415     2128743.643      220050.246
#Sta/Elev= 30
       0   64.71   47.81   65.47  120.87   63.89  391.84   64.67  601.27   61.65
  728.62   61.48  736.85   60.64 1221.21   60.19 1279.81   61.23 1305.73   59.77
 1477.37   59.07 1551.77   61.18 1725.61   57.42 1863.96   56.74 1917.95   54.02
  1977.6   55.19 1994.85   51.03 2009.86   50.88 2018.23    54.8 2037.22   55.52
  2190.1   54.45 2258.14   56.11 2318.65   55.12 2367.73   57.13 2416.07   56.61
 2468.48   58.61 2495.43   57.83 2547.74   59.62 2667.68   59.69 2709.03   61.08
#Mann= 3 , 0 , 0
       0     .12       0  1977.6     .06       0 2018.23     .12       0
#XS Ineff= 2 , 0
         1939.32   64.03  2404.9           64.09
Permanent Ineff=
       F       F
Bank Sta=1977.6,2018.23
XS Rating Curve= 0
Exp/Cntr=.3,.1

Type RM Length L Ch R = 1 ,51473.53,260.64,253.63,245.18
XS GIS Cut Line= 6
     2130852.954      218477.053     2130395.936      218793.449
     2129727.988       219114.24     2129367.648      219316.382
     2128936.997      219518.524     2128541.501      219773.399
#Sta/Elev= 30
       0    63.8  480.44   62.95  714.83   60.88  751.74    62.4  791.29   60.85
  898.54    61.6  923.59   63.37   981.7   61.74 1064.48   62.63 1073.98   61.37
 1124.68   61.24 1378.88   62.58 1387.16   61.36 1662.69   57.41 1685.31   58.66
 1692.37   57.27 1794.12   53.35 1957.65   54.78 1967.26   51.71 1987.97   51.38
 2000.15   55.28 2138.74   55.84 2181.93   58.01 2202.08   56.28 2268.05   56.78
 2297.16   57.98 2303.27   59.62 2327.05    58.4 2591.16   59.96 2656.25   58.84
#Mann= 3 , 0 , 0
       0     .12       0 1957.65     .06       0 2000.15     .12       0
#XS Ineff= 2 , 0
         1736.29      64 2201.87           64.09
Permanent Ineff=
       F       F
Bank Sta=1957.65,2000.15
XS Rating Curve= 0
Exp/Cntr=.3,.1

Type RM Length L Ch R = 1 ,51219.90,245.88,299.16,286.05
XS GIS Cut Line= 4
     2131653.973      218099.452     2129666.041      218831.848
      2128814.07      219325.094     2128454.023      219585.966
#Sta/Elev= 30
       0   62.81   19.32   61.47   64.66   62.82   74.09   61.53  114.82   64.16
  188.31    62.4  728.15   63.79  784.95   62.62 1008.88   64.31 1067.09   62.59
 1291.06   62.89 1496.93   60.84 2100.04   61.47 2291.45   59.41 2293.61   60.41
 2324.42   58.71 2611.75   54.98 2714.81    54.1 2735.28   55.33    2796    53.2
 2839.73   51.58 2877.31   53.37 2954.77    53.6 2993.79   57.11 3004.15   56.05
 3073.78   57.65 3191.03   56.84 3339.62   58.64 3480.62   57.66 3547.63    59.1
#Mann= 3 , 0 , 0
       0     .12       0    2796     .06       0 2877.31     .12       0
#XS Ineff= 2 , 0
          2623.1   62.53  2996.5           62.67
Permanent Ineff=
       F       F
Bank Sta=2796,2877.31
XS Rating Curve= 0
Exp/Cntr=.3,.1

Type RM Length L Ch R = 1 ,50920.74,420.39,438.32,390.36
XS GIS Cut Line= 3
     2132774.987      217636.099     2129770.669      218592.698
     2128423.897      219179.753
#Sta/Elev= 30
       0   61.31  358.46   62.03  549.98   60.15 1215.27   62.36  1226.4   60.98
 2078.23   64.05 2107.88   62.66 2466.79   63.26 2643.29   61.13 2769.52   63.26
  2899.2   60.53  2953.8   62.65 3241.84    60.4 3307.82   62.48 3340.16   60.55
 3540.39   59.51 3820.12   54.69 3911.77   55.65 3959.03   53.31 4073.64   54.78
 4109.04   53.38 4117.26   51.52 4143.49   51.28 4153.41   53.38 4268.37   55.75
 4272.53   54.29  4342.3   56.04 4414.13   55.01 4530.08   58.03  4622.1   57.86
#Mann= 3 , 0 , 0
       0     .12       0 4109.04     .06       0 4153.41     .12       0
#XS Ineff= 2 , 0
          3827.3   61.78 4253.21           61.72
Permanent Ineff=
       F       F
Bank Sta=4109.04,4153.41
XS Rating Curve= 0
Exp/Cntr=.3,.1

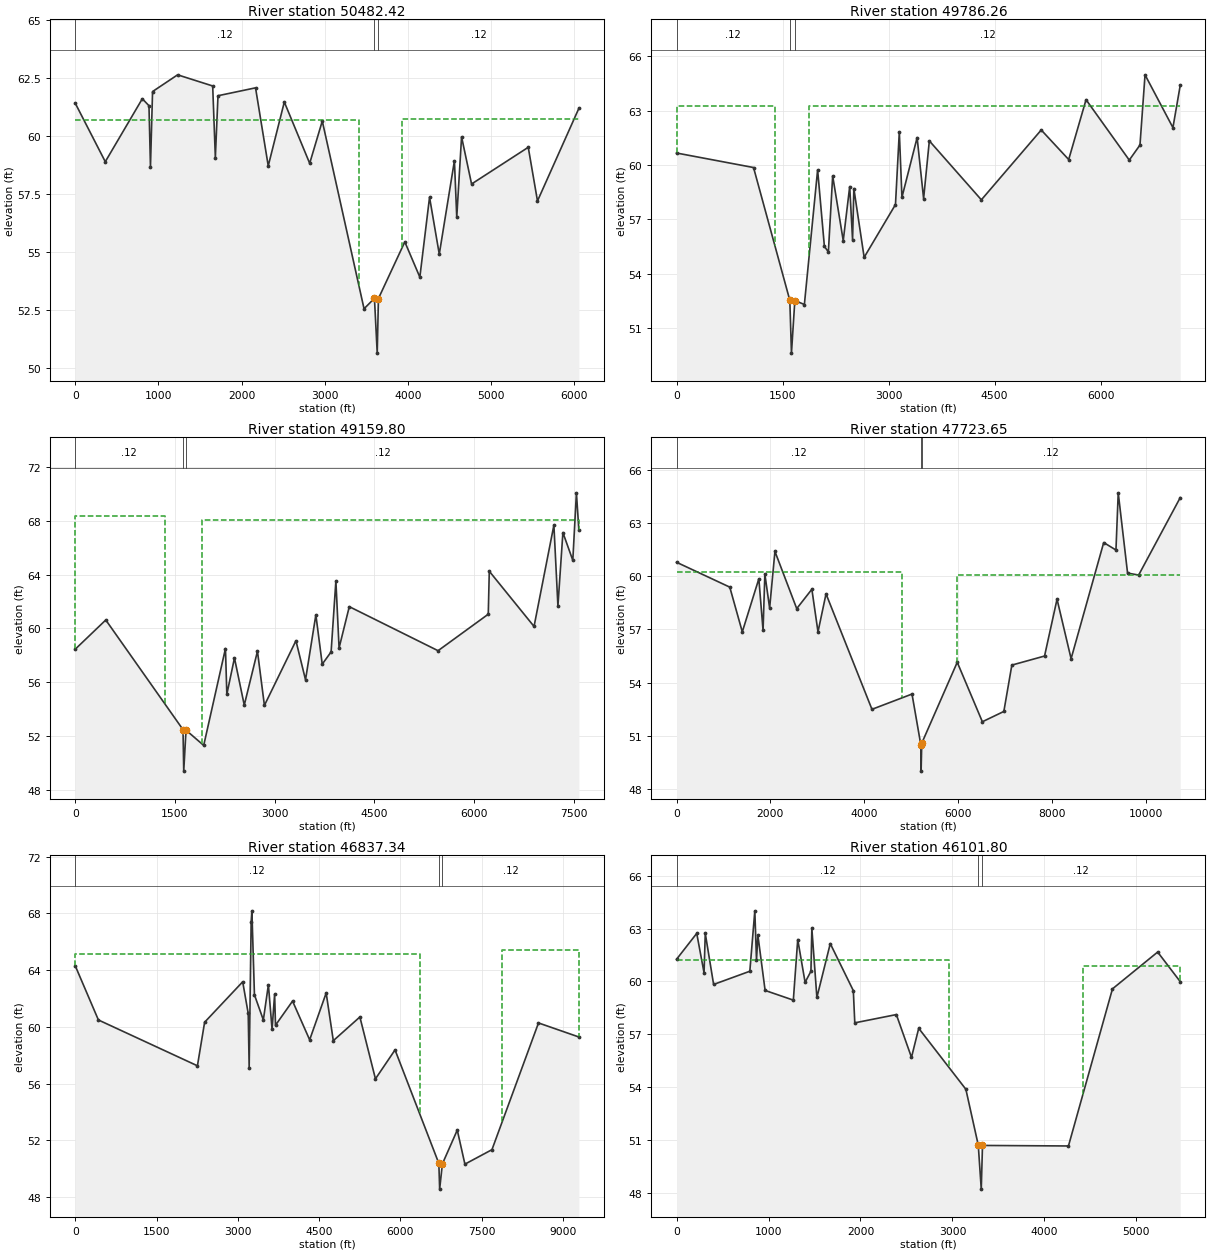
Type RM Length L Ch R = 1 ,50482.42,672.84,696.16,726.15
XS GIS Cut Line= 5
     2132276.302      217401.345     2131280.302      217621.152
     2130652.534      217636.099     2128308.391      218858.164
     2128367.841      220623.352
#Sta/Elev= 30
       0   61.42  361.57    58.9  806.91   61.61  886.96   61.31  904.95   58.68
   930.1   61.92  1231.4   62.64 1653.34   62.16  1685.3   59.08 1717.08   61.74
  2168.7   62.08 2321.44   58.72 2514.74   61.47 2819.95   58.83 2971.43   60.65
 3473.71   52.57 3598.92   53.02 3632.07   50.66 3646.72   53.01 3964.06   55.45
 4144.85   53.93 4261.49   57.37 4378.49   54.92 4560.61   58.94 4588.66   56.51
 4646.66   59.97 4766.89   57.94 5448.61   59.52 5559.69   57.21 6057.67    61.2
#Mann= 3 , 0 , 0
       0     .12       0 3598.92     .06       0 3646.72     .12       0
#XS Ineff= 2 , 0
         3414.24   60.68 3928.82           60.73
Permanent Ineff=
       F       F
Bank Sta=3598.92,3646.72
XS Rating Curve= 0
Exp/Cntr=.3,.1

Type RM Length L Ch R = 1 ,49786.26,618.55,626.46,610.01
XS GIS Cut Line= 3
     2130353.597      217277.375     2128709.442      217905.143
     2124165.598      220759.992
#Sta/Elev= 30
       0   60.66 1089.05   59.86 1602.38   52.54 1625.56   49.63 1673.44   52.53
 1808.33   52.31 1995.77   59.73  2091.6   55.51  2147.8   55.21 2208.73    59.4
 2358.17   55.83 2449.66   58.81 2490.19   55.87 2508.35    58.7 2654.06   54.91
 3097.33   57.82 3151.58   61.83 3188.78   58.22 3403.47   61.51 3495.33   58.15
 3576.32   61.33 4312.46   58.08 5159.52   61.93 5548.04    60.3 5793.59    63.6
 6405.11   60.27 6556.63    61.1  6628.1   64.97 7022.81   62.06 7126.18   64.39
#Mann= 3 , 0 , 0
       0     .12       0 1602.38     .06       0 1673.44     .12       0
#XS Ineff= 2 , 0
          1390.9   63.27 1876.31           63.27
Permanent Ineff=
       F       F
Bank Sta=1602.38,1673.44
XS Rating Curve= 0
Exp/Cntr=.3,.1

Type RM Length L Ch R = 1 ,49159.80,1177.21,1436.16,1311.17
XS GIS Cut Line= 5
     2130177.412      216678.485     2129688.461      216828.969
     2126962.386      218111.269     2127080.147      218763.132
     2124164.658      220488.626
#Sta/Elev= 30
       0   58.46   459.5   60.63 1620.93   52.49 1631.84   49.41 1666.37   52.45
 1932.19   51.32 2259.26   58.51 2280.07   55.11 2394.66   57.81 2542.26   54.31
 2740.54   58.31 2845.12   54.29 3319.25   59.09 3463.42   56.19 3618.86   61.01
 3714.63   57.35 3848.06   58.26 3919.96   63.53 3967.82   58.55 4121.63   61.62
 5456.53   58.35 6211.61   61.06 6226.89   64.25 6899.98   60.15 7198.53   67.67
 7259.02   61.67 7334.01   67.12 7482.94   65.06 7537.17   70.07 7574.43   67.29
#Mann= 3 , 0 , 0
       0     .12       0 1620.93     .06       0 1666.37     .12       0
#XS Ineff= 2 , 0
         1353.56   68.33 1913.65           68.06
Permanent Ineff=
       F       F
Bank Sta=1620.93,1666.37
XS Rating Curve= 0
Exp/Cntr=.3,.1

Type RM Length L Ch R = 1 ,47723.65,835.04,886.31,764.62
XS GIS Cut Line= 4
     2132855.579      217366.122     2129135.428       215872.37
     2127476.327      216485.191     2123216.473      219026.157
#Sta/Elev= 30
       0   60.78 1134.37   59.38 1401.44   56.86 1754.09   59.85 1844.03   56.94
 1882.32   60.12 1983.93    58.2    2097   61.39 2561.84   58.17 2884.44   59.26
 3015.15   56.86 3186.32      59 4165.59    52.5 5019.39   53.36 5206.84   50.51
 5213.48   49.02 5226.84   50.59 5983.77   55.15 6519.34    51.8 6977.08   52.38
 7147.86   54.99 7844.95    55.5 8111.27    58.7 8410.92   55.35 9106.31   61.89
 9367.38   61.47 9415.82   64.69 9614.93   60.17 9851.17   60.0610737.64   64.42
#Mann= 3 , 0 , 0
       0     .12       0 5206.84     .06       0 5226.84     .12       0
#XS Ineff= 2 , 0
          4802.8   60.21    5979           60.04
Permanent Ineff=
       F       F
Bank Sta=5206.84,5226.84
XS Rating Curve= 0
Exp/Cntr=.3,.1

Type RM Length L Ch R = 1 ,46837.34,516.61,735.54,549.78
XS GIS Cut Line= 5
     2133902.787      213289.153     2129975.802      214320.483
     2128210.642      215312.145     2126564.569      216126.467
     2125338.927      216739.288
#Sta/Elev= 30
       0   64.31  427.47   60.49 2254.41   57.26 2387.18   60.33 3089.65   63.18
 3191.22   60.95 3208.89   57.14 3245.58   67.39 3259.03   68.18 3306.33   62.26
 3470.36   60.49 3563.39   62.97 3631.11   59.84 3678.49    62.3 3694.73   60.12
 4009.38   61.82 4324.68   59.09 4629.57   62.39 4761.11   59.03 5251.34    60.7
 5538.41   56.34    5900   58.38 6708.19   50.38  6722.9   48.57 6773.57   50.35
 7047.94   52.73 7188.87   50.33 7687.79   51.35 8546.34   60.28 9291.59   59.29
#Mann= 3 , 0 , 0
       0     .12       0 6708.19     .06       0 6773.57     .12       0
#XS Ineff= 2 , 0
         6359.39   65.16 7876.31           65.43
Permanent Ineff=
       F       F
Bank Sta=6708.19,6773.57
XS Rating Curve= 0
Exp/Cntr=.3,.1

Type RM Length L Ch R = 1 ,46101.80,694.6,824.16,627.78
XS GIS Cut Line= 3
     2130301.283      213929.279     2128776.703        214542.1
     2125279.139       216111.52
#Sta/Elev= 30
       0   61.26   219.4   62.73  298.94   60.49  312.05   62.73  402.89   59.83
  796.67   60.58  850.91   64.01  869.12   61.22   884.4   62.62  962.82   59.49
 1269.71   58.94 1317.52   62.38 1397.63   59.95 1461.13   60.58 1470.92   63.02
 1525.78   59.09 1671.26   62.15    1922   59.48 1937.91   57.65 2389.93   58.12
 2554.46   55.69 2633.04   57.34 3145.71   53.88 3280.53   50.71 3313.12   48.21
 3326.56   50.69 4261.27   50.66 4739.83   59.58 5231.31   61.67 5476.67   59.99
#Mann= 3 , 0 , 0
       0     .12       0 3280.53     .06       0 3326.56     .12       0
#XS Ineff= 2 , 0
         2961.49   61.22 4417.74           60.89
Permanent Ineff=
       F       F
Bank Sta=3280.53,3326.56
XS Rating Curve= 0
Exp/Cntr=.3,.1