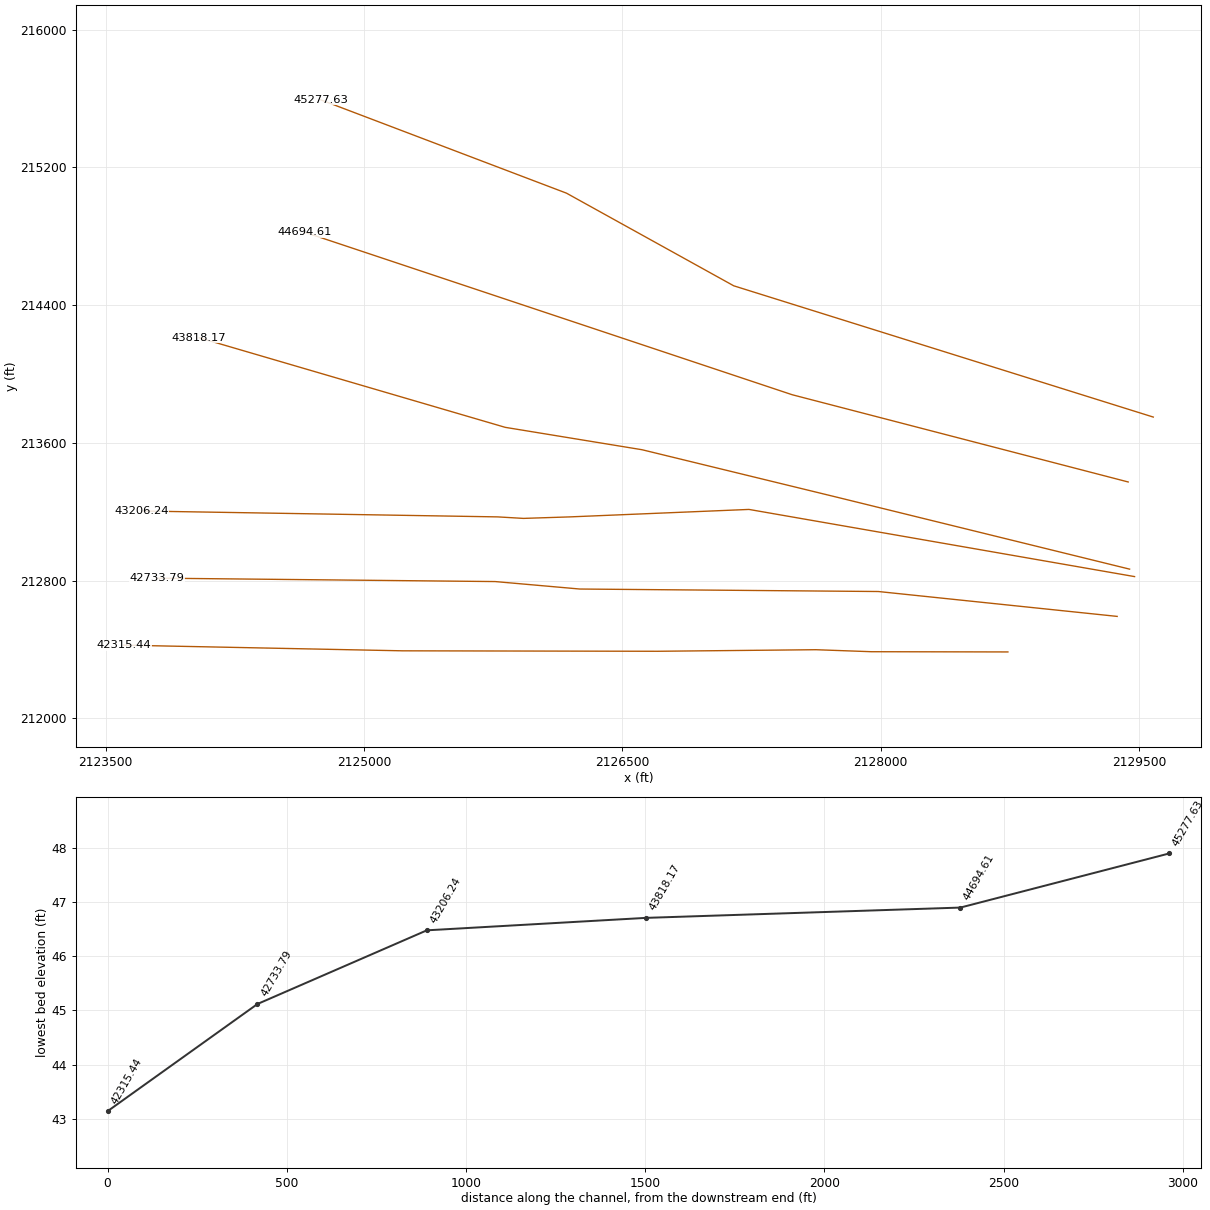
HEC-RAS study bogue.prj: NCFM-Bogue Swamp - Detailed Study

--- bogue.g01 (geometry) --- (continued)

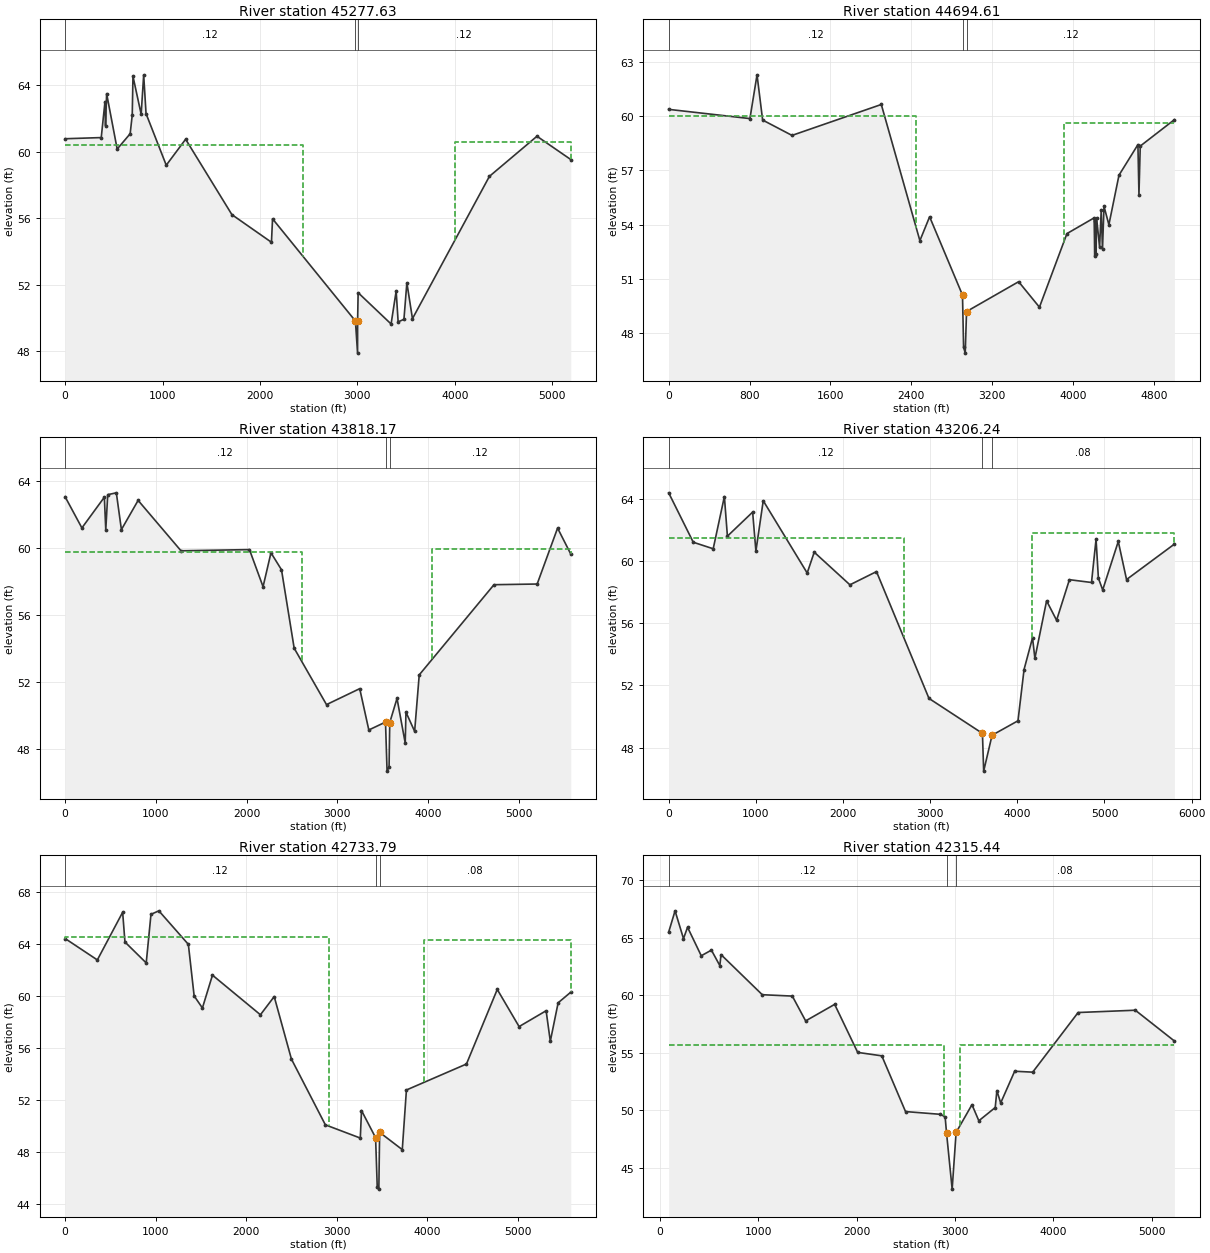
Type RM Length L Ch R = 1 ,45277.63,513.39,583.03,693.43
XS GIS Cut Line= 4
     2129583.834      213749.917     2127147.496      214512.206
      2126175.95      215050.293     2124748.379      215592.611
#Sta/Elev= 30
       0   60.78  371.16   60.85  409.66   63.01  415.19   61.56  426.53   63.49
   534.7   60.16  667.98   61.08  689.35    62.2  696.84   64.53  780.91   62.25
  806.74   64.62  830.98   62.29 1038.41   59.19 1237.27   60.75  1712.3   56.22
 2118.22   54.56 2129.37   55.97    2980   49.83 3002.05    47.9 3002.45   49.86
 3007.92   51.53 3346.12   49.65 3398.09   51.63  3418.4   49.78 3477.91   49.93
 3507.98   52.13 3565.39   49.97 4355.14   58.52 4843.24   60.93 5190.52   59.53
#Mann= 3 , 0 , 0
       0     .12       0    2980     .06       0 3002.45     .12       0
#XS Ineff= 2 , 0
         2443.41   60.43 3997.67           60.58
Permanent Ineff=
       F       F
Bank Sta=2980,3002.45
XS Rating Curve= 0
Exp/Cntr=.3,.1

Type RM Length L Ch R = 1 ,44694.61,615.67,876.43,721.53
XS GIS Cut Line= 3
     2129438.106      213372.994     2127487.103      213879.571
     2124653.014      214824.267
#Sta/Elev= 30
       0   60.38  803.79   59.87  874.03   62.29  929.51   59.79 1220.06   58.94
 2103.42   60.65 2485.17   53.12 2581.37   54.44 2906.79   50.11 2917.53   47.23
 2933.73    46.9 2946.82    49.2 3462.06   50.85 3667.92   49.44 3940.04   53.51
 4209.03   54.38 4215.18   52.26 4216.86   54.19 4227.54   52.37 4233.43   54.37
 4263.05   52.76 4278.96   54.79  4291.8   52.65 4306.59   55.02 4355.02      54
  4454.9   56.74 4642.24   58.43 4652.44   55.67 4665.28   58.35 5003.09   59.81
#Mann= 3 , 0 , 0
       0     .12       0 2906.79     .06       0 2946.82     .12       0
#XS Ineff= 2 , 0
         2450.41   60.03 3906.65           59.64
Permanent Ineff=
       F       F
Bank Sta=2906.79,2946.82
XS Rating Curve= 0
Exp/Cntr=.3,.1

Type RM Length L Ch R = 1 ,43818.17,468.13,611.93,577.9
XS GIS Cut Line= 5
     2129446.267      212866.858     2127741.602      213285.801
     2126614.789      213560.281     2125820.242      213690.298
     2124043.345      214210.365
#Sta/Elev= 30
       0   63.05  185.25   61.19  432.79   63.02  448.35   61.07  469.89   63.17
  564.73   63.28  620.57   61.09  804.71   62.83 1276.92   59.83  2031.4    59.9
 2181.22   57.69  2268.4   59.71 2384.28    58.7 2523.97   54.03 2880.22   50.67
 3246.16   51.62 3346.45   49.16 3530.21   49.63 3547.43   46.71 3569.56   46.96
 3577.03    49.6 3657.08   51.04 3747.55   48.38 3755.59   50.22 3851.22   49.08
  3901.8   52.44 4725.47   57.81 5201.14   57.85 5426.15   61.18  5571.7   59.63
#Mann= 3 , 0 , 0
       0     .12       0 3530.21     .06       0 3577.03     .12       0
#XS Ineff= 2 , 0
         2611.44   59.74 4046.67           59.96
Permanent Ineff=
       F       F
Bank Sta=3530.21,3577.03
XS Rating Curve= 0
Exp/Cntr=.3,.1

Type RM Length L Ch R = 1 ,43206.24,435.91,472.45,385.95
BEGIN DESCRIPTION:
Survey Cross Section 108
END DESCRIPTION:
XS GIS Cut Line= 6
      2129475.16      212823.519     2127235.981       213213.57
     2126195.846      213170.231     2125926.027      213161.496
     2125776.903      213170.231     2123708.683      213204.416
#Sta/Elev= 30
       0   64.39  282.03   61.21  510.82   60.79  639.11   64.15   673.8    61.6
   963.3   63.15 1000.76   60.64 1084.81   63.88 1589.07   59.23 1669.95   60.57
 2079.37   58.47 2384.17   59.32 2986.28   51.16 3599.76   48.91 3613.87   46.48
 3710.15   48.79 4007.56   49.72 4077.18   53.02 4174.38   55.06 4201.45   53.74
 4335.78   57.44 4450.37   56.19  4597.7    58.8 4850.99   58.62 4903.21    61.4
 4930.04    58.9 4979.32   58.14 5158.22   61.26 5252.97   58.81 5802.05   61.09
#Mann= 3 , 0 , 0
       0     .12       0 3599.76     .06       0 3710.15     .08       0
#XS Ineff= 2 , 0
         2695.45   61.49  4172.7           61.78
Permanent Ineff=
       F       F
Bank Sta=3599.76,3710.15
XS Rating Curve= 0
Exp/Cntr=.3,.1

Type RM Length L Ch R = 1 ,42733.79,414.82,418.35,430.71
XS GIS Cut Line= 6
     2129374.035      212592.378     2127987.189      212736.841
     2126253.631      212751.288     2125762.457      212794.627
     2124332.271      212809.073     2123799.988      212814.449
#Sta/Elev= 30
       0   64.41  356.26   62.76   635.7   66.43  661.12   64.14  895.92   62.53
  948.39   66.27  1035.5   66.54 1361.11   63.96 1425.02   59.99 1516.25   59.06
 1627.27   61.59 2156.67   58.54 2309.02   59.94 2499.03   55.13 2873.61   50.07
 3259.62   49.05 3272.76   51.17 3428.34   49.08 3446.59   45.28 3464.12   45.12
 3473.01   49.49 3722.98   48.16 3768.71   52.75 4431.63   54.75 4771.67   60.49
 5012.83   57.63 5311.18   58.85  5357.4    56.5 5443.72   59.46 5583.62   60.28
#Mann= 3 , 0 , 0
       0     .12       0 3428.34     .06       0 3473.01     .08       0
#XS Ineff= 2 , 0
         2908.89   64.54 3961.75           64.33
Permanent Ineff=
       F       F
Bank Sta=3428.34,3473.01
XS Rating Curve= 0
Exp/Cntr=.5,.3

Type RM Length L Ch R = 1 ,42315.44,283.52,310.04,370.35
XS GIS Cut Line= 6
     2128739.608      212385.956     2127947.391      212387.251
     2127624.421      212398.901     2126705.346       212389.84
     2125225.118      212392.429 2123604.2880197  212425.3990149
#Sta/Elev= 30
      92   65.51  156.79   67.36  242.46   64.94  283.66   65.93  422.86   63.45
  526.11   63.94  611.68   62.59  623.51   63.55 1042.48   60.06 1347.74   59.94
 1483.04   57.78 1777.65   59.22 2011.46   55.04 2256.43   54.74 2497.37   49.89
 2851.38   49.65 2899.69   49.43    2914   48.02    2971   43.14    3011   48.07
  3172.2   50.49 3242.03   49.09 3408.38   50.24  3425.2   51.71 3463.86   50.64
 3605.86    53.4 3788.94   53.32 4250.23   58.51 4831.17   58.71 5228.07   56.03
#Mann= 3 , 0 , 0
      92     .12       0    2914     .06       0    3011     .08       0
#XS Ineff= 2 , 0
       0  2889.5   55.65    3049       0   55.65
Permanent Ineff=
       F       F
Bank Sta=2914,3011
XS Rating Curve= 0
Exp/Cntr=.5,.3