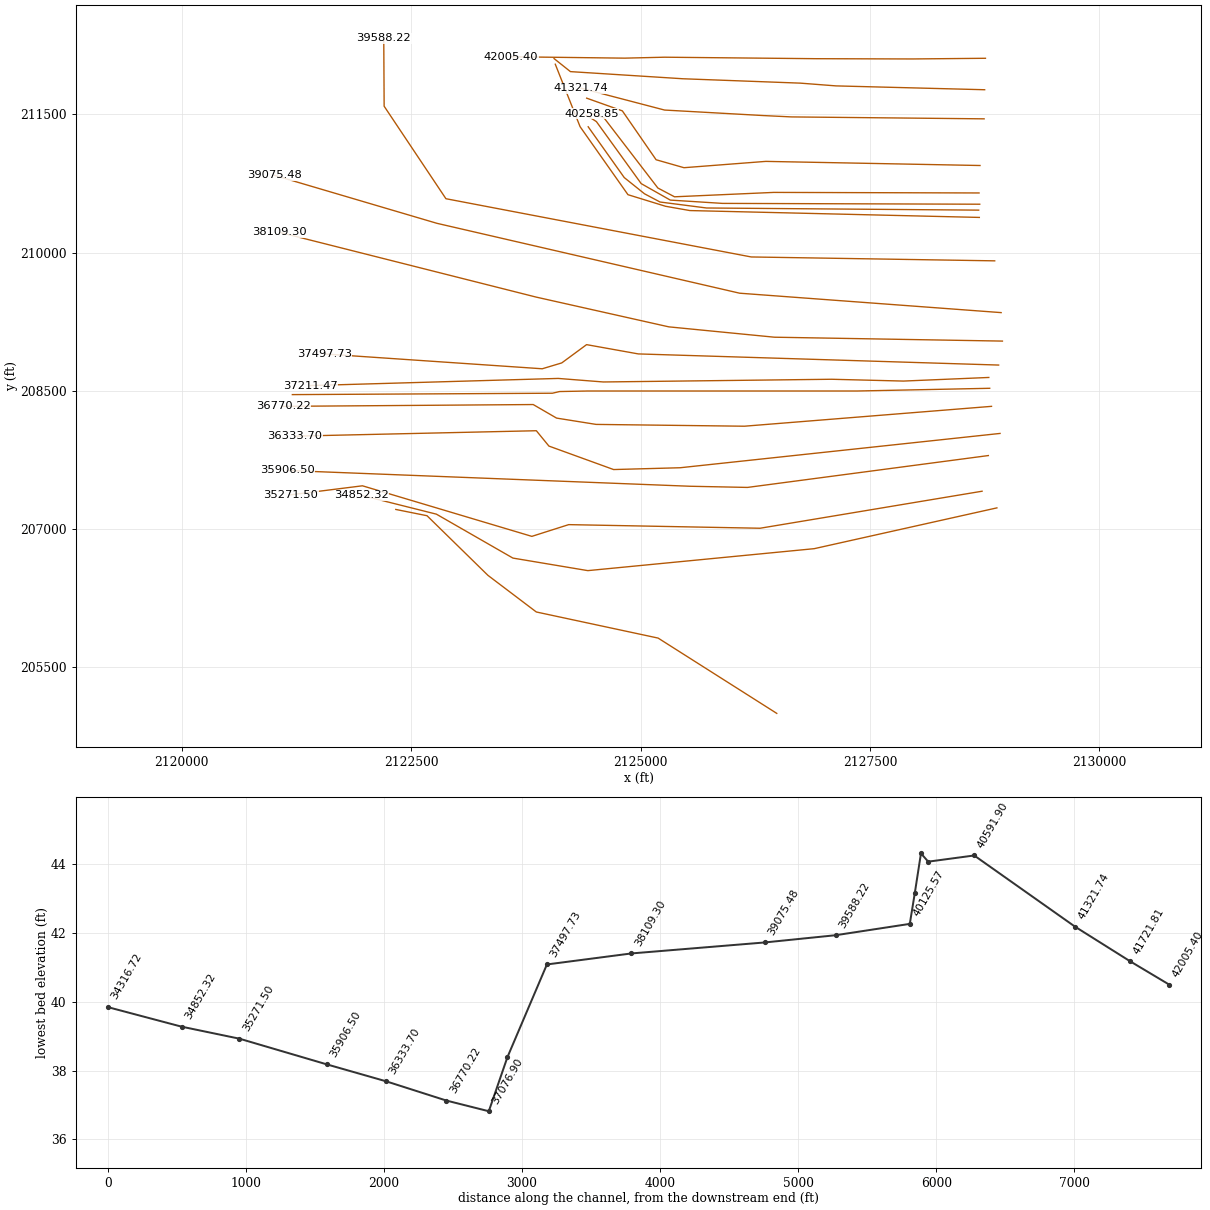
HEC-RAS study bogue.prj: NCFM-Bogue Swamp - Detailed Study

--- bogue.g01 (geometry) --- (continued)

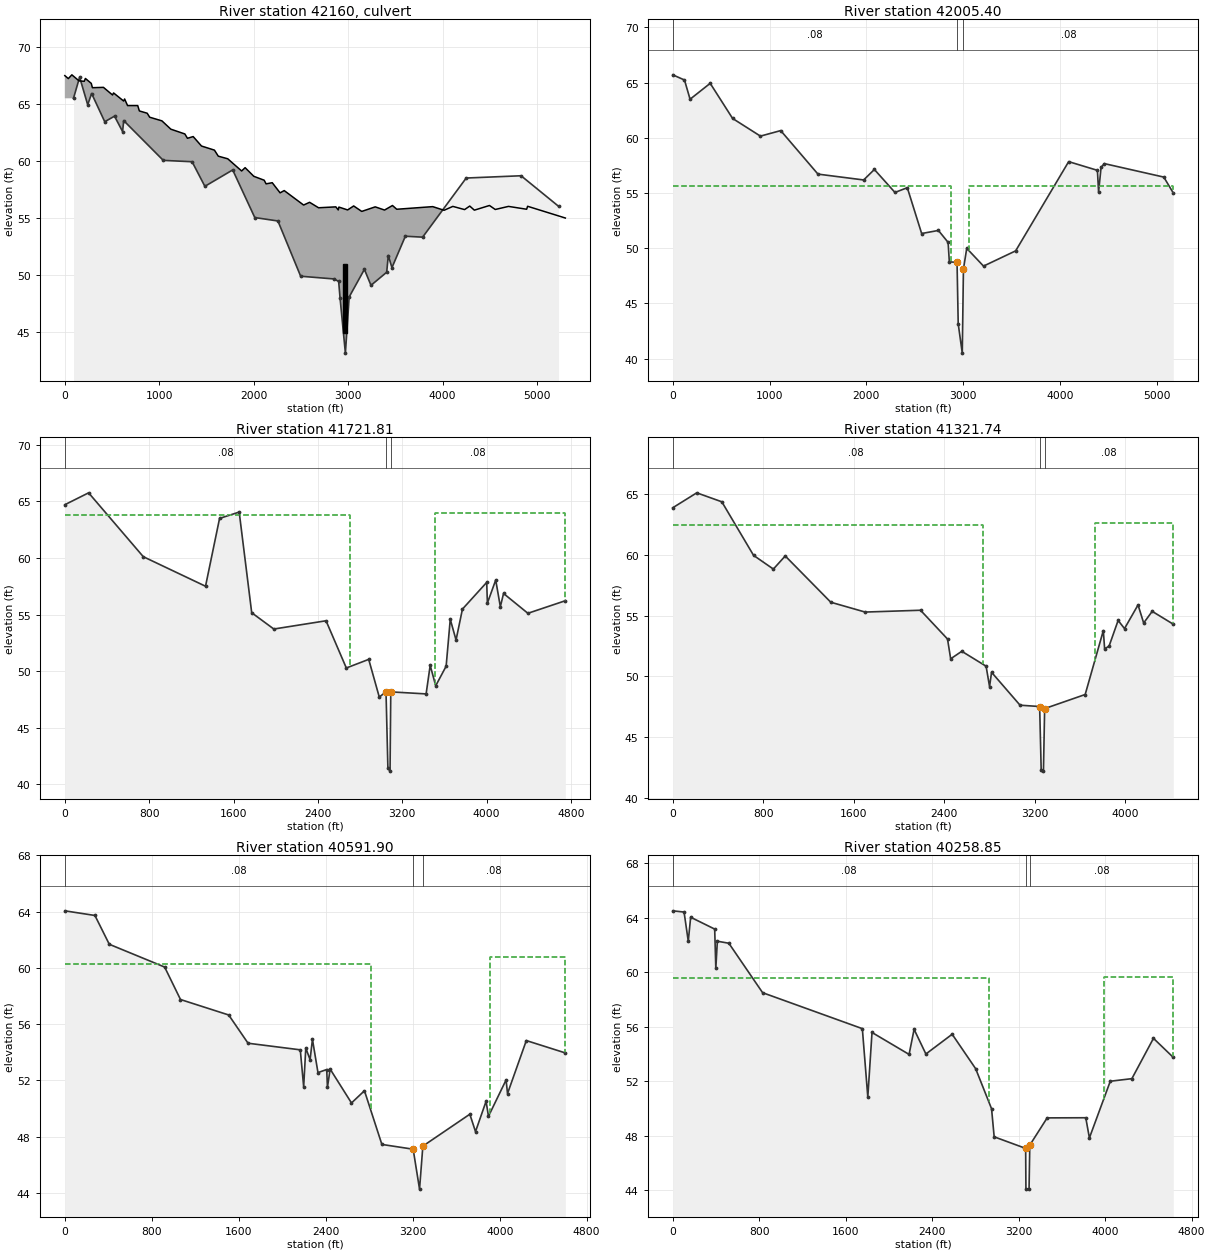
Type RM Length L Ch R = 2 ,42160   ,,,
BEGIN DESCRIPTION:
US Hwy 74/76 -- 4-9x5 RCB - Survey Structure #71
END DESCRIPTION:
Bridge Culvert--1,0,-1,-1, 0
Deck Dist Width WeirC Skew NumUp NumDn MinLoCord MaxHiCord MaxSubmerge Is_Ogee
60,174,2.6,0, 60, 60, , , .95, 0, 0,0,,
       0   37.09   74.58  150.46  205.55     218  280.06  292.19   408.9  505.16
  516.34  622.91   633.3  664.56  772.11  789.31  872.15   898.6 1028.08 1122.52
 1271.02 1298.62 1359.16  1447.3  1584.3 1625.07 1725.34 1872.23 1909.14 2001.53
 2110.97  2131.3 2196.35 2279.48 2322.95 2528.43 2591.93 2686.92 2869.94 2895.22
 2902.24 2994.72 3058.69 3143.99 3286.71 3385.56 3469.47 3514.73 3895.89 4015.85
 4108.79 4233.15 4287.67 4336.45 4496.52 4557.73 4698.18 4890.33 4900.48    5300
    67.5   67.24   67.57   67.04      67   67.25   66.82   66.44   66.47    65.8
   65.98   65.27   65.45   64.87   64.87    64.4    64.2   63.85   63.53    62.8
   62.38      62   62.15   61.32   60.96   60.43    60.2   59.13   59.42   58.66
   58.32      58    58.1   57.21   57.41   56.14   56.38    55.9   55.98   55.71
   55.96   55.71   56.06   55.58   55.98    55.7    56.1   55.77      56   55.68
   56.02   55.74   56.05   55.69    56.1   55.75   56.02   55.77   56.03      55
                                                                                
                                                                                
                                                                                
                                                                                
                                                                                
                                                                                
       0   37.09   74.58  150.46  205.55     218  280.06  292.19   408.9  505.16
  516.34  622.91   633.3  664.56  772.11  789.31  872.15   898.6 1028.08 1122.52
 1271.02 1298.62 1359.16  1447.3  1584.3 1625.07 1725.34 1872.23 1909.14 2001.53
 2110.97  2131.3 2196.35 2279.48 2322.95 2528.43 2591.93 2686.92 2869.94 2895.22
 2902.24 2994.72 3058.69 3143.99 3286.71 3385.56 3469.47 3514.73 3895.89 4015.85
 4108.79 4233.15 4287.67 4336.45 4496.52 4557.73 4698.18 4890.33 4900.48    5300
    67.5   67.24   67.57   67.04      67   67.25   66.82   66.44   66.47    65.8
   65.98   65.27   65.45   64.87   64.87    64.4    64.2   63.85   63.53    62.8
   62.38      62   62.15   61.32   60.96   60.43    60.2   59.13   59.42   58.66
   58.32      58    58.1   57.21   57.41   56.14   56.38    55.9   55.98   55.71
   55.96   55.71   56.06   55.58   55.98    55.7    56.1   55.77      56   55.68
   56.02   55.74   56.05   55.69    56.1   55.75   56.02   55.77   56.03      55
                                                                                
                                                                                
                                                                                
                                                                                
                                                                                
                                                                                
BR Coef=-1 , 1 , 0 ,, 0 ,,,.8,0,1.2,0,
WSPro=,,,, 1 ,,,, 0 ,,,, 0 ,,,,-1 ,-1 ,-1 , 0 , 0 , 0 , 0 , 0
Multiple Barrel Culv=2,6,9,174,.013,.4,1,8,1,44.95,44.45, 4,Culvert #1  , 0 ,60
    2954    2954    2964    2964    2974    2974    2984    2984
Culvert Bottom n=.013
BR U #Sta/Elev= 30
      92   65.51  156.79   67.36  242.46   64.94  283.66   65.93  422.86   63.45
  526.11   63.94  611.68   62.59  623.51   63.55 1042.48   60.06 1347.74   59.94
 1483.04   57.78 1777.65   59.22 2011.46   55.04 2256.43   54.74 2497.37   49.89
 2851.38   49.65 2899.69   49.43    2914   48.02    2971   43.14    3011   48.07
  3172.2   50.49 3242.03   49.09 3408.38   50.24  3425.2   51.71 3463.86   50.64
 3605.86    53.4 3788.94   53.32 4250.23   58.51 4831.17   58.71 5228.07   56.03
BR U #Mann= 3
      92     .12    2914     .05    3011     .08
BR D #Sta/Elev= 30
       0    65.7  121.17   65.23  178.89   63.49  386.87   64.93  618.45   61.75
  905.85   60.15 1115.66   60.65 1500.54   56.71 1972.92   56.18 2083.48   57.13
 2296.35   55.05  2423.9   55.48 2572.18   51.33 2745.25   51.61 2845.49   50.53
 2858.26   48.77    2938   48.71    2950   43.16    2992    40.5    3004    48.1
 3038.08   49.99 3211.56   48.38 3543.62   49.76  4091.6   57.84 4388.77   57.05
 4400.69   55.09  4426.5   57.32 4460.64   57.66 5074.68   56.44 5172.71      55
BR D #Mann= 3
       0     .08    2938     .05    3004     .08
BC Design=,, 0 ,, 0 ,,,,,,

Type RM Length L Ch R = 1 ,42005.40,245.46,283.6,339.32
XS GIS Cut Line= 6
     2128757.778      212106.949     2127956.113      212099.648
      2126903.29      212102.568     2125259.805      212118.631
     2124824.657      212108.409  2123585.393665  212123.6330938
#Sta/Elev= 30
       0    65.7  121.17   65.23  178.89   63.49  386.87   64.93  618.45   61.75
  905.85   60.15 1115.66   60.65 1500.54   56.71 1972.92   56.18 2083.48   57.13
 2296.35   55.05  2423.9   55.48 2572.18   51.33 2745.25   51.61 2845.49   50.53
 2858.26   48.77    2938   48.71    2950   43.16    2992    40.5    3004    48.1
 3038.08   49.99 3211.56   48.38 3543.62   49.76  4091.6   57.84 4388.77   57.05
 4400.69   55.09  4426.5   57.32 4460.64   57.66 5074.68   56.44 5172.71      55
#Mann= 3 , 0 , 0
       0     .08       0    2938     .06       0    3004     .08       0
#XS Ineff= 2 , 0
       0  2873.5   55.65  3064.5       0   55.65
Permanent Ineff=
       F       F
Bank Sta=2938,3004
XS Rating Curve= 0
Exp/Cntr=.5,.3

Type RM Length L Ch R = 1 ,41721.81,358.77,400.07,375.08
XS GIS Cut Line= 6
     2128749.089      211765.785     2127129.204      211807.473
     2126742.099       211837.25     2125460.187      211884.894
     2124234.852      211962.315      2124056.71       212103.55
#Sta/Elev= 30
       0   64.71  225.65   65.76  744.07   60.12  1334.4   57.51 1467.49    63.5
 1653.63   64.06 1772.29   55.17 1982.03   53.73 2477.26   54.46 2669.54   50.29
  2881.9   51.05 2982.14   47.72 3045.97   48.19 3063.77   41.46 3084.19   41.18
 3091.17   48.18 3426.24      48 3464.84   50.52 3517.38   48.72 3616.22   50.45
  3655.3   54.59 3710.12   52.76 3770.74   55.49  4000.8   57.85  4007.4   56.02
 4086.38   58.06 4130.17    55.7 4160.61   56.87  4391.5   55.12 4746.58   56.23
#Mann= 3 , 0 , 0
       0     .08       0 3045.97     .06       0 3091.17     .08       0
#XS Ineff= 2 , 0
         2701.28   63.76 3515.19           63.94
Permanent Ineff=
       F       F
Bank Sta=3045.97,3091.17
XS Rating Curve= 0
Exp/Cntr=.3,.1

Type RM Length L Ch R = 1 ,41321.74,605.33,729.84,528.82
XS GIS Cut Line= 5
     2128743.133      211450.146     2126643.834       211470.99
      2126334.15      211485.878     2125260.679      211545.433
     2124351.068      211782.222
#Sta/Elev= 30
       0   63.88  212.11   65.11  433.76   64.37  714.28   59.96  889.35   58.83
  994.32   59.91  1396.9    56.1 1700.64   55.29 2190.26   55.44 2428.81   53.07
 2456.65   51.44 2554.96   52.06 2769.87   50.83 2800.35   49.15 2818.09   50.33
 3069.93   47.62 3243.15   47.51 3256.83   42.27 3276.74   42.19  3287.4   47.34
 3645.62    48.5 3805.99   53.76  3817.6   52.26 3857.04   52.49 3936.94    54.6
 3993.39   53.93 4112.99   55.88 4162.64   54.39 4238.21   55.35 4424.49   54.29
#Mann= 3 , 0 , 0
       0     .08       0 3243.15     .06       0  3287.4     .08       0
#XS Ineff= 2 , 0
         2742.12   62.46 3728.12           62.62
Permanent Ineff=
       F       F
Bank Sta=3243.15,3287.4
XS Rating Curve= 0
Exp/Cntr=.3,.1

Type RM Length L Ch R = 1 ,40591.90,427.64,333.05,440.22
XS GIS Cut Line= 6
     2128698.467      210943.932     2126363.928      210988.598
     2125472.098       210920.11      2125168.37      211006.464
      2124800.62        211536.5     2124411.911      211674.375
#Sta/Elev= 30
       0   64.06  276.91   63.73  408.98   61.68  918.14   60.06 1064.04   57.75
  1507.4   56.65 1685.41   54.64 2165.83   54.17 2196.98   51.54 2216.44    54.3
 2255.99   53.47 2277.67   54.92 2328.48   52.55 2408.89   52.77 2415.56    51.5
 2440.53    52.8  2636.8   50.39 2756.03   51.26 2916.42   47.44 3204.06    47.1
 3262.75   44.26 3293.24   47.32 3725.41   49.59 3777.53   48.35 3874.85   50.51
 3896.77   49.44  4058.8   52.03    4072   51.06 4244.96   54.83 4603.84   53.95
#Mann= 3 , 0 , 0
       0     .08       0 3204.06     .06       0 3293.24     .08       0
#XS Ineff= 2 , 0
         2812.14   60.25 3908.98            60.8
Permanent Ineff=
       F       F
Bank Sta=3204.06,3293.24
XS Rating Curve= 0
Exp/Cntr=.3,.1

Type RM Length L Ch R = 1 ,40258.85,52.59,52.51,58.72
XS GIS Cut Line= 6
     2128688.045      210646.159     2126448.793      210652.114
     2125369.366      210604.471     2125187.725      210699.758
     2124599.623      211462.057     2124465.626      211506.723
#Sta/Elev= 30
       0   64.51  104.64   64.42  143.46   62.28  165.59   64.04  387.85   63.17
  398.33   60.29  412.49   62.28  518.86   62.13  831.22    58.5 1753.79   55.86
 1804.31   50.84 1843.14   55.58 2186.11   53.97 2232.46   55.81 2341.63      54
 2584.65   55.45 2802.06   52.92 2949.05   49.98 2973.24   47.92  3264.5   47.07
 3266.87    44.1 3295.88   44.08 3302.75   47.31 3463.32   49.31 3820.47   49.32
 3854.17   47.84  4047.3      52 4247.07   52.19  4446.8   55.15  4630.1   53.75
#Mann= 3 , 0 , 0
       0     .08       0  3264.5     .06       0 3302.75     .08       0
#XS Ineff= 2 , 0
         2922.99   59.58 3984.83           59.67
Permanent Ineff=
       F       F
Bank Sta=3264.5,3302.75
XS Rating Curve= 0
Exp/Cntr=.5,.3

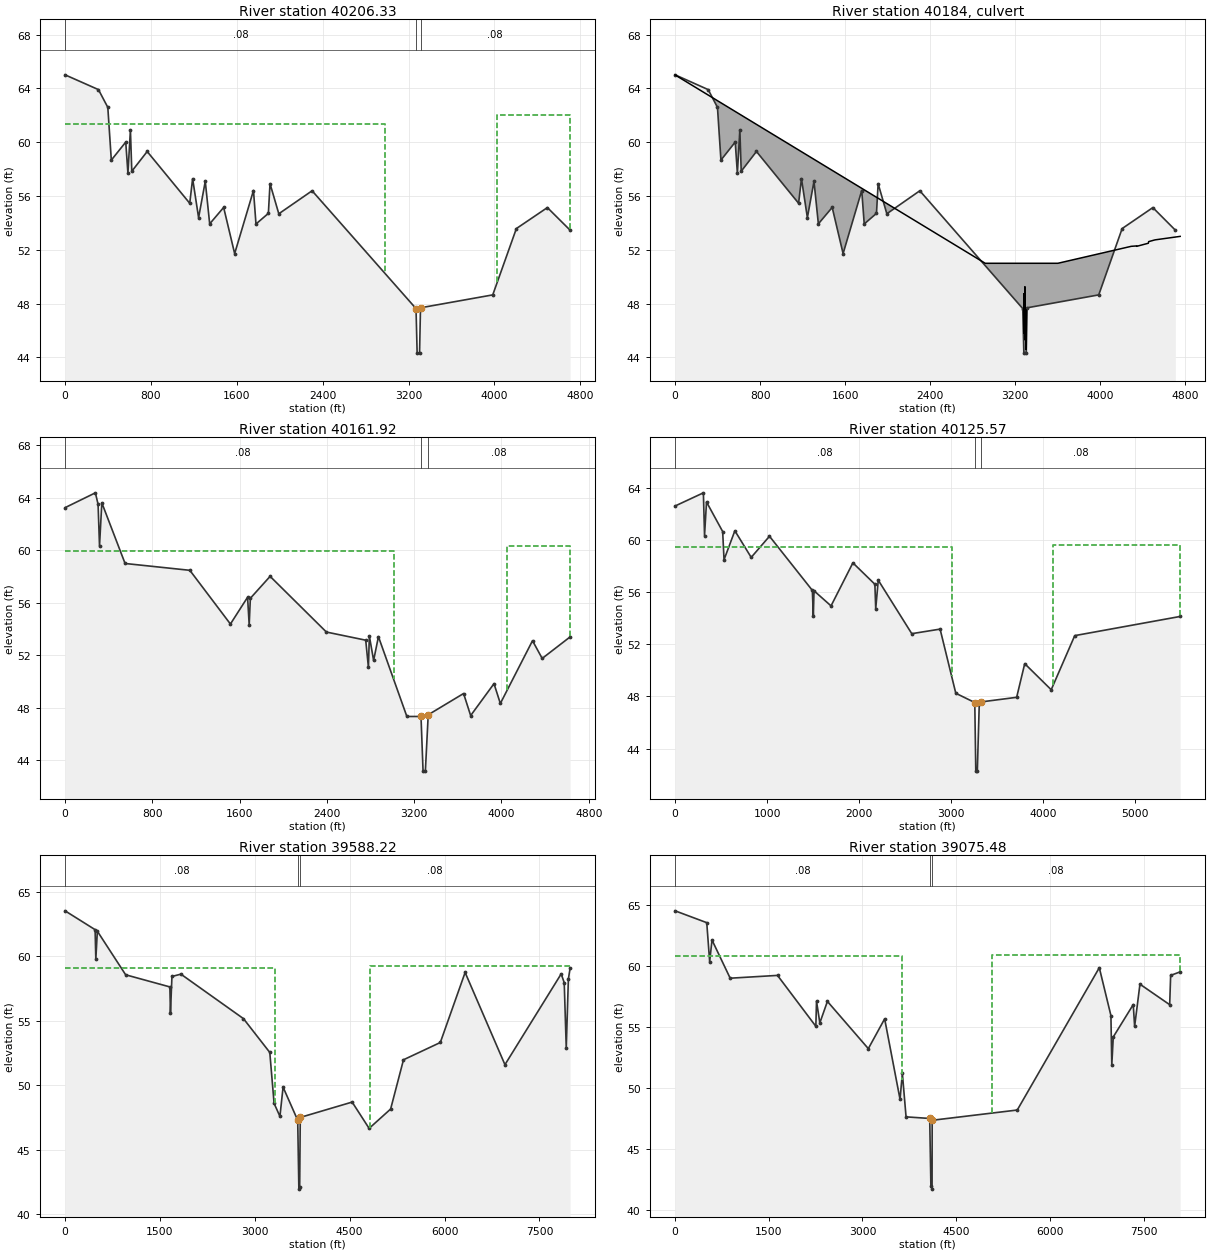
Type RM Length L Ch R = 1 ,40206.33,56.46,44.41,43.35
XS GIS Cut Line= 6
      2128695.49      210524.072     2125891.958      210533.005
     2125323.212      210568.738     2125006.083      210747.402
     2124517.736      211420.368     2124404.582      211491.834
#Sta/Elev= 30
       0   65.01  311.23   63.91  398.42   62.59  431.07   58.67  565.48   60.01
  585.74   57.69  608.99   60.91  621.76   57.84  765.14   59.31 1161.57   55.46
 1188.44   57.29 1244.14   54.39 1306.23   57.09 1347.38   53.93 1477.44   55.15
 1579.97   51.72 1755.38   56.41 1778.65   53.92 1894.08   54.71 1909.46   56.92
 1991.28   54.68 2301.45   56.39  3269.6   47.63  3279.9   44.32 3302.42   44.32
 3311.25   47.69 3984.31   48.65 4204.28   53.58 4493.13   55.14  4704.9   53.46
#Mann= 3 , 0 , 0
       0     .08       0  3269.6     .06       0 3311.25     .08       0
#XS Ineff= 2 , 0
         2981.33   61.37 4025.67           62.03
Permanent Ineff=
       F       F
Bank Sta=3269.6,3311.25
XS Rating Curve= 0
Exp/Cntr=.5,.3

Type RM Length L Ch R = 2 ,40184   ,,,
BEGIN DESCRIPTION:
Unknown Road -- 2-36" & 1-48" CMP - Survey Structure # 210
END DESCRIPTION:
Bridge Culvert--1,0,-1,-1, 0
Deck Dist Width WeirC Skew NumUp NumDn MinLoCord MaxHiCord MaxSubmerge Is_Ogee
10,24,2.6,0, 14, 14, 51, , .95, 0, 0,0,,
       0 2916.25  3204.4  3204.4 3210.44 3210.44    3600 4289.61 4340.38  4341.4
 4450.59 4453.76  4513.7    4750
      65      51      51      51      51      51      51   52.26   52.29   52.26
   52.49   52.61   52.74      53
                                                                                
                                
       0 2916.25  3204.4  3204.4 3210.44 3210.44    3600 4289.61 4340.38  4341.4
 4450.59 4453.76  4513.7    4750
      65      51      51      51      51      51      51   52.26   52.29   52.26
   52.49   52.61   52.74      53
                                                                                
                                
BR Coef=-1 , 1 , 0 ,, 0 ,,,.8,-1,1.2,0,
WSPro=,,,, 1 ,,,, 0 ,,,, 0 ,,,,-1 ,-1 ,-1 , 0 , 0 , 0 , 0 , 0
Culvert=1,3,,24,.024,.7,1,2,2,45.77,3280,45.74,3280,Culvert #1  , 0 ,10
Culvert Bottom n=.024
Culvert=1,4,,24,.024,.7,1,2,2,45.28,3290,45.28,3290,Culvert #2  , 0 ,10
Culvert Bottom n=.024
Culvert=1,3,,24,.024,.9,1,2,3,44.57,3300,44.34,3300,Culvert #3  , 0 ,10
Culvert Bottom n=.024
BR U #Sta/Elev= 30
       0   65.01  311.23   63.91  398.42   62.59  431.07   58.67  565.48   60.01
  585.74   57.69  608.99   60.91  621.76   57.84  765.14   59.31 1161.57   55.46
 1188.44   57.29 1244.14   54.39 1306.23   57.09 1347.38   53.93 1477.44   55.15
 1579.97   51.72 1755.38   56.41 1778.65   53.92 1894.08   54.71 1909.46   56.92
 1991.28   54.68 2301.45   56.39  3269.6   47.63  3279.9   44.32 3302.42   44.32
 3311.25   47.69 3984.31   48.65 4204.28   53.58 4493.13   55.14  4704.9   53.46
BR U #Mann= 3
       0     .08  3269.6     .05 3311.25     .08
BR D #Sta/Elev= 30
       0   63.23  278.02   64.36  302.71   63.49  315.88   60.32  337.11    63.6
  550.25   58.98 1143.67   58.46 1515.67   54.37 1672.97   56.41 1687.71    54.3
 1698.31   56.33 1879.45      58 2395.27   53.76 2755.72   53.14 2780.45   51.07
 2788.94   53.46  2828.1    51.6  2872.2   53.41 3132.88   47.33 3262.37   47.33
 3281.21   43.17 3302.34   43.17 3328.49   47.46 3652.59   49.08 3717.39    47.4
 3931.36   49.83 3989.46   48.32 4284.31    53.1 4373.05   51.75 4628.91   53.39
BR D #Mann= 3
       0     .08 3262.37     .05 3328.49     .08
BC Design=,, 0 ,, 0 ,,,,,,

Type RM Length L Ch R = 1 ,40161.92,36.4,36.35,38.87
XS GIS Cut Line= 6
     2128684.044      210459.865     2125717.947      210483.128
     2125211.547      210547.894     2125041.816      210637.226
     2124821.464      210812.912     2124428.404      211363.792
#Sta/Elev= 30
       0   63.23  278.02   64.36  302.71   63.49  315.88   60.32  337.11    63.6
  550.25   58.98 1143.67   58.46 1515.67   54.37 1672.97   56.41 1687.71    54.3
 1698.31   56.33 1879.45      58 2395.27   53.76 2755.72   53.14 2780.45   51.07
 2788.94   53.46  2828.1    51.6  2872.2   53.41 3132.88   47.33 3262.37   47.33
 3281.21   43.17 3302.34   43.17 3328.49   47.46 3652.59   49.08 3717.39    47.4
 3931.36   49.83 3989.46   48.32 4284.31    53.1 4373.05   51.75 4628.91   53.39
#Mann= 3 , 0 , 0
       0     .08       0 3262.37     .06       0 3328.49     .08       0
#XS Ineff= 2 , 0
          3010.5   59.94 4054.84            60.3
Permanent Ineff=
       F       F
Bank Sta=3262.37,3328.49
XS Rating Curve= 0
Exp/Cntr=.5,.3

Type RM Length L Ch R = 1 ,40125.57,369.86,537.35,567.76
XS GIS Cut Line= 6
     2128691.023      210380.769     2125536.491      210455.212
     2125271.287      210501.739      2124861.85      210627.362
     2124339.806      211365.365      2124069.75       212042.54
#Sta/Elev= 30
       0    62.6   307.3   63.61  319.77   60.33  341.21   62.91  516.75   60.64
  531.54   58.48  649.16    60.7   826.6   58.66 1025.29   60.28 1490.78   56.13
  1501.6   54.17 1508.83    56.1 1693.83   54.94 1931.21   58.24 2170.13    56.6
 2179.15   54.72 2206.81   56.91 2570.81   52.81 2878.46   53.16 3049.06   48.24
 3255.16   47.53 3266.14   42.27 3282.76   42.27  3303.8   47.41 3327.01   47.58
 3709.96   47.93 3797.68   50.51 4085.37   48.51 4340.99   52.66 5486.04   54.13
#Mann= 3 , 0 , 0
       0     .08       0 3255.16     .06       0 3327.01     .08       0
#XS Ineff= 2 , 0
          3003.5   59.48 4109.69           59.62
Permanent Ineff=
       F       F
Bank Sta=3255.16,3327.01
XS Rating Curve= 0
Exp/Cntr=.3,.1

Type RM Length L Ch R = 1 ,39588.22,401.88,512.75,606.74
XS GIS Cut Line= 5
     2128858.601       209909.82     2126205.253      209951.937
     2122878.038      210583.686      2122204.63       211587.01
      2122200.51       212323.32
#Sta/Elev= 30
       0   63.52  475.12   62.06  486.64   59.76  510.81   61.94  958.33   58.56
 1657.24   57.62 1666.48   55.56 1690.03   58.43 1831.68   58.61 2820.69   55.16
    3237   52.54 3305.05   48.59 3397.35   47.58 3446.93   49.85 3678.39   47.28
 3696.69   41.94 3709.57    42.1  3718.9    47.5 4538.94   48.69 4807.43   46.65
 5147.45   48.15 5350.72   51.97    5933   53.31  6325.1   58.74 6954.79   51.59
 7844.09   58.63 7891.99   57.95 7924.05   52.89 7957.58   58.23 7985.03   59.07
#Mann= 3 , 0 , 0
       0     .08       0 3678.39     .06       0  3718.9     .08       0
#XS Ineff= 2 , 0
         3325.55   59.12 4819.14           59.26
Permanent Ineff=
       F       F
Bank Sta=3678.39,3718.9
XS Rating Curve= 0
Exp/Cntr=.3,.1

Type RM Length L Ch R = 1 ,39075.48,570.5,966.17,650.1
XS GIS Cut Line= 4
     2128928.795      209348.265     2126078.903      209558.848
     2122779.766      210316.948     2121010.867      210836.386
#Sta/Elev= 30
       0   64.53  506.73   63.56  553.59   60.36  590.73   62.14  881.86   59.01
 1639.62   59.24 2253.41   55.07  2264.2   57.13 2317.41   55.35 2438.59   57.11
 3093.59   53.24 3355.03   55.68 3601.49   49.09 3638.52   51.22 3697.91   47.65
 4076.35   47.52 4095.52   41.98 4114.25   41.73 4115.96   47.37  5478.1   48.21
 6791.82   59.87 6977.75   55.95  6991.8    51.9 7015.53    54.2 7335.29   56.85
 7357.28   55.06 7442.53   58.52 7918.71   56.84 7934.17   59.24 8086.37   59.53
#Mann= 3 , 0 , 0
       0     .08       0 4076.35     .06       0 4115.96     .08       0
#XS Ineff= 2 , 0
         3628.94   60.84 5075.85           60.89
Permanent Ineff=
       F       F
Bank Sta=4076.35,4115.96
XS Rating Curve= 0
Exp/Cntr=.3,.1

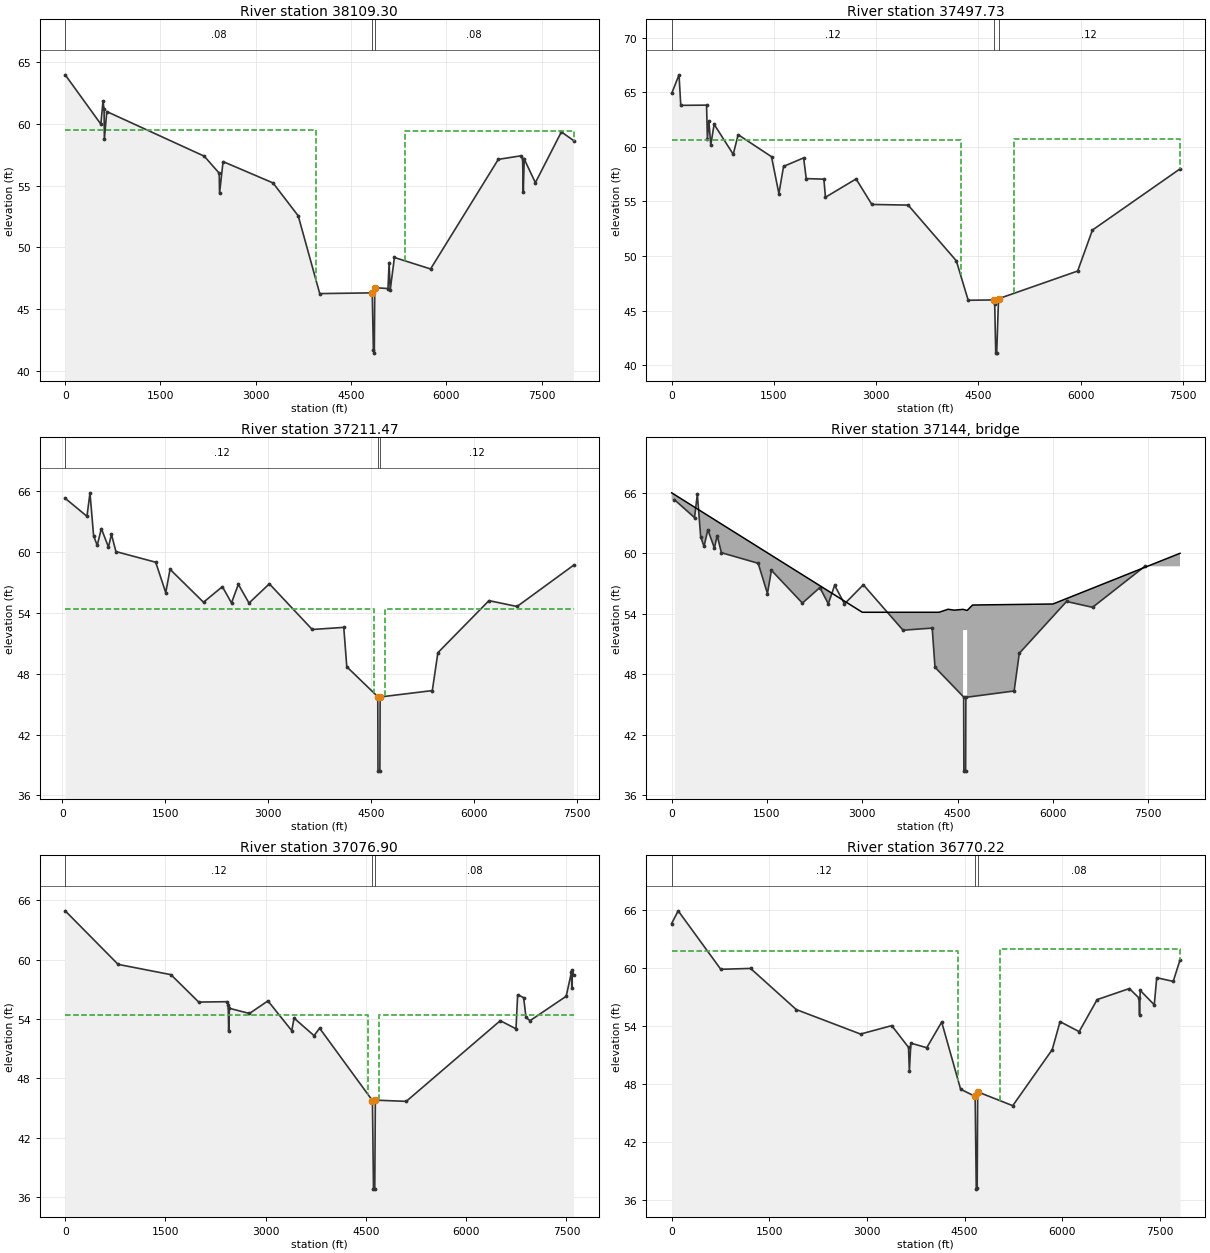
Type RM Length L Ch R = 1 ,38109.30,510.41,611.57,831.01
XS GIS Cut Line= 5
     2128942.834       209039.41     2126457.952      209081.526
     2125306.764      209193.837      2123860.76      209516.731
     2121067.022      210218.676
#Sta/Elev= 30
       0   63.99  561.27   59.99  594.98   61.86  612.12   61.19  616.69   58.75
  654.49   61.01 2189.55   57.39 2424.95   56.01 2430.28   54.38 2485.91   56.95
 3272.15   55.22 3668.94   52.55 4007.84   46.24 4834.47    46.3 4852.45   41.69
 4867.15   41.41 4874.49   46.72 5082.31   46.65 5100.46   48.76 5117.12   46.51
 5183.83   49.17  5753.1   48.24 6819.31   57.13 7176.21   57.42 7202.21   57.17
  7213.2   54.51 7227.53   57.16 7403.25   55.24 7812.73   59.36 8004.08   58.66
#Mann= 3 , 0 , 0
       0     .08       0 4834.47     .06       0 4874.49     .08       0
#XS Ineff= 2 , 0
         3955.66   59.53 5355.89           59.44
Permanent Ineff=
       F       F
Bank Sta=4834.47,4874.49
XS Rating Curve= 0
Exp/Cntr=.3,.1

Type RM Length L Ch R = 1 ,37497.73,415.17,286.26,185.69
XS GIS Cut Line= 6
     2128901.461       208779.42     2124974.677      208900.244
     2124410.831       209000.93      2124140.19      208802.617
     2123927.534      208739.145     2121551.326      208900.244
#Sta/Elev= 30
       0   64.91  107.79   66.62  133.63   63.82   511.7   63.84  524.45   60.77
  545.54   62.41  573.44   60.18  622.83   62.08  903.32   59.33  975.34   61.13
 1464.78   59.11  1573.2   55.72  1641.4   58.22 1935.83      59 1974.38    57.1
 2232.88   57.05 2256.35   55.39 2705.61   57.07  2936.8   54.73 3469.44   54.67
 4176.23   49.56 4350.47   45.94 4725.67   45.97 4739.57   45.56 4754.46   41.09
 4768.66   41.09 4795.46   46.08 5956.41   48.62 6173.15   52.38 7457.95   57.99
#Mann= 3 , 0 , 0
       0     .12       0 4725.67     .06       0 4795.46     .12       0
#XS Ineff= 2 , 0
         4238.04   60.61 5023.96           60.73
Permanent Ineff=
       F       F
Bank Sta=4725.67,4795.46
XS Rating Curve= 0
Exp/Cntr=.5,.3

Type RM Length L Ch R = 1 ,37211.47,130.44,134.57,149.71
XS GIS Cut Line= 6
     2128794.337       208644.95     2127863.947      208605.776
     2127080.461      208625.363     2124592.892      208595.983
     2124101.601      208634.408     2121400.186      208556.808
#Sta/Elev= 30
      43   65.32  359.92   63.54  403.91   65.86   456.9    61.6  509.46   60.68
  569.33   62.33  672.83   60.51  716.64   61.76  781.88   60.06 1360.88   59.01
 1507.28   56.01 1570.06   58.31 2057.66   55.06 2331.99    56.6 2465.24   54.99
 2564.64   56.83 2719.87   54.98 3016.39   56.88 3640.92   52.37 4100.15   52.58
 4144.31   48.69  4595.6   45.74 4598.54   38.39 4626.16   38.39 4629.97   45.71
 5389.81   46.34 5470.97   50.08 6214.78   55.22 6624.21   54.64 7446.66   58.71
#Mann= 3 , 0 , 0
      43     .12       0  4595.6     .06       0 4629.97     .12       0
#XS Ineff= 2 , 0
       0    4539    54.4    4697       0    54.4
Permanent Ineff=
       F       F
Bank Sta=4595.6,4629.97
XS Rating Curve= 0
Exp/Cntr=.5,.3

Type RM Length L Ch R = 3 ,37144   ,,,
BEGIN DESCRIPTION:
39512  Bridge - Structure #70
END DESCRIPTION:
Bridge Culvert--1,0,-1,-1, 0
Deck Dist Width WeirC Skew NumUp NumDn MinLoCord MaxHiCord MaxSubmerge Is_Ogee
48,34,2.6,0, 12, 12, 54.4, , .95, 0, 0,0,,
       0    3000 4207.49  4349.9 4447.08    4586    4586    4650    4650  4735.7
    6000    8000
      66   54.15   54.15   54.45   54.36   54.44   54.44   54.33   54.33   54.87
   54.97      60
      45      45      45      45      45      45   52.39   52.39      43      45
      45      45
       0    3000 4207.49  4349.9 4447.08    4586    4586    4650    4650  4735.7
    6000    8000
      66   54.15   54.15   54.45   54.36   54.44   54.44   54.33   54.33   54.87
   54.97      60
      45      45      45      45      45      45   52.39   52.39      43      45
      45      45
BR Coef=-1 , 1 , 0 ,, 0 ,,,.8,0,1.2,0,
WSPro=,,,, 1 ,,,, 0 ,,,, 0 ,,,,-1 ,-1 ,-1 , 0 , 0 , 0 , 0 , 0
BR U #Sta/Elev= 30
      43   65.32  359.92   63.54  403.91   65.86   456.9    61.6  509.46   60.68
  569.33   62.33  672.83   60.51  716.64   61.76  781.88   60.06 1360.88   59.01
 1507.28   56.01 1570.06   58.31 2057.66   55.06 2331.99    56.6 2465.24   54.99
 2564.64   56.83 2719.87   54.98 3016.39   56.88 3640.92   52.37 4100.15   52.58
 4144.31   48.69  4595.6   45.74 4598.54   38.39 4626.16   38.39 4629.97   45.71
 5389.81   46.34 5470.97   50.08 6214.78   55.22 6624.21   54.64 7446.66   58.71
BR U #Mann= 3
      43     .12  4595.6     .05 4629.97     .12
BR D #Sta/Elev= 30
       0   64.94  791.43   59.53 1581.92   58.49 1997.82   55.72 2422.95   55.76
 2438.75   55.46  2445.8    52.8 2456.92   55.09 2756.79   54.57 3033.48   55.84
 3390.09   52.83 3424.42    54.1 3723.52   52.33 3806.99   53.08 4597.05   45.77
 4612.95   36.82 4632.13   36.82 4640.52   45.81 5103.49   45.69 6509.75   53.84
 6745.13   53.02 6770.15   56.46 6859.55   56.17  6894.8   54.18 6954.77   53.84
 7496.61   56.31 7574.68   58.73 7581.09    57.1 7587.98   58.92 7606.12   58.42
BR D #Mann= 3
       0     .12 4597.05     .05 4640.52     .08
BC Design=,, 0 ,, 0 ,,,,,,

Type RM Length L Ch R = 1 ,37076.90,317.28,306.68,213.36
XS GIS Cut Line= 6
     2128804.131      208527.427     2127364.475      208498.047
     2124426.401      208498.047      2124116.78      208492.111
      2124038.11      208473.899     2121204.314      208458.872
#Sta/Elev= 30
       0   64.94  791.43   59.53 1581.92   58.49 1997.82   55.72 2422.95   55.76
 2438.75   55.46  2445.8    52.8 2456.92   55.09 2756.79   54.57 3033.48   55.84
 3390.09   52.83 3424.42    54.1 3723.52   52.33 3806.99   53.08 4597.05   45.77
 4612.95   36.82 4632.13   36.82 4640.52   45.81 5103.49   45.69 6509.75   53.84
 6745.13   53.02 6770.15   56.46 6859.55   56.17  6894.8   54.18 6954.77   53.84
 7496.61   56.31 7574.68   58.73 7581.09    57.1 7587.98   58.92 7606.12   58.42
#Mann= 3 , 0 , 0
       0     .12       0 4597.05     .06       0 4640.52     .08       0
#XS Ineff= 2 , 0
       0    4534    54.4    4702       0    54.4
Permanent Ineff=
       F       F
Bank Sta=4597.05,4640.52
XS Rating Curve= 0
Exp/Cntr=.5,.3

Type RM Length L Ch R = 1 ,36770.22,397.87,436.51,320.62
XS GIS Cut Line= 6
     2128823.718      208331.556     2126130.484      208116.097
     2124514.544      208135.684     2124083.626      208204.239
     2123828.993      208351.143     2121106.379      208331.556
#Sta/Elev= 30
       0   64.57  100.05   65.88  754.56   59.84 1212.43   59.93 1914.46   55.68
 2902.25   53.15 3381.66   54.02 3639.06   51.78  3652.6   49.31 3675.27   52.21
 3919.31   51.74 4149.16   54.39 4439.74   47.45  4663.1   46.71 4680.53   37.13
 4694.25   37.27 4702.16   47.18 5240.68   45.75  5847.4   51.54 5967.95   54.43
 6261.33    53.4  6537.8   56.71 7032.66   57.85 7180.19   56.88 7189.17   55.13
 7199.75   57.66 7415.61   56.17 7453.25   58.97 7706.38   58.59 7810.89    60.8
#Mann= 3 , 0 , 0
       0     .12       0  4663.1     .06       0 4702.16     .08       0
#XS Ineff= 2 , 0
         4406.07   61.71 5044.14           61.92
Permanent Ineff=
       F       F
Bank Sta=4663.1,4702.16
XS Rating Curve= 0
Exp/Cntr=.3,.1

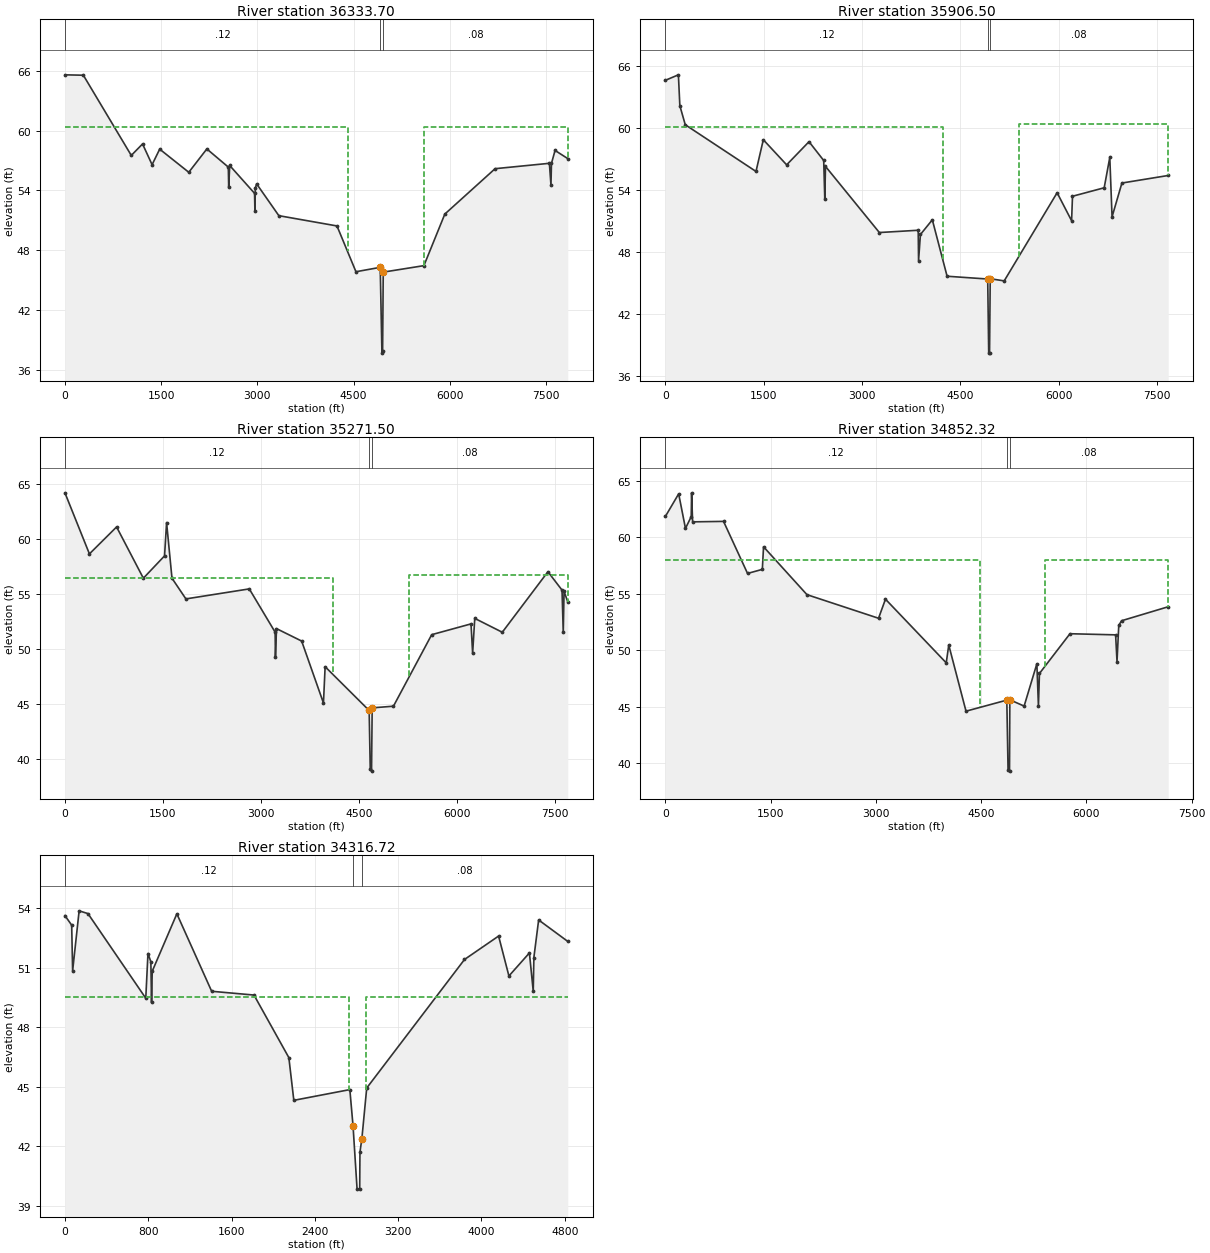
Type RM Length L Ch R = 1 ,36333.70,254.23,427.2,552.19
XS GIS Cut Line= 6
     2128916.757      208037.749     2125430.243      207665.593
     2124705.518      207646.005     2124000.381      207900.638
     2123863.271      208067.129     2121233.695      208008.368
#Sta/Elev= 30
       0   65.59  287.14   65.55 1034.44   57.51 1210.24   58.66 1359.08   56.58
 1477.44   58.14 1931.14   55.82 2212.78   58.16 2547.45   56.34 2553.68   54.32
 2569.15    56.5 2956.76   53.71 2962.33   51.93 2968.72   54.24 2988.75   54.66
 3335.53   51.47 4241.84   50.44 4537.69   45.85 4916.19   46.29 4942.96   37.69
 4953.31   37.94 4963.23   45.81 5597.33   46.46 5923.55   51.63 6707.26   56.18
 7553.93   56.72 7578.56   54.54 7586.29   56.71 7642.45   58.01 7840.81   57.19
#Mann= 3 , 0 , 0
       0     .12       0 4916.19     .06       0 4963.23     .08       0
#XS Ineff= 2 , 0
         4406.07   60.32  5591.6           60.32
Permanent Ineff=
       F       F
Bank Sta=4916.19,4963.23
XS Rating Curve= 0
Exp/Cntr=.3,.1

Type RM Length L Ch R = 1 ,35906.50,484.79,635,638.18
XS GIS Cut Line= 4
      2128789.44      207797.806     2126164.193      207452.168
     2125537.973      207464.824     2121145.553      207636.212
#Sta/Elev= 30
       0   64.58  198.46   65.11  220.74   62.12  303.24   60.28 1382.21   55.76
 1493.76   58.83 1849.74    56.4  2190.8   58.64 2415.08   56.82 2431.48   53.09
 2442.07   56.25 3263.71   49.85 3856.49   50.07 3861.83   47.14 3890.35   49.66
 4071.76   51.08 4297.11   45.62 4916.48   45.35  4931.7   38.18 4944.53   38.18
 4954.83   45.38 5168.09   45.17 5975.18    53.7 6196.01   50.99 6209.74   53.36
 6693.26   54.18  6778.6   57.12 6813.34   51.37 6963.53   54.64 7670.02   55.37
#Mann= 3 , 0 , 0
       0     .12       0 4916.48     .06       0 4954.83     .08       0
#XS Ineff= 2 , 0
         4238.04   60.06 5386.23           60.32
Permanent Ineff=
       F       F
Bank Sta=4916.48,4954.83
XS Rating Curve= 0
Exp/Cntr=.3,.1

Type RM Length L Ch R = 1 ,35271.50,487.68,419.18,285.52
XS GIS Cut Line= 6
     2128720.885       207410.96     2126301.872      207009.423
      2124215.84      207048.597     2123814.303      206921.281
     2121968.213      207469.721     2121184.727      207371.785
#Sta/Elev= 30
       0   64.22  374.95   58.67  790.96   61.12 1200.78   56.46 1525.21   58.49
 1556.44   61.52 1639.06   56.46 1852.25   54.58 2822.79   55.49  3218.3   51.56
 3223.42   49.31 3239.42   51.88 3624.59   50.75 3958.41   45.12 3984.06   48.42
 4658.29   44.44 4674.68   39.16 4694.68   38.93 4704.49   44.68 5030.09   44.83
 5615.85   51.33 6218.08   52.31 6242.56   49.63 6275.17   52.81 6696.65   51.55
 7395.47   57.05 7611.49   55.38 7630.31   51.54 7642.52   55.26 7699.65   54.31
#Mann= 3 , 0 , 0
       0     .12       0 4658.29     .06       0 4704.49     .08       0
#XS Ineff= 2 , 0
         4107.35   56.48 5274.21           56.75
Permanent Ineff=
       F       F
Bank Sta=4658.29,4704.49
XS Rating Curve= 0
Exp/Cntr=.3,.1

Type RM Length L Ch R = 1 ,34852.32,642.22,535.6,552.57
XS GIS Cut Line= 6
     2128882.433      207230.243     2126891.702      206787.859
     2124424.557      206549.652     2123607.847       206685.77
     2122774.123      207162.184     2121957.413      207366.362
#Sta/Elev= 30
       0   61.84  189.42   63.84   286.2   60.78  368.27   61.82  373.69   63.93
  388.07   61.36   828.9    61.4 1170.97   56.79 1381.73   57.15 1398.95   59.15
 2017.62   54.91 3037.88   52.82  3136.4   54.51 4002.49   48.87 4038.34   50.45
 4284.32   44.59 4865.75   45.57 4883.36   39.42  4904.2   39.28 4908.74    45.6
 5112.39   45.04 5294.04   48.79  5316.3   45.05 5330.74   47.93 5766.04   51.45
 6416.25   51.35 6436.09   48.99 6461.29   52.19 6501.11    52.6 7166.05   53.84
#Mann= 3 , 0 , 0
       0     .12       0 4865.75     .06       0 4908.74     .08       0
#XS Ineff= 2 , 0
         4479.19   58.02  5404.9              58
Permanent Ineff=
       F       F
Bank Sta=4865.75,4908.74
XS Rating Curve= 0
Exp/Cntr=.5,.3

Type RM Length L Ch R = 1 ,34316.72,120.24,121.22,120.86
XS GIS Cut Line= 6
     2126483.347      205001.306     2125190.223      205818.016
     2123863.152      206101.112     2123335.611      206498.607
     2122672.034      207145.169     2122331.738      207213.229
#Sta/Elev= 30
       0   53.62   64.77   53.14    73.9   50.84  136.28   53.86   221.3   53.72
  776.35   49.46  797.33   51.71  825.06    51.3  831.72   49.25   838.4   50.82
 1074.89   53.71 1409.07   49.81 1815.67   49.62 2150.37   46.47 2198.12   44.32
 2736.06   44.86    2767   43.02 2805.54   39.85 2830.75   39.85 2833.11   41.71
 2851.57   42.39 2898.12   44.94 3837.12   51.41 4164.62   52.59 4263.71   50.58
 4460.53   51.74 4497.35   49.81 4503.38   51.51  4549.2    53.4 4829.05   52.32
#Mann= 3 , 0 , 0
       0     .12       0    2767     .06       0 2851.57     .08       0
#XS Ineff= 2 , 0
       0    2724   49.54    2896       0   49.54
Permanent Ineff=
       F       F
Bank Sta=2767,2851.57
XS Rating Curve= 0
Exp/Cntr=.5,.3