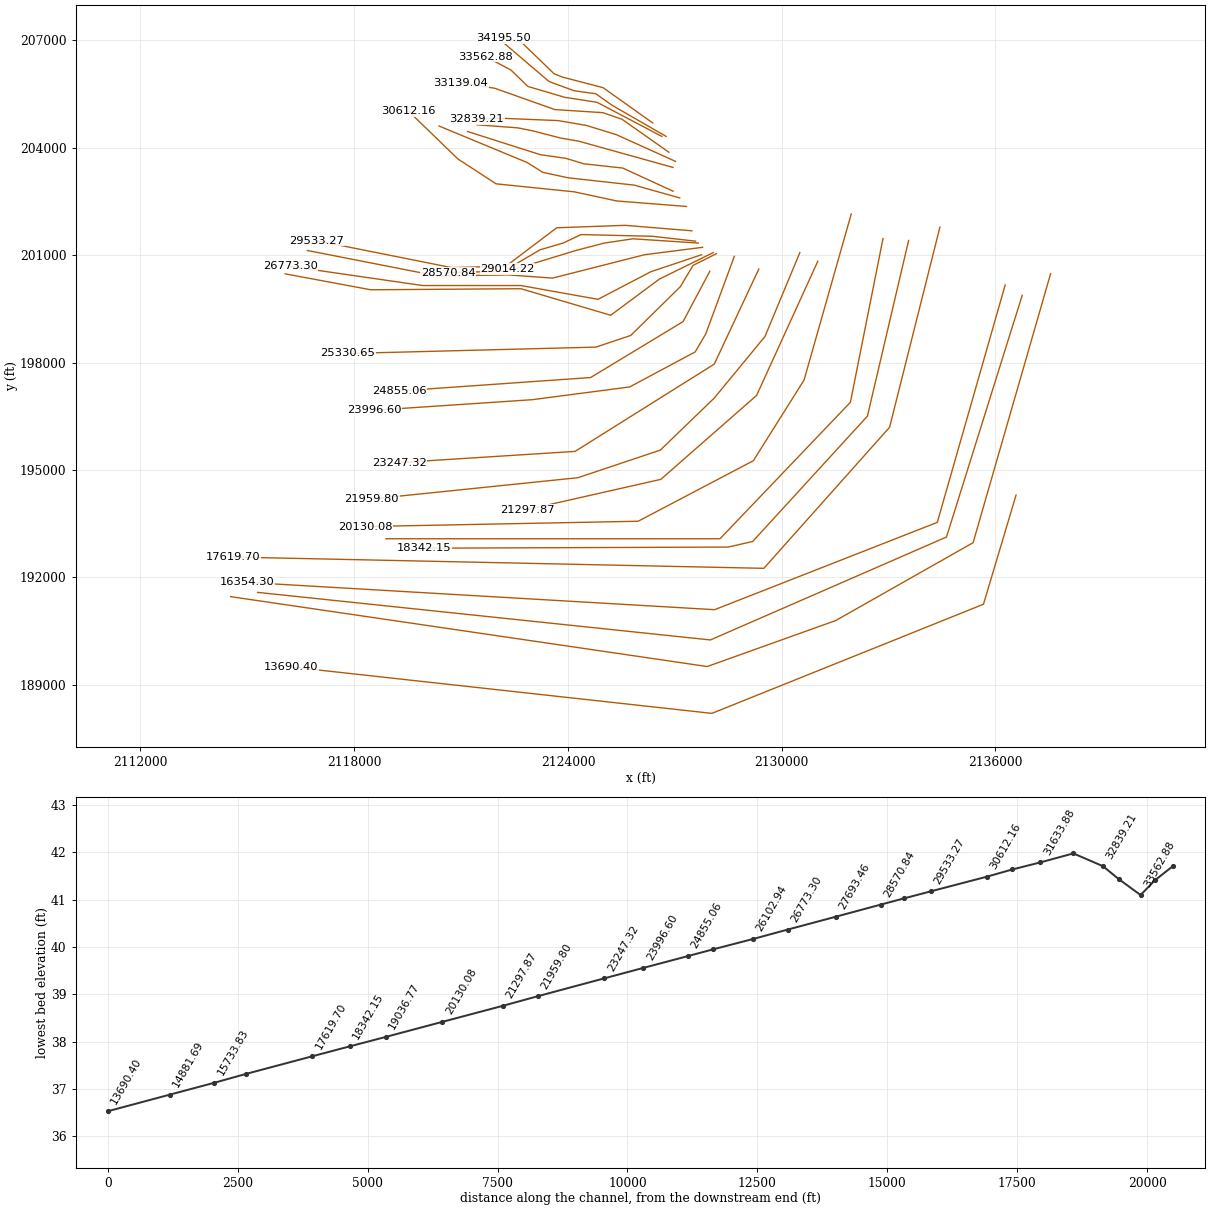
HEC-RAS study bogue.prj: NCFM-Bogue Swamp - Detailed Study

--- bogue.g01 (geometry) --- (continued)

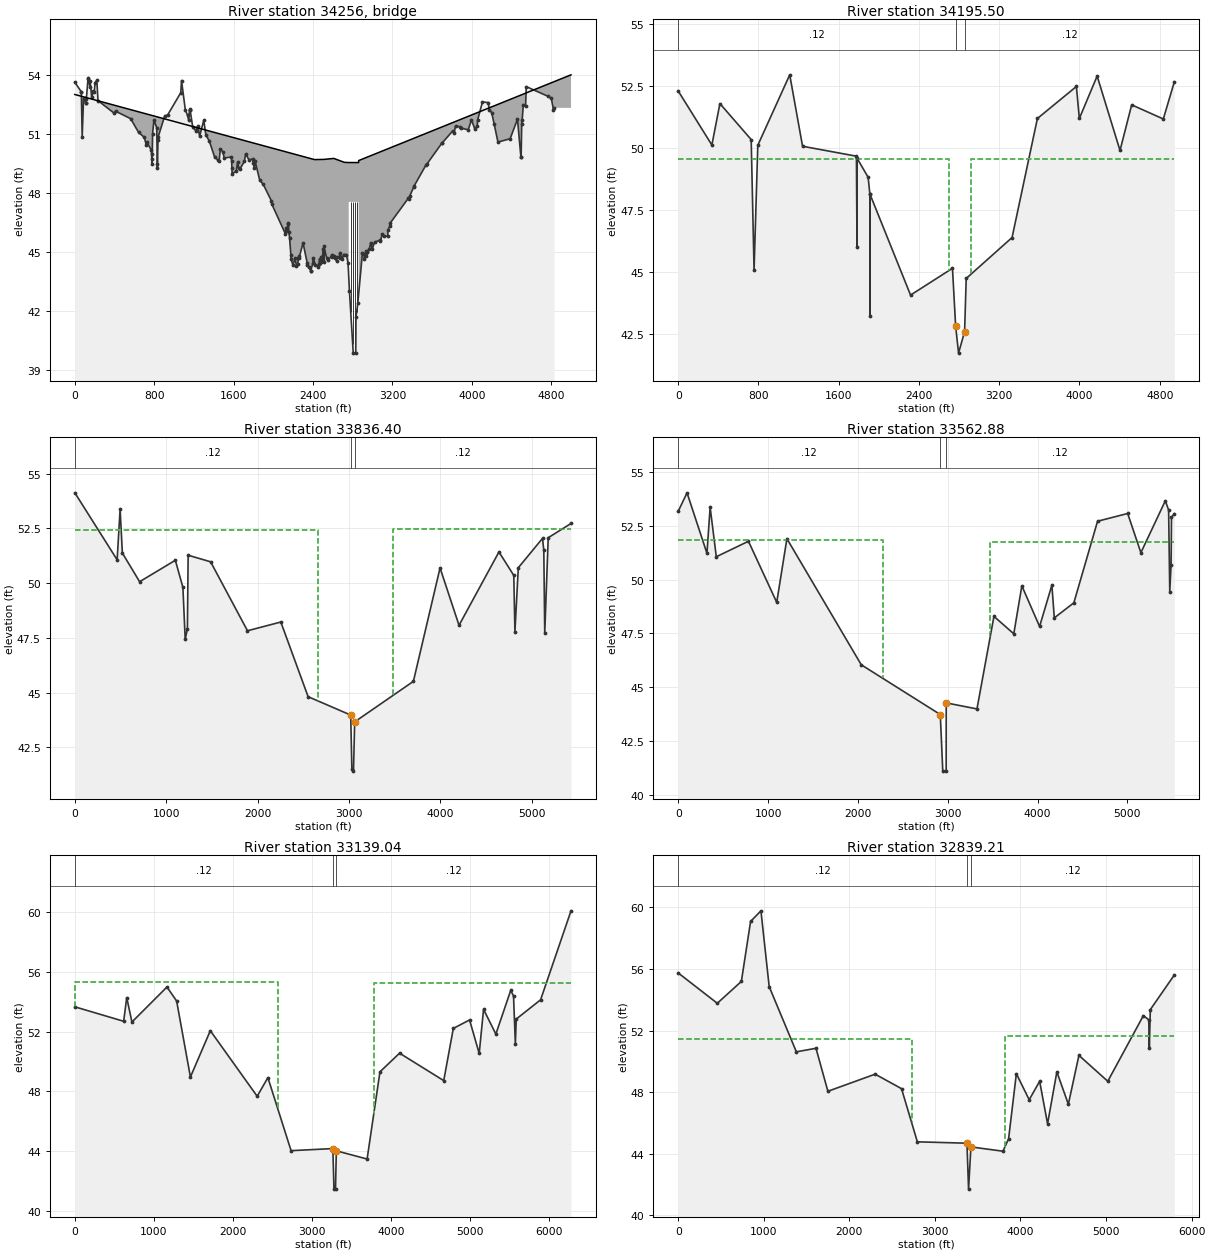
Type RM Length L Ch R = 3 ,34256   ,,,
BEGIN DESCRIPTION:
36382.5  Bridge - Structure #69
END DESCRIPTION:
Bridge Culvert--1,0,-1,-1, 0
Deck Dist Width WeirC Skew NumUp NumDn MinLoCord MaxHiCord MaxSubmerge Is_Ogee
36,25,2.6,0, 10, 10, , , .95, 0, 0,0,,
       0 2415.11 2510.45 2609.23  2716.2    2760    2760    2860    2860    5000
      53   49.69    49.7   49.75   49.55   49.54   49.54   49.54   49.64      54
                                                   47.54   47.54
       0 2415.11 2510.45 2609.23  2716.2    2760    2760    2860    2860    5000
      53   49.69    49.7   49.75   49.55   49.54   49.54   49.54   49.64      54
                                                   47.54   47.54
Pier Skew, UpSta & Num, DnSta & Num=  ,2780, 2 ,2780, 2 , 0 , 0 , 0 ,,
       2       2
   39.85   47.54
       2       2
   39.85   47.54
Pier Skew, UpSta & Num, DnSta & Num=  ,2800, 2 ,2800, 2 , 0 , 0 , 0 ,,
       2       2
   39.85   47.54
       2       2
   39.85   47.54
Pier Skew, UpSta & Num, DnSta & Num=  ,2820, 2 ,2820, 2 , 0 , 0 , 0 ,,
       2       2
   39.85   47.54
       2       2
   39.85   47.54
Pier Skew, UpSta & Num, DnSta & Num=  ,2840, 2 ,2840, 2 , 0 , 0 , 0 ,,
       2       2
   39.85   47.54
       2       2
   39.85   47.54
BR Coef=-1 , 1 , 0 ,, 0 ,,,.8,0,1.2,0,
WSPro=,,,, 1 ,,,, 0 ,,,, 0 ,,,,-1 ,-1 ,-1 , 0 , 0 , 0 , 0 , 0
BR U #Sta/Elev= 195
       0   53.62   64.77   53.14   65.27   53.12    73.9   50.84    87.7   52.78
  101.47   52.81  107.51   52.55  108.34   52.55  116.32   52.79  132.24   53.78
  136.28   53.86  151.42    53.4  154.86   53.67  169.59   52.85  187.01   53.17
  196.94   53.12  202.96    53.6   221.3   53.72  233.22   52.69  395.75   52.05
   410.3   52.15  562.25   51.77   642.6   51.07  700.19   50.82  719.43   50.43
  724.87   50.58  769.92   50.18  773.71   49.95  776.35   49.46  779.41   49.74
  783.62   51.01  797.33   51.71  825.06    51.3  831.72   49.25  832.82   49.45
  837.66   50.67   838.4   50.82  906.24   51.92  933.98   51.95 1067.31   53.09
 1074.89   53.71 1112.96   52.23 1135.42   51.94 1147.79   51.68 1155.58   52.21
 1161.47   52.24 1162.21   52.19 1188.32   51.33 1221.48   51.14 1237.99    51.4
 1257.36   50.88 1299.05   51.69 1320.28   50.94 1354.33   50.64 1409.07   49.81
 1445.98   49.65 1453.71    49.6 1467.04   50.24  1493.3   50.06  1504.6   49.77
 1575.59   49.82 1579.93   49.63 1582.06   49.28 1584.82   48.97 1626.91    49.1
 1639.86   49.56  1650.7   49.25 1662.57    49.2 1708.75    49.6  1721.3   49.98
 1755.11   49.67 1790.78   49.72 1796.17   49.54 1808.09   49.26 1815.67   49.62
 1863.27   48.64 1898.41   48.43 1980.96   47.59  1985.1   47.42 2120.36   45.93
 2128.99   46.19 2135.87   46.05 2150.37   46.47 2152.68   46.39 2156.26   46.03
 2163.67   45.72 2177.16   44.82 2178.68   44.64 2198.12   44.32 2219.59   44.67
 2233.25   44.27  2247.2   44.39 2251.91   44.68  2258.6   44.79 2260.77   44.71
  2299.6   45.45 2342.43   44.41 2343.77   44.33 2355.12   44.23 2377.71   44.04
 2377.98   44.05 2397.81   44.41 2401.48   44.67 2423.33   44.35    2455   44.24
  2457.7   44.36 2462.82   44.38 2466.59   44.64 2471.06   44.44 2471.74   44.54
 2475.59    44.5 2478.54   44.62 2479.71   44.72 2497.37    44.6  2500.8   44.86
  2502.3   45.13 2508.53   44.48 2508.96    45.3 2536.97   44.69 2554.04   44.56
 2593.86   44.86 2593.86   44.76 2610.92   44.81  2622.3   44.69 2639.36   44.51
 2639.36   44.74  2667.8   44.69  2667.8   44.94 2696.25   44.63 2707.62   44.86
 2736.06   44.86 2753.13   44.43    2767   43.02 2805.54   39.85 2830.75   39.85
 2833.11   41.71 2851.57   42.39 2898.12   44.94 2913.54   44.88 2916.63   44.66
 2929.12    44.8 2931.24   44.93 2937.27   45.03 2945.59   44.98 2946.49   45.01
 2967.88   45.15 2981.99   45.47 2995.34   45.13 3021.39   45.49  3077.5    45.6
  3078.6   45.56 3100.25    45.9 3112.36   45.78 3153.61    45.8 3155.36   46.11
 3176.45   46.32 3180.74   46.48 3359.98   47.72 3371.18   47.68 3374.69   47.84
 3416.24    48.3  3416.9   48.33 3536.91    49.4 3551.66   49.49 3702.28   50.55
 3702.62   50.54 3808.16   51.15 3821.76   51.05 3837.12   51.41 3885.14   51.35
 3889.73    51.3 3963.95    51.2 3997.14   51.71 4029.95   51.25 4054.88   51.39
  4059.2   51.71 4107.62   52.62 4164.62   52.59 4178.25   52.22 4200.25   52.08
 4225.42    51.5 4263.71   50.58 4386.42   50.75 4460.53   51.74 4495.26   49.81
 4497.35   49.81 4503.38   51.51 4508.13   51.72 4519.44   52.45 4542.37   52.43
  4549.2    53.4 4766.76   52.91 4800.68   52.81 4823.43   52.23 4829.05   52.32
BR U #Mann= 3
       0     .12    2767     .05 2851.57     .08
BR D #Sta/Elev= 30
       0   52.29  335.73   50.11   415.9   51.78  727.69   50.33  756.37   45.07
  793.59    50.1 1111.87   52.94 1239.69   50.06 1776.55   49.66 1782.41      46
 1784.22   49.57 1893.32   48.81  1910.2   48.15 1911.76   43.22 1912.42   48.12
 2316.28   44.06    2734   45.14 2765.79    42.8 2794.63   41.72 2854.93   42.59
 2870.83   44.73 3328.02   46.38 3580.62   51.18 3969.23   52.47 3998.54   51.18
 4175.97   52.89 4404.03   49.89 4520.21   51.73 4835.63   51.16  4945.6   52.66
BR D #Mann= 3
       0     .12 2765.79     .05 2854.93     .12
BC Design=,, 0 ,, 0 ,,4,2780,2780,20,2

Type RM Length L Ch R = 1 ,34195.50,432.27,359.1,255.3
XS GIS Cut Line= 6
     2126381.258      204695.039     2124986.046      205681.897
     2123844.942      205977.578     2123607.847      206073.237
     2122689.049      206958.007     2122178.605      207060.095
#Sta/Elev= 30
       0   52.29  335.73   50.11   415.9   51.78  727.69   50.33  756.37   45.07
  793.59    50.1 1111.87   52.94 1239.69   50.06 1776.55   49.66 1782.41      46
 1784.22   49.57 1893.32   48.81  1910.2   48.15 1911.76   43.22 1912.42   48.12
 2316.28   44.06    2734   45.14 2765.79    42.8 2794.63   41.72 2854.93   42.59
 2870.83   44.73 3328.02   46.38 3580.62   51.18 3969.23   52.47 3998.54   51.18
 4175.97   52.89 4404.03   49.89 4520.21   51.73 4835.63   51.16  4945.6   52.66
#Mann= 3 , 0 , 0
       0     .12       0 2765.79     .06       0 2854.93     .12       0
#XS Ineff= 2 , 0
       0    2699   49.54    2921       0   49.54
Permanent Ineff=
       F       F
Bank Sta=2765.79,2854.93
XS Rating Curve= 0
Exp/Cntr=.5,.3

Type RM Length L Ch R = 1 ,33836.40,223.72,273.51,274.2
XS GIS Cut Line= 6
     2126755.584      204320.714     2125241.267      205188.468
     2124781.868      205511.749     2124169.336      205596.823
     2123471.729      205852.045     2122127.561      206992.036
#Sta/Elev= 30
       0   54.12  462.98   51.06  495.54   53.37  520.13   51.37  709.11   50.06
 1100.12   51.04 1182.92    49.8 1208.03   47.43 1232.15    47.9  1240.2   51.27
 1486.06   50.97 1889.92   47.82 2254.75   48.22 2553.48   44.81  3019.9   43.97
 3032.64   41.49 3050.29   41.41 3063.35   43.66    3706   45.51 3997.85   50.69
 4205.64   48.07 4642.61   51.42 4804.96   50.35 4817.53   47.78 4854.59    50.7
 5119.56   52.04 5133.59    51.5 5143.89   47.72 5182.06   52.07 5431.47   52.72
#Mann= 3 , 0 , 0
       0     .12       0  3019.9     .06       0 3063.35     .12       0
#XS Ineff= 2 , 0
          2663.3   52.42 3488.02           52.45
Permanent Ineff=
       F       F
Bank Sta=3019.9,3063.35
XS Rating Curve= 0
Exp/Cntr=.3,.1

Type RM Length L Ch R = 1 ,33562.88,370.53,423.84,416.07
XS GIS Cut Line= 6
      2126636.48      204320.714     2124815.898      205273.542
     2123910.795      205412.637     2122876.211      205715.927
     2122399.797      206175.326     2121685.176      206549.652
#Sta/Elev= 30
       0   53.17   98.49   54.03   320.2   51.22  355.64   53.36  424.18   51.06
  782.13   51.78 1096.84   48.94 1210.03    51.9  2037.9   46.04 2917.35   43.73
 2945.01    41.1 2982.78    41.1 2983.34   44.27 3325.54   43.99 3514.65   48.29
 3735.48   47.48 3825.08   49.71 4022.54   47.82 4159.44   49.74 4186.39   48.22
 4403.95   48.92 4667.73   52.71 5003.01   53.07 5150.03   51.25 5422.15   53.66
 5458.72   53.23 5471.36   49.44 5486.04   50.66 5490.54   52.89  5522.5   53.06
#Mann= 3 , 0 , 0
       0     .12       0 2917.35     .06       0 2983.34     .12       0
#XS Ineff= 2 , 0
         2275.38   51.86 3472.58           51.75
Permanent Ineff=
       F       F
Bank Sta=2917.35,2983.34
XS Rating Curve= 0
Exp/Cntr=.3,.1

Type RM Length L Ch R = 1 ,33139.04,319.3,299.84,327.86
XS GIS Cut Line= 6
      2126832.15      203878.329     2125522.011      204797.128
     2124977.538      204984.291      2123633.37      205069.365
     2121948.905      205664.882     2120996.077      205818.016
#Sta/Elev= 30
       0   53.67     618    52.7  656.71   54.29  722.64   52.65 1166.19      55
 1288.59   54.06 1462.97   48.96 1714.91   52.07 2308.18   47.67 2443.83   48.92
 2737.29   44.02  3266.2   44.16 3280.26   41.46  3299.8   41.44 3310.17   44.01
 3699.88   43.46 3862.62   49.31 4110.66   50.56 4669.88   48.72 4791.27   52.22
 4996.94   52.79 5118.83   50.54 5174.04    53.5 5329.77   51.84 5518.39   54.78
  5553.5   54.39 5576.72   51.17 5587.95   52.85 5896.03   54.14 6281.15   60.11
#Mann= 3 , 0 , 0
       0     .12       0  3266.2     .06       0 3310.17     .12       0
#XS Ineff= 2 , 0
         2572.93   55.33  3781.8           55.28
Permanent Ineff=
       F       F
Bank Sta=3266.2,3310.17
XS Rating Curve= 0
Exp/Cntr=.3,.1

Type RM Length L Ch R = 1 ,32839.21,468.1,569.51,413.05
XS GIS Cut Line= 6
     2127019.313      203623.107     2125351.864      204371.758
     2124518.139       204626.98     2123718.444      204763.099
     2122033.979      204831.158     2121438.461      204797.128
#Sta/Elev= 30
       0   55.74  457.02   53.77  738.33   55.19  845.92   59.08  967.06   59.77
 1063.43   54.85 1380.76   50.62 1610.26   50.85 1749.27   48.06 2301.55   49.17
 2609.64   48.23 2794.85   44.78 3374.31   44.69 3393.16   41.71 3420.69   44.45
 3794.98   44.17 3861.04   44.98 3951.55    49.2 4101.76   47.51  4223.8   48.71
 4316.41   45.95 4424.88   49.32  4559.2   47.22 4682.71   50.39 5019.89   48.71
 5435.83   52.97 5498.75    52.7 5505.48   50.89    5517   53.36 5797.79   55.61
#Mann= 3 , 0 , 0
       0     .12       0 3374.31     .06       0 3420.69     .12       0
#XS Ineff= 2 , 0
         2730.46   51.43 3815.64           51.65
Permanent Ineff=
       F       F
Bank Sta=3374.31,3420.69
XS Rating Curve= 0
Exp/Cntr=.3,.1

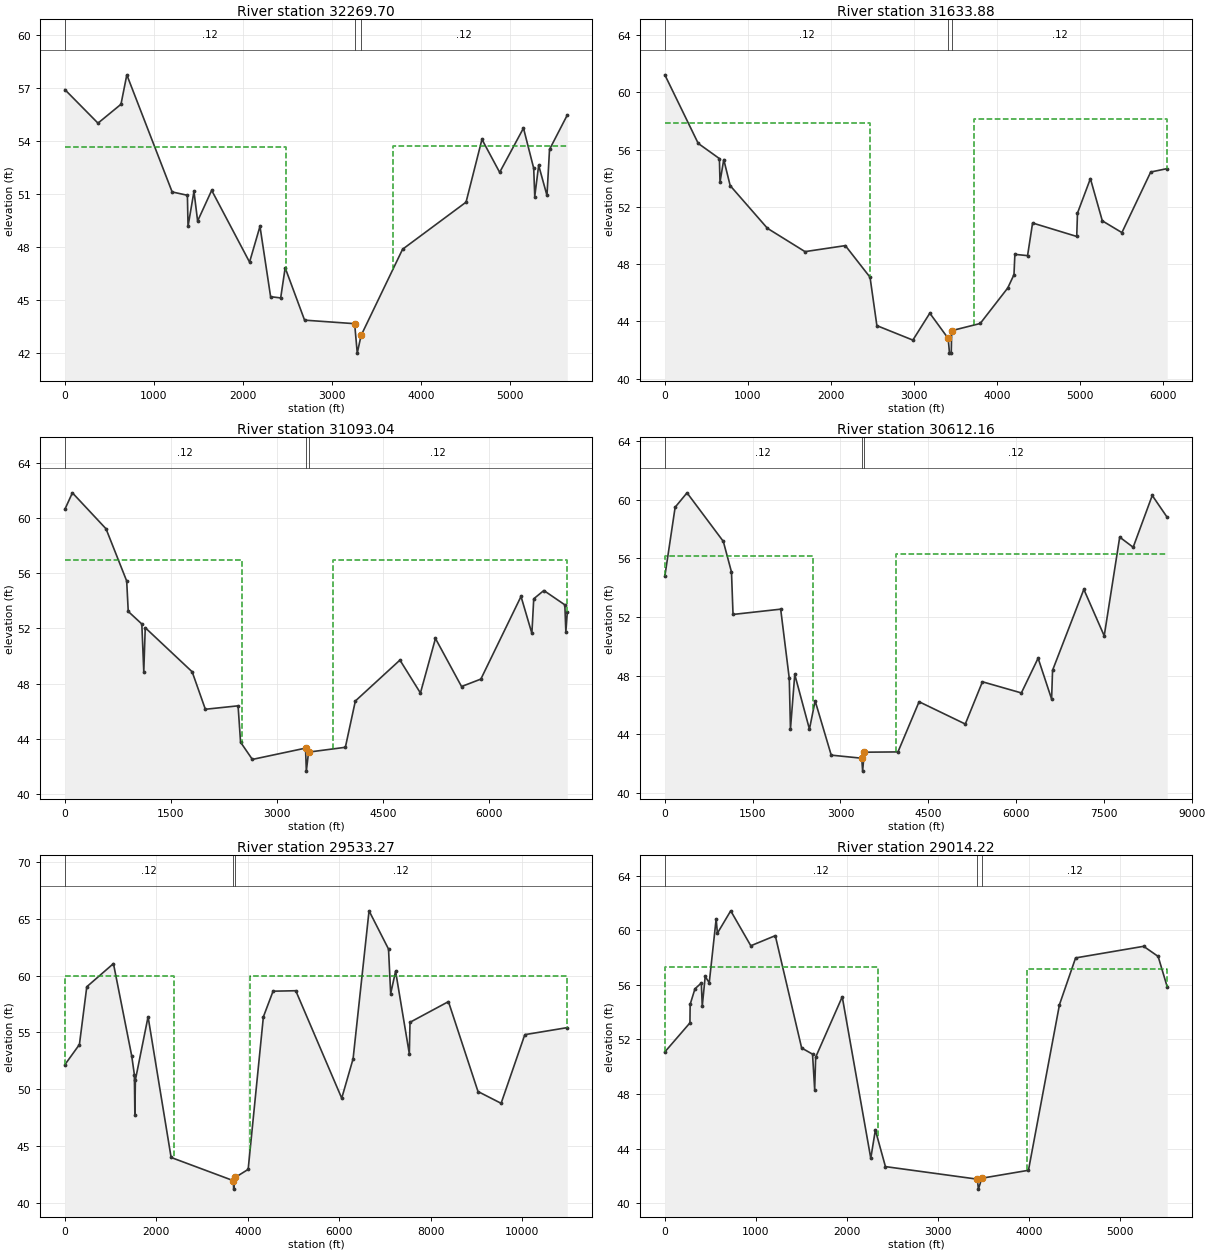
Type RM Length L Ch R = 1 ,32269.70,566.45,635.82,564.67
XS GIS Cut Line= 6
     2126951.254       203452.96     2124313.961      204184.596
     2123794.896      204274.196     2123020.837      204473.847
     2122595.467      204558.921     2121455.476      204643.995
#Sta/Elev= 30
       0   56.92  371.42   55.02  629.65   56.09   695.3   57.76 1204.26   51.12
 1375.67   50.93 1382.66   49.17 1449.37   51.15 1490.43   49.47 1648.26   51.21
 2073.71   47.14 2190.68   49.17 2310.02   45.18 2423.23   45.11 2473.51   46.82
 2691.53   43.85 3253.71   43.65 3283.15   41.98 3326.09   42.98 3792.09   47.87
  4504.9   50.54 4683.45    54.1 4882.34   52.23 5149.84   54.74 5264.72   52.46
 5276.45   50.86 5320.24   52.63 5413.69   50.92 5442.36   53.53 5641.78   55.48
#Mann= 3 , 0 , 0
       0     .12       0 3253.71     .06       0 3326.09     .12       0
#XS Ineff= 2 , 0
         2485.41   53.67 3682.61           53.74
Permanent Ineff=
       F       F
Bank Sta=3253.71,3326.09
XS Rating Curve= 0
Exp/Cntr=.3,.1

Type RM Length L Ch R = 1 ,31633.88,522.56,540.84,505.42
XS GIS Cut Line= 6
     2126951.254      202789.383     2125539.026      203435.945
      2124450.08      203555.048     2123939.636      203708.181
     2123225.015       203810.27      2121183.24      204456.832
#Sta/Elev= 30
       0   61.23  401.84   56.44  656.79   55.38  664.15   53.74  709.32   55.31
   786.7   53.49 1234.77   50.51 1687.28   48.88 2173.02    49.3 2470.19   47.09
 2552.54   43.71 2985.63    42.7 3189.69   44.58 3410.64   42.82 3426.63   41.79
 3447.67   41.79 3452.97   43.36 3796.31   43.86 4127.82   46.34 4202.83   47.27
 4213.69   48.69  4366.3    48.6  4426.8   50.88 4958.06   49.94 4967.19   51.57
 5122.75   53.98 5266.24   51.03 5501.94   50.21 5848.66   54.44 6047.23   54.68
#Mann= 3 , 0 , 0
       0     .12       0 3410.64     .06       0 3452.97     .12       0
#XS Ineff= 2 , 0
         2466.74   57.86 3724.62           58.13
Permanent Ineff=
       F       F
Bank Sta=3410.64,3452.97
XS Rating Curve= 0
Exp/Cntr=.3,.1

Type RM Length L Ch R = 1 ,31093.04,405.04,480.87,474.26
XS GIS Cut Line= 6
     2127138.417       202602.22     2125862.307      202959.531
     2124007.695      203163.708     2123293.074      203316.841
     2122855.663       203590.69     2120383.544      204609.965
#Sta/Elev= 30
       0   60.65  106.11   61.84  582.09   59.23  874.55   55.44   896.7   53.23
 1088.83   52.32 1116.56   48.87 1137.23   52.05 1801.38   48.85 1988.19   46.13
 2451.45   46.38 2486.78   43.74 2653.83   42.49 3406.61   43.31 3417.87   41.64
 3449.29   43.02 3970.28   43.37 4111.69   46.73 4742.83    49.7 5032.88   47.31
 5245.79   51.27 5614.98   47.78 5888.43   48.32    6457   54.32 6610.69   51.64
 6637.09   54.15 6780.25   54.75 7077.25   53.71 7091.64   51.76 7111.93   53.16
#Mann= 3 , 0 , 0
       0     .12       0 3406.61     .06       0 3449.29     .12       0
#XS Ineff= 2 , 0
         2501.75   56.97  3799.3           56.97
Permanent Ineff=
       F       F
Bank Sta=3406.61,3449.29
XS Rating Curve= 0
Exp/Cntr=.3,.1

Type RM Length L Ch R = 1 ,30612.16,979.89,1078.89,1071.49
XS GIS Cut Line= 6
     2127325.579      202364.013     2125368.878      202517.146
     2124177.843      202772.368     2121982.999      202995.692
     2120911.003      203691.167     2119532.805       205018.32
#Sta/Elev= 30
       0   54.77  176.22   59.48  379.12   60.46  998.94   57.15 1138.57   55.06
 1164.86   52.17 1978.87   52.53 2125.33   47.82    2146   44.36 2219.35   48.08
 2470.12   44.35 2567.45   46.28 2842.28   42.58 3363.79   42.37 3378.44   41.49
  3406.7   42.78 3982.34    42.8 4342.92   46.22 5132.17    44.7 5425.09   47.58
 6090.04   46.82 6376.01   49.19 6606.61    46.4 6622.64   48.36 7157.15   53.88
 7505.22   50.71 7769.79   57.44 7999.78   56.75 8325.68   60.28 8581.11   58.79
#Mann= 3 , 0 , 0
       0     .12       0 3363.79     .06       0  3406.7     .12       0
#XS Ineff= 2 , 0
         2532.09   56.16 3955.66           56.27
Permanent Ineff=
       F       F
Bank Sta=3363.79,3406.7
XS Rating Curve= 0
Exp/Cntr=.3,.1

Type RM Length L Ch R = 1 ,29533.27,258.94,519.06,440.16
XS GIS Cut Line= 6
     2127478.713      201683.421     2125607.085      201836.554
     2123684.414      201768.495     2122260.665      200695.034
     2120733.504      200655.368     2116945.352      201409.031
#Sta/Elev= 30
       0   52.15  317.24   53.92  478.22   59.01 1061.19   61.05 1460.34   52.92
 1518.32   51.27 1529.57   47.74  1540.8    50.8 1817.98   56.37 2321.74   43.97
 3679.05   41.93 3690.37   41.18 3722.98   42.21 4006.01   42.92 4338.54   56.36
 4550.56   58.62 5046.69   58.66 6051.35   49.19 6299.77   52.66 6648.74    65.7
 7074.43   62.33 7121.46    58.4 7228.92   60.38 7529.47    53.1 7544.08   55.88
 8384.26    57.7 9030.17   49.78 9535.58   48.7410054.01   54.7910982.25   55.41
#Mann= 3 , 0 , 0
       0     .12       0 3679.05     .06       0 3722.98     .12       0
#XS Ineff= 2 , 0
          2380.4   59.94 4046.67           59.94
Permanent Ineff=
       F       F
Bank Sta=3679.05,3722.98
XS Rating Curve= 0
Exp/Cntr=.3,.1

Type RM Length L Ch R = 1 ,29014.22,392.76,443.38,329.85
XS GIS Cut Line= 6
     2127580.801       201394.17     2126372.751      201530.288
     2124368.966      201578.634     2123864.756      201341.359
     2123212.661      201151.199     2122300.331      200615.701
#Sta/Elev= 30
       0   51.08  275.95   53.21  278.34   54.57  331.35   55.71  400.97   56.13
  411.31   54.44  443.74   56.61  488.09   56.15  564.08   60.83  577.73   59.78
  724.11   61.42  944.93   58.86 1214.02    59.6 1503.57   51.37  1623.3   50.92
 1646.81   48.32 1657.76    50.7 1949.73   55.12 2263.39   43.29 2313.69   45.36
 2424.42   42.68 3434.09   41.76 3446.36   41.03 3483.78   41.83 3996.34   42.41
 4337.21   54.55 4514.23   57.97 5261.88   58.82 5421.34   58.08 5521.04   55.85
#Mann= 3 , 0 , 0
       0     .12       0 3434.09     .06       0 3483.78     .12       0
#XS Ineff= 2 , 0
         2338.39    57.3 3983.66           57.19
Permanent Ineff=
       F       F
Bank Sta=3434.09,3483.78
XS Rating Curve= 0
Exp/Cntr=.3,.1

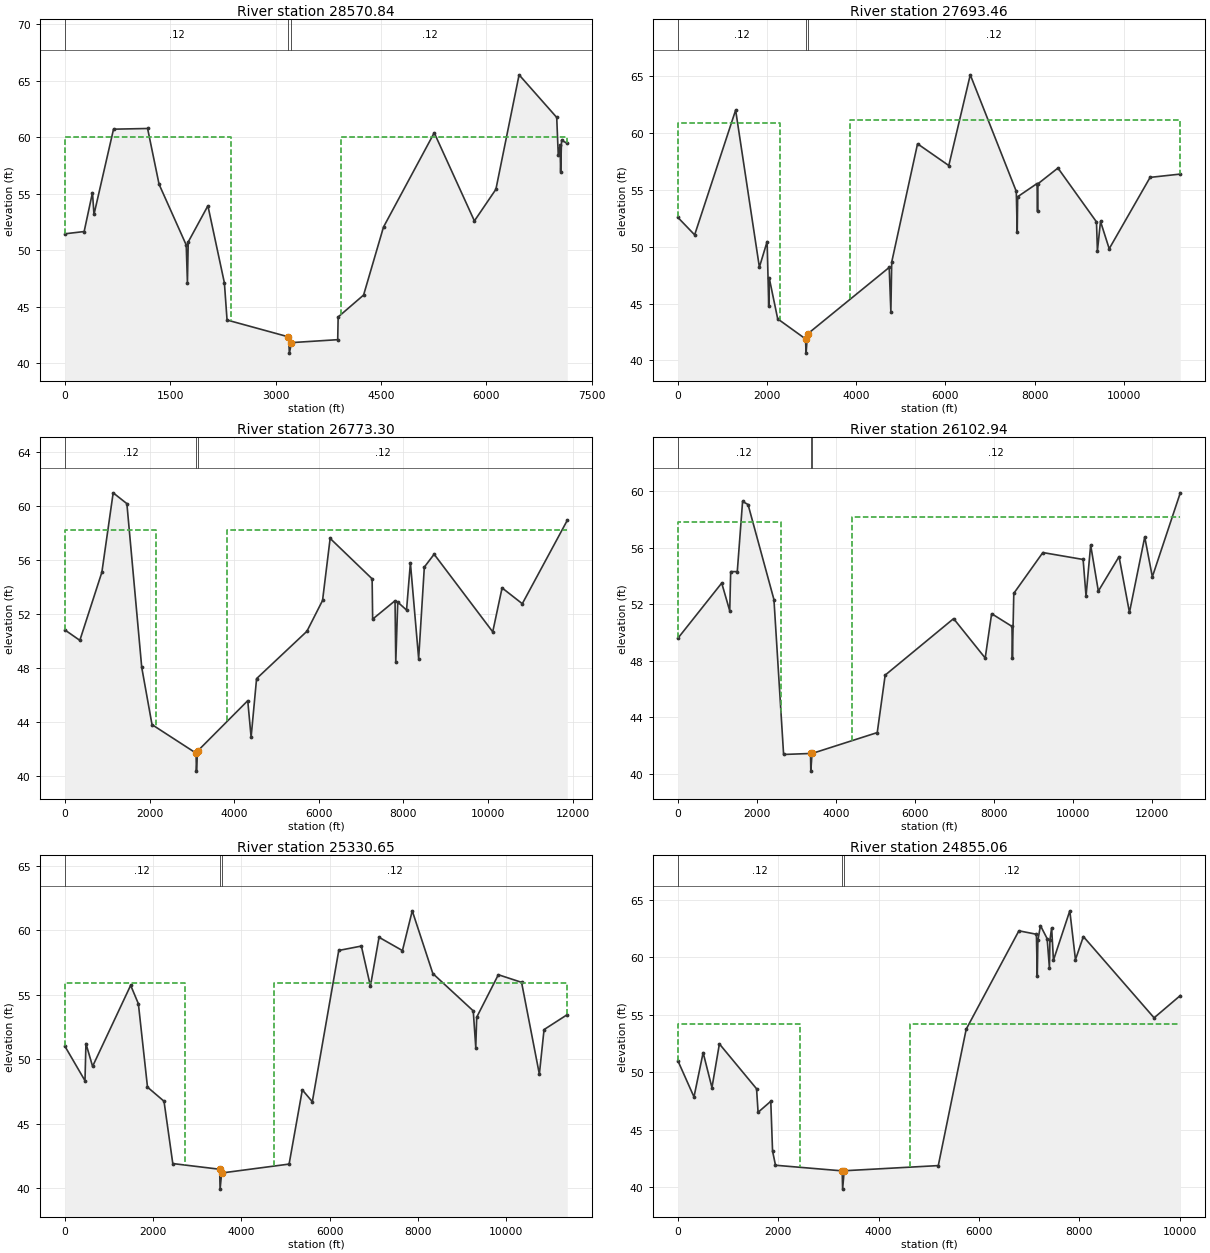
Type RM Length L Ch R = 1 ,28570.84,629.18,877.37,643
XS GIS Cut Line= 6
     2127661.159      201341.359     2125822.276      201459.996
     2125021.473      201341.359     2124220.669      201133.743
     2122320.165      200556.201     2120634.338      200516.535
#Sta/Elev= 30
       0   51.46  273.78   51.66  392.35    55.1  413.82   53.17  692.15   60.72
 1177.11   60.78 1340.71   55.84 1727.02   50.47 1744.15   47.15 1755.69   50.74
 2035.78   53.94 2270.45   47.12 2308.34   43.83 3182.86   42.34  3195.8    40.9
 3225.78   41.83 3883.79   42.09 3890.04    44.1 4252.29   46.04 4535.78   52.06
 5257.84    60.4 5829.85    52.6 6135.92    55.4 6465.97   65.53 7001.74   61.76
 7023.53   58.44 7048.94   59.29 7057.44   56.96  7070.4   59.73 7152.49   59.47
#Mann= 3 , 0 , 0
       0     .12       0 3182.86     .06       0 3225.78     .12       0
#XS Ineff= 2 , 0
         2371.06      60 3929.99           60.06
Permanent Ineff=
       F       F
Bank Sta=3182.86,3225.78
XS Rating Curve= 0
Exp/Cntr=.3,.1

Type RM Length L Ch R = 1 ,27693.46,782.88,920.16,679.51
XS GIS Cut Line= 6
     2127779.796      201222.721      2126148.53      201015.105
     2123568.162      200362.599     2122322.468      200451.577
     2120335.288      200421.917     2116687.183      201133.743
#Sta/Elev= 30
       0   52.56  375.56   51.03 1294.71   61.99  1827.1   48.19 2000.82   50.44
  2036.5   44.81 2046.81   47.26 2237.78   43.65 2861.37   41.89  2874.6   40.64
 2906.43   42.32  4738.2   48.17 4775.31   44.28 4794.42   48.64 5373.69   59.03
 6074.49   57.12 6556.14   65.09  7587.7   54.85 7608.61   51.24 7618.54   54.38
 8053.21   55.54  8064.2   53.09 8074.06   55.52 8521.85    56.9  9385.8   52.17
 9406.69   49.62 9476.33   52.21 9671.21   49.8110588.13   56.0811265.25   56.37
#Mann= 3 , 0 , 0
       0     .12       0 2861.37     .06       0 2906.43     .12       0
#XS Ineff= 2 , 0
         2282.38   60.82 3864.64           61.08
Permanent Ineff=
       F       F
Bank Sta=2861.37,2906.43
XS Rating Curve= 0
Exp/Cntr=.3,.1

Type RM Length L Ch R = 1 ,26773.30,578.98,670.36,322.27
XS GIS Cut Line= 6
     2127750.137      201015.105     2126326.486      200540.555
     2124843.516      199769.411      2122678.38      200154.983
     2119920.057      200154.983     2116212.632      200688.852
#Sta/Elev= 30
       0   50.81  352.78   50.04  873.92   55.08 1140.86   60.95 1464.91   60.15
 1815.96   48.04 2058.92   43.81 3099.65    41.7 3109.25   40.37 3135.28   41.85
 4321.97   45.58 4401.57   42.88 4530.76   47.21 5720.19   50.71 6090.33   52.99
 6269.73   57.58 7262.17   54.59 7274.57   51.61 7803.75   52.97  7821.1   48.41
  7867.8   52.87 8075.71   52.28 8166.99   55.77  8361.9   48.69 8496.27   55.46
 8727.65   56.4110113.16   50.6710333.98   53.9210811.88   52.7511876.04   58.92
#Mann= 3 , 0 , 0
       0     .12       0 3099.65     .06       0 3135.28     .12       0
#XS Ineff= 2 , 0
         2156.36   58.22 3836.64           58.22
Permanent Ineff=
       F       F
Bank Sta=3099.65,3135.28
XS Rating Curve= 0
Exp/Cntr=.3,.1

Type RM Length L Ch R = 1 ,26102.94,567.21,772.29,1133.55
XS GIS Cut Line= 6
      2128076.39      201074.424     2126563.761      200332.939
     2125199.429       199324.52      2122678.38      200066.005
     2118466.746      200036.345     2116064.335      200481.236
#Sta/Elev= 30
       0   49.58 1109.39   53.49 1312.47   51.52 1336.48    54.3 1503.52    54.3
  1637.7   59.27 1776.22   59.05 2431.63   52.32 2676.16   41.35 3357.93   41.42
 3364.98   40.17 3396.08   41.42 5046.98    42.9 5247.74   46.97 6980.17   50.97
 7780.19   48.18 7943.02   51.32 8457.88   50.42 8468.88   48.17  8504.1   52.76
 9239.72   55.6510259.29   55.1610333.04   52.5610450.13   56.1810644.46   52.92
 11168.7   55.3611432.41   51.41 11819.1   56.7512011.75   53.9312719.42   59.88
#Mann= 3 , 0 , 0
       0     .12       0 3357.93     .06       0 3396.08     .12       0
#XS Ineff= 2 , 0
         2613.77   57.78 4410.74           58.16
Permanent Ineff=
       F       F
Bank Sta=3357.93,3396.08
XS Rating Curve= 0
Exp/Cntr=.3,.1

Type RM Length L Ch R = 1 ,25330.65,597.38,475.59,660.12
XS GIS Cut Line= 6
     2128165.369      201044.765     2127512.862      200718.511
     2127156.949      200125.323     2125762.958      198760.991
     2124784.198      198434.738      2117814.24      198256.781
#Sta/Elev= 30
       0   51.02  455.23   48.35  476.66   51.23  627.53   49.46 1490.82   55.74
 1665.63   54.31 1872.39   47.85 2246.84   46.76 2445.87   41.93 3508.18   41.49
 3518.15   39.95 3553.74    41.2 5082.73   41.89  5382.7   47.64 5609.24   46.72
 6208.56   58.44 6720.88   58.78 6926.44   55.68 7121.98   59.46 7652.72   58.43
 7874.85   61.51 8341.57   56.65 9257.78   53.76 9314.87   50.92 9336.08   53.27
 9826.54   56.5610353.27   55.9710756.43   48.8610862.78   52.3111390.18   53.47
#Mann= 3 , 0 , 0
       0     .12       0 3508.18     .06       0 3553.74     .12       0
#XS Ineff= 2 , 0
         2730.46   55.94 4746.79           55.89
Permanent Ineff=
       F       F
Bank Sta=3508.18,3553.74
XS Rating Curve= 0
Exp/Cntr=.3,.1

Type RM Length L Ch R = 1 ,24855.06,854.1,858.46,592.19
XS GIS Cut Line= 4
     2127982.034      200554.428      2127231.83      199147.796
     2124637.375      197584.871     2119260.913      197209.769
#Sta/Elev= 30
       0   50.99  320.64   47.84     503    51.7  678.85   48.65  827.04   52.46
 1567.92   48.55 1597.95    46.5 1851.15   47.46  1886.4   43.13 1945.06   41.89
 3274.11    41.4 3282.93   39.81 3314.16   41.41 5189.51   41.86 5745.71   53.74
  6795.8   62.31 7144.88   62.01 7162.19   58.37 7174.24   61.49 7225.93   62.76
 7358.91   61.63 7404.53   59.06 7414.38   61.51 7448.51   62.56 7484.58   59.75
 7810.55   64.05 7923.31    59.8 8080.84   61.81 9490.63   54.7310012.57   56.67
#Mann= 3 , 0 , 0
       0     .12       0 3274.11     .06       0 3314.16     .12       0
#XS Ineff= 2 , 0
         2436.41   54.15 4634.77           54.15
Permanent Ineff=
       F       F
Bank Sta=3274.11,3314.16
XS Rating Curve= 0
Exp/Cntr=.3,.1

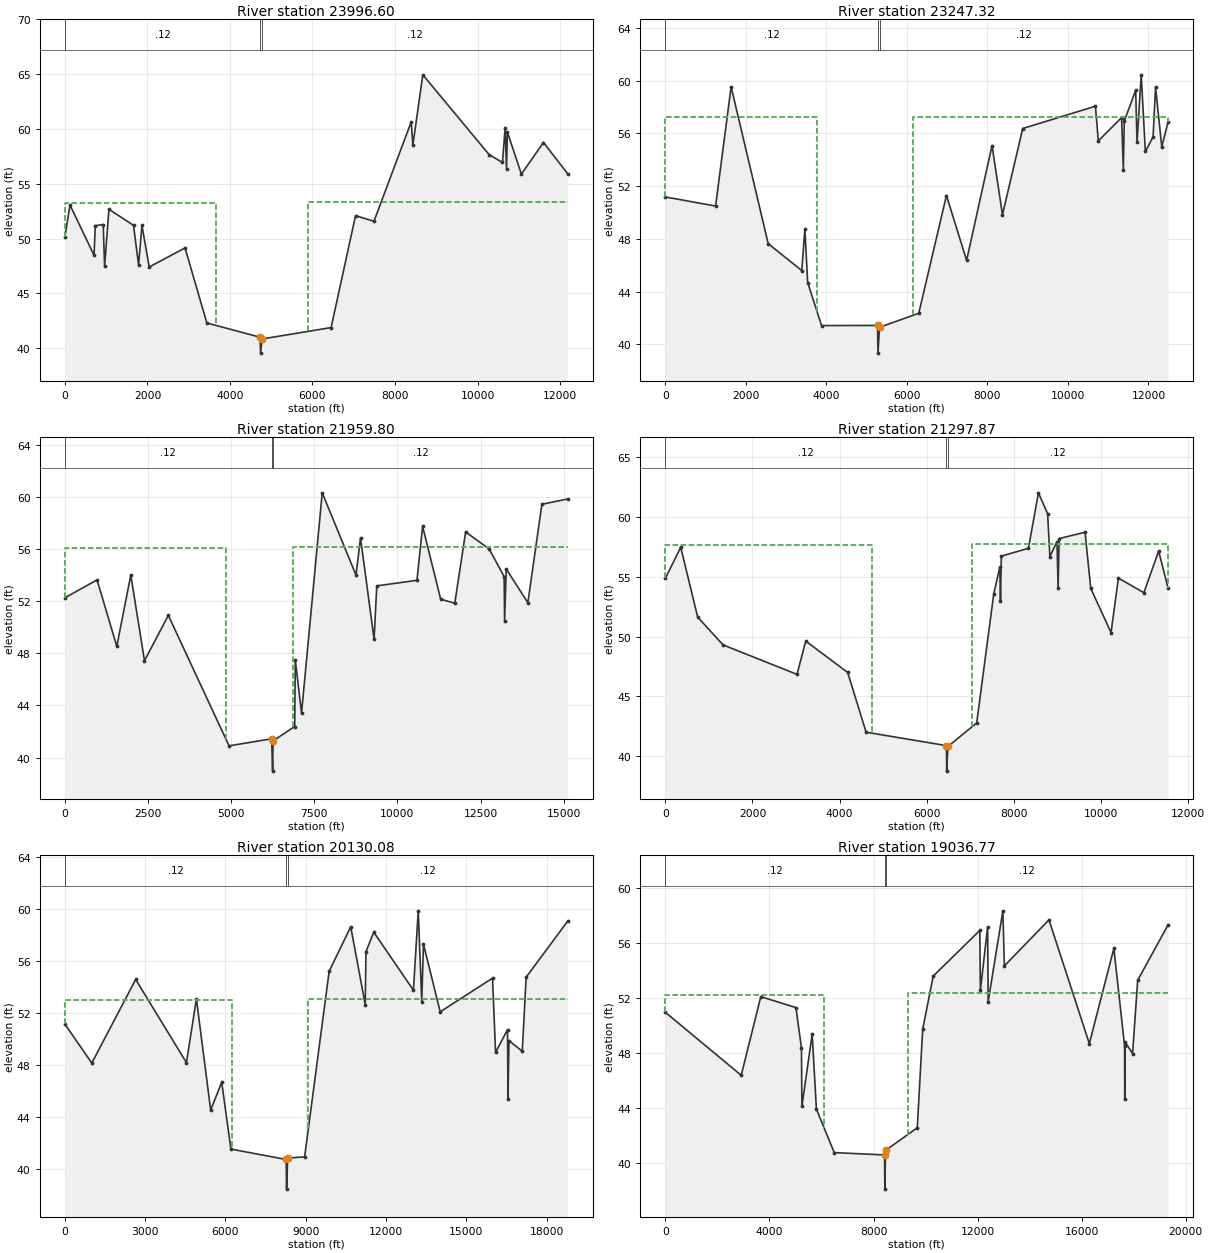
Type RM Length L Ch R = 1 ,23996.60,649.24,749.28,950.91
XS GIS Cut Line= 6
     2128669.578      200970.616     2127868.775       198805.48
     2127572.181      198301.271     2125733.298      197322.511
     2123004.634      196966.598     2118555.725      196670.004
#Sta/Elev= 30
       0   50.16  122.45   53.06  705.74   48.48  735.96   51.18   928.3   51.28
  960.99   47.47 1066.85   52.67 1662.59   51.21 1785.24    47.6 1866.37   51.21
 2042.15   47.41 2911.29   49.15 3439.66   42.31 4728.62   41.01 4742.22   39.56
 4777.37   40.85 6451.68   41.89 7043.75   52.09 7490.87   51.58 8393.93   60.65
 8432.51   58.51 8674.72   64.9310282.52   57.6510604.95   56.9410669.35   60.09
10703.57   56.36 10723.2   59.7211063.45   55.8811598.63   58.7612187.16   55.91
#Mann= 3 , 0 , 0
       0     .12       0 4728.62     .06       0 4777.37     .12       0
#XS Ineff= 2 , 0
         3659.28   53.23 5880.98           53.34
Permanent Ineff=
       F       F
Bank Sta=4728.62,4777.37
XS Rating Curve= 0
Exp/Cntr=.3,.1

Type RM Length L Ch R = 1 ,23247.32,977.64,1287.52,1264.56
XS GIS Cut Line= 4
     2129357.408      200616.945     2128107.068      197959.973
     2124199.756       195521.81     2119260.913      195209.225
#Sta/Elev= 30
       0   51.18 1248.42   50.49 1633.99   59.53 2554.98   47.64 3388.55    45.6
 3466.63   48.73  3536.2   44.69  3881.2   41.43 5271.12   41.44 5281.79   39.34
 5321.08    41.3 6295.25   42.36 6983.49   51.29 7484.03   46.37 8115.85   55.08
 8374.93   49.83 8878.29   56.37 10684.4   58.0610756.09   55.4311333.81    57.2
11378.25   53.2611400.44   56.9311684.44   59.2711717.95   55.3111821.79   60.44
11924.72   54.6312116.33   55.7312177.68    59.5 12332.2   54.9912490.81   56.88
#Mann= 3 , 0 , 0
       0     .12       0 5271.12     .06       0 5321.08     .12       0
#XS Ineff= 2 , 0
         3773.63   57.24 6142.36           57.24
Permanent Ineff=
       F       F
Bank Sta=5271.12,5321.08
XS Rating Curve= 0
Exp/Cntr=.3,.1

Type RM Length L Ch R = 1 ,21959.80,734.47,661.94,645.83
XS GIS Cut Line= 6
     2130508.461      201074.424     2129529.701      198731.332
      2128106.05      197011.087     2126593.421      195557.777
     2124279.988      194786.632     2118496.406      194193.444
#Sta/Elev= 30
       0   52.26  966.62   53.63 1559.74   48.53 1980.85      54 2392.72   47.43
 3109.17   50.91 4935.35    40.9 6215.31   41.44 6246.18   38.96 6260.67   41.28
 6911.01   42.38 6928.19   47.49 7116.15   43.41 7738.15   60.31 8753.91      54
 8889.95   56.86 9298.16   49.07 9378.62   53.1710587.88    53.610757.19   57.74
11300.76   52.1511725.17   51.8412051.69   57.3112759.59      5613210.34   53.88
13223.41   50.4813272.73   54.4713922.68   51.8814345.02   59.43 15122.4   59.84
#Mann= 3 , 0 , 0
       0     .12       0 6215.31     .06       0 6260.67     .12       0
#XS Ineff= 2 , 0
         4835.47    56.1 6870.48           56.16
Permanent Ineff=
       F       F
Bank Sta=6215.31,6260.67
XS Rating Curve= 0
Exp/Cntr=.3,.1

Type RM Length L Ch R = 1 ,21297.87,1334.87,1167.79,1030.31
XS GIS Cut Line= 4
     2131014.109      200835.754     2129294.891      197084.735
      2126606.66      194740.347     2122855.641      193896.368
#Sta/Elev= 30
       0   54.85  352.86   57.46  742.21   51.62  1324.8    49.3 3021.13   46.84
 3222.82   49.62 4183.81      47 4607.54   42.01  6449.7   40.89 6456.94   38.76
 6484.32   40.82 7144.68   42.78 7536.24   53.56 7676.29    55.8 7690.56   52.94
 7709.84   56.71 8332.09   57.37 8561.28      62 8772.09   60.26 8824.02   56.68
 8986.88   57.91 9012.86   54.06  9037.4   58.18 9631.28   58.71 9761.56   54.02
10227.85   50.33 10396.3   54.8810981.14   53.6611320.17   57.1411537.93   54.02
#Mann= 3 , 0 , 0
       0     .12       0  6449.7     .06       0 6484.32     .12       0
#XS Ineff= 2 , 0
         4751.41   57.66 7043.17           57.73
Permanent Ineff=
       F       F
Bank Sta=6449.7,6484.32
XS Rating Curve= 0
Exp/Cntr=.3,.1

Type RM Length L Ch R = 1 ,20130.08,885.03,1093.31,1242.19
XS GIS Cut Line= 5
     2131951.922      202155.817     2130627.098      197515.297
     2129203.447      195261.183     2125970.573      193570.597
     2118318.449        193422.3
#Sta/Elev= 30
       0   51.11 1003.94   48.12 2644.38   54.55 4541.96   48.15 4914.01   53.06
 5447.22    44.5 5859.85   46.64 6203.78    41.5 8269.26    40.7 8283.98   38.42
 8325.64   40.81 8959.34    40.9 9877.62   55.1910682.14    58.611224.87   52.62
 11250.8   56.6811542.89   58.1913025.74   53.7213205.78   59.8313337.71   52.84
13400.82   57.2714026.33   52.0615982.49   54.6516095.81   48.9416542.94   50.69
16560.04   45.3516598.42   49.8417093.02   49.03 17239.9   54.7318793.78   59.04
#Mann= 3 , 0 , 0
       0     .12       0 8269.26     .06       0 8325.64     .12       0
#XS Ineff= 2 , 0
         6231.72   52.94 9101.52           53.08
Permanent Ineff=
       F       F
Bank Sta=8269.26,8325.64
XS Rating Curve= 0
Exp/Cntr=.3,.1

Type RM Length L Ch R = 1 ,19036.77,673.21,694.62,707.19
XS GIS Cut Line= 5
     2132842.154      201466.689     2131927.459      196893.212
     2128268.677      193081.981      2125829.49      193081.981
     2118893.049      193081.981
#Sta/Elev= 30
       0   50.98 2916.33   46.39  3668.5   52.12 5018.99   51.32  5231.1   48.38
 5248.31   44.13 5643.42   49.39 5805.33   43.93 6491.59   40.76 8424.79   40.59
 8435.03    38.1 8463.43   40.92 9682.45   42.57 9890.26   49.7510295.62   53.62
12084.29   56.9412106.92   52.5912386.09    57.212406.27   51.76   12972   58.37
13028.78   54.3614742.69   57.7116293.95    48.717236.51   55.63   17649   48.53
17655.91   44.6417667.52   48.8317955.98   47.9718152.18   53.3119322.91   57.36
#Mann= 3 , 0 , 0
       0     .12       0 8424.79     .06       0 8463.43     .12       0
#XS Ineff= 2 , 0
         6096.74   52.24 9311.55           52.36
Permanent Ineff=
       F       F
Bank Sta=8424.79,8463.43
XS Rating Curve= 0
Exp/Cntr=.3,.1

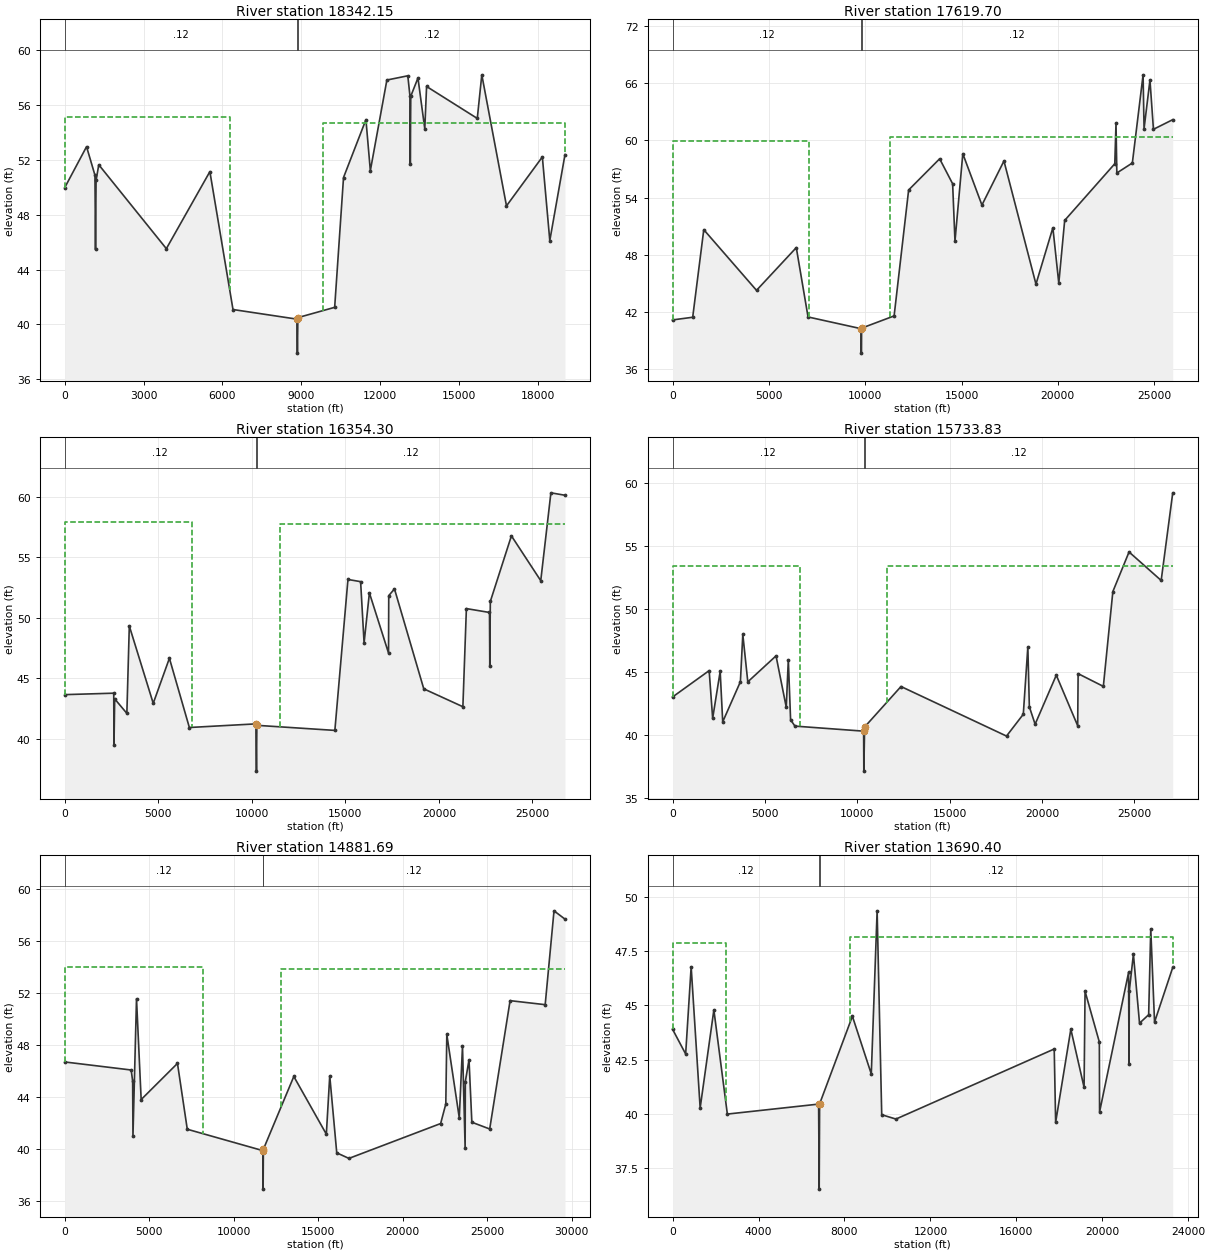
Type RM Length L Ch R = 1 ,18342.15,707.65,722.45,730.58
XS GIS Cut Line= 5
     2133561.676      201414.037     2132405.112      196506.452
     2129185.487      193005.501       2128497.8      192849.208
      2119964.23       192817.95
#Sta/Elev= 30
       0   49.98  827.92   52.96 1147.61   50.88 1168.97   45.46 1190.08    50.5
 1293.26   51.64    3865   45.52 5521.89   51.14  6401.6   41.08 8833.25   40.38
 8852.54    37.9 8871.32   40.4910271.29   41.2410608.31   50.7111461.22   54.93
11629.07   51.2112258.29   57.8213055.08   58.1313138.18   56.6313149.57   51.66
13167.74   56.64 13441.4   57.9713701.17   54.2613769.63   57.3515699.17   55.02
15871.26    58.216810.86   48.6418175.64   52.2118459.16   46.1119037.17   52.38
#Mann= 3 , 0 , 0
       0     .12       0 8833.25     .06       0 8871.32     .12       0
#XS Ineff= 2 , 0
         6276.72   55.16 9824.97           54.67
Permanent Ineff=
       F       F
Bank Sta=8833.25,8871.32
XS Rating Curve= 0
Exp/Cntr=.3,.1

Type RM Length L Ch R = 1 ,17619.70,1661.63,1265.4,910.79
XS GIS Cut Line= 4
     2134440.457      201787.145     2133027.215      196195.621
     2129498.072      192255.297     2114593.621      192570.348
#Sta/Elev= 30
       0   41.17 1045.38   41.45 1620.31   50.63 4357.96   44.27 6423.03   48.75
 7033.46   41.48 9788.75   40.25 9798.82   37.69 9814.72   40.3111501.02   41.59
12254.55   54.7913865.05   58.0614538.94   55.44 14660.3   49.4215067.17   58.59
16059.52   53.2117202.85   57.8318864.75   44.9219742.36   50.8320049.74   45.02
20354.92    51.622956.16   57.5423019.58   61.7723062.62   56.5723868.12   57.62
24425.47   66.8624475.68   61.2124782.32   66.3124963.17   61.1525964.86   62.16
#Mann= 3 , 0 , 0
       0     .12       0 9788.75     .06       0 9814.72     .12       0
#XS Ineff= 2 , 0
         7086.61   59.8911306.88           60.38
Permanent Ineff=
       F       F
Bank Sta=9788.75,9814.72
XS Rating Curve= 0
Exp/Cntr=.3,.1

Type RM Length L Ch R = 1 ,16354.30,580.9,620.47,653.87
XS GIS Cut Line= 4
     2136272.262      200170.871     2134366.647      193539.329
     2128116.228      191100.141     2115005.594      191862.388
#Sta/Elev= 30
       0   43.65  2616.4   43.77 2630.76   39.46 2666.89    43.3 3317.89    42.1
 3448.75   49.33 4728.02   42.93 5592.64   46.66 6659.55   40.93 10215.5   41.23
10247.48   37.3210268.98   41.1114438.78   40.6915138.55   53.1815815.68      53
16001.12   47.9316284.98   52.0717308.32   47.0917319.35   51.8417625.78    52.4
19192.44   44.1321283.22   42.6521470.91   50.7722706.04   50.4522722.13   46.02
22750.55   51.3623877.93   56.7925446.39   53.0825989.24   60.3526742.14   60.15
#Mann= 3 , 0 , 0
       0     .12       0 10215.5     .06       010268.98     .12       0
#XS Ineff= 2 , 0
         6816.65   57.9111516.92           57.78
Permanent Ineff=
       F       F
Bank Sta=10215.5,10268.98
XS Rating Curve= 0
Exp/Cntr=.3,.1

Type RM Length L Ch R = 1 ,15733.83,774.74,852.13,931.07
XS GIS Cut Line= 4
     2136750.043       199882.37     2134624.465      193130.535
     2127997.664      190254.753     2115291.084      191583.239
#Sta/Elev= 30
       0   43.01 1981.18    45.1 2170.89   41.32 2577.53   45.04 2714.95   41.04
 3672.77   44.22 3802.93   47.97 4073.42   44.21 5601.68   46.27 6155.27    42.2
 6266.85   45.96    6390    41.2 6625.39    40.710343.89    40.310354.58   37.13
10398.05   40.6312366.76   43.8418078.97   39.9118987.94   41.6419233.77   46.98
19315.65   42.2319627.59   40.8520774.19   44.7421932.18   40.7321955.92   44.86
23321.08   43.85 23835.9   51.3724712.74   54.5126451.83   52.2527078.25    59.2
#Mann= 3 , 0 , 0
       0     .12       010343.89     .06       010398.05     .12       0
#XS Ineff= 2 , 0
         6917.89   53.4311586.93            53.4
Permanent Ineff=
       F       F
Bank Sta=10343.89,10398.05
XS Rating Curve= 0
Exp/Cntr=.3,.1

Type RM Length L Ch R = 1 ,14881.69,1303.48,1191.3,1130.82
XS GIS Cut Line= 5
     2137546.346      200484.713     2135371.563      192971.825
     2131516.265      190797.042     2127908.102      189511.943
     2114532.176      191464.332
#Sta/Elev= 30
       0   46.69 3928.12   46.07  4014.8   45.21 4032.78   40.95  4242.7   51.57
 4518.28   43.79 6666.79   46.58  7246.7    41.511719.86   39.8511734.72   36.88
11749.45   39.9513550.53   45.5715475.35   41.12 15676.3   45.6216091.06   39.68
16811.67   39.2522238.23   41.9422543.71   43.4522603.31   48.8123341.39   42.38
23531.26   47.9123687.74   40.0423699.37   45.1823917.34   46.8624085.09   42.04
25140.89   41.5226347.92   51.4228423.97   51.1128946.33   58.35 29595.6   57.71
#Mann= 3 , 0 , 0
       0     .12       011719.86     .06       011749.45     .12       0
#XS Ineff= 2 , 0
         8200.22   54.0512789.65           53.84
Permanent Ineff=
       F       F
Bank Sta=11719.86,11749.45
XS Rating Curve= 0
Exp/Cntr=.3,.1

Type RM Length L Ch R = 1 ,13690.40,1220.98,1329.5,1369.93
XS GIS Cut Line= 4
     2136577.161      194301.575     2135662.465      191252.591
     2128040.004      188203.606     2116225.188      189499.424
#Sta/Elev= 30
       0    43.9  609.53   42.76   865.4   46.78 1284.25   40.27 1922.47   44.79
 2549.61   39.99 6797.33   40.45  6824.3   36.53 6843.89   40.46 8369.79    44.5
 9248.74   41.84 9520.49   49.36 9734.63   39.9610395.58   39.7617762.23   42.99
17828.92   39.6118535.67    43.919152.35   41.2219197.63   45.6519862.52   43.31
19873.45   40.0921223.12   46.5221243.46   42.3221258.09   45.6821447.74   47.36
21732.45   44.1822157.63   44.5722255.36   48.5322431.51   44.2323278.52   46.75
#Mann= 3 , 0 , 0
       0     .12       0 6797.33     .06       0 6843.89     .12       0
#XS Ineff= 2 , 0
         2474.69   47.86 8267.72           48.14
Permanent Ineff=
       F       F
Bank Sta=6797.33,6843.89
XS Rating Curve= 0
Exp/Cntr=.3,.1