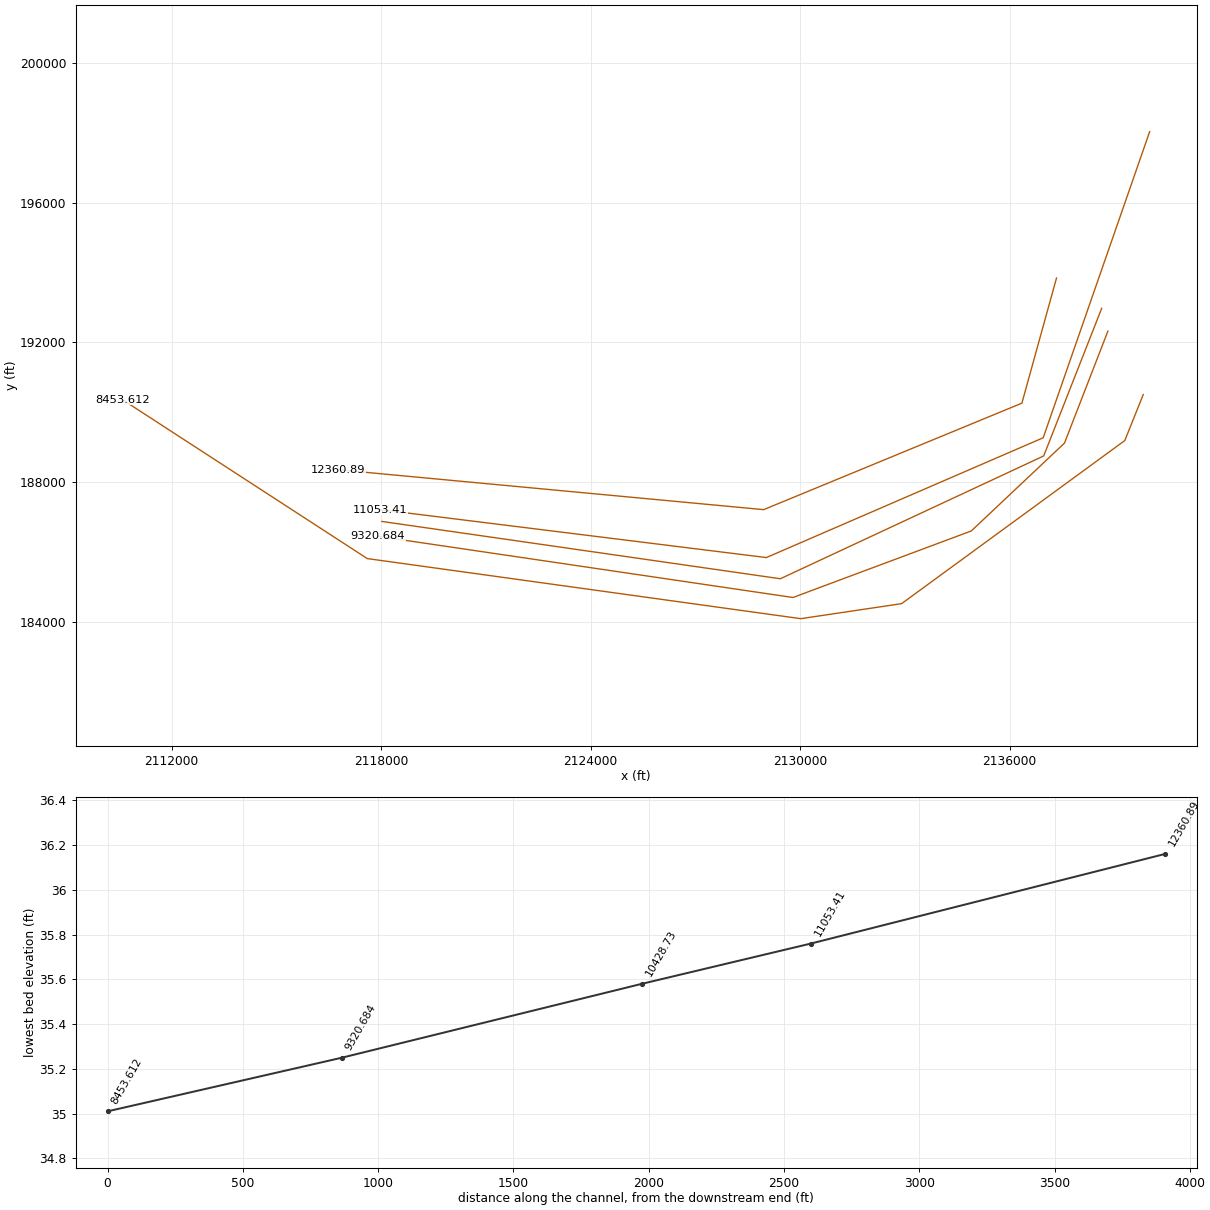
HEC-RAS study bogue.prj: NCFM-Bogue Swamp - Detailed Study

--- bogue.g01 (geometry) --- (continued)

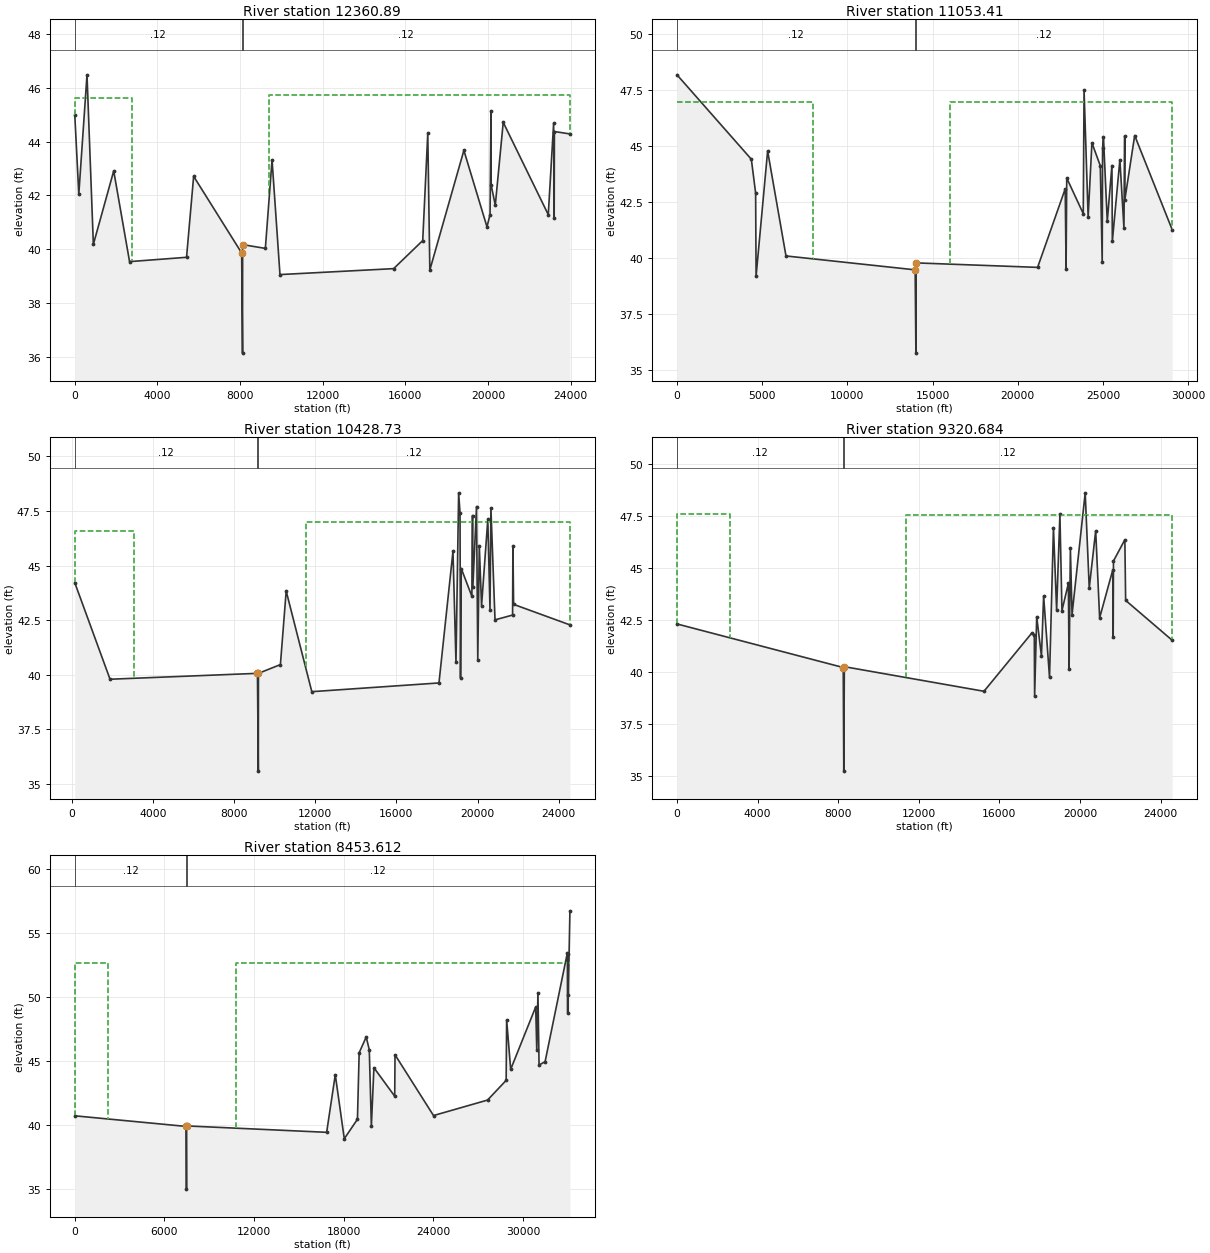
Type RM Length L Ch R = 1 ,12360.89,1257.03,1307.49,1317.87
XS GIS Cut Line= 4
     2137339.407      193844.228     2136348.487      190261.671
     2128954.699      187212.686      2116758.76      188356.055
#Sta/Elev= 30
       0   44.97  194.14   42.05  590.68   46.47  898.51   40.19 1883.76   42.91
 2650.55   39.55 5408.55   39.71 5751.95   42.71 8075.97   39.87 8118.37   36.16
  8123.9   40.18 9223.13   40.04 9546.94   43.32 9930.39   39.0715431.74   39.29
16839.69   40.3317083.97    44.317183.81   39.2418831.64   43.6719949.19   40.84
20098.07   41.2920144.14   45.1320153.52   42.3820352.05   41.6420735.85   44.71
22916.29   41.2923175.96   44.6723202.12   41.1523213.17   44.3723964.31   44.28
#Mann= 3 , 0 , 0
       0     .12       0 8075.97     .06       0  8123.9     .12       0
#XS Ineff= 2 , 0
         2755.91    45.6  9420.7           45.71
Permanent Ineff=
       F       F
Bank Sta=8075.97,8123.9
XS Rating Curve= 0
Exp/Cntr=.3,.1

Type RM Length L Ch R = 1 ,11053.41,624.17,624.67,636.21
XS GIS Cut Line= 4
     2140007.268      198036.582     2136958.284      189270.751
     2129030.924      185840.643     2117978.354      187212.686
#Sta/Elev= 30
       0   48.19 4362.76   44.42 4614.27   42.91 4641.29    39.2 5318.81   44.79
 6395.81    40.113975.91   39.4814019.97   35.7614034.02   39.7921161.59   39.59
 22782.3    43.122832.51   39.52 22871.3   43.5823841.27   41.9923887.57    47.5
24127.67   41.84   24349   45.1524840.22   44.1324953.07   39.8124974.59   44.91
25026.71   45.4125249.34   41.6525524.25   44.1425547.06   40.7525990.71    44.4
26228.21   41.3426272.59   45.4626279.52    42.626858.66   45.4829055.94   41.28
#Mann= 3 , 0 , 0
       0     .12       013975.91     .06       014034.02     .12       0
#XS Ineff= 2 , 0
         7997.75   46.98 15995.5           46.98
Permanent Ineff=
       F       F
Bank Sta=13975.91,14034.02
XS Rating Curve= 0
Exp/Cntr=.3,.1

Type RM Length L Ch R = 1 ,10428.73,1087.39,1108.05,881.61
XS GIS Cut Line= 4
 2138633.7029863  192978.2931378      2136972.76      188750.438
     2129431.647      185233.856     2118022.295      186874.928
#Sta/Elev= 30
  159.37   44.21 1895.21   39.79 9156.49   40.06 9199.95   35.58 9205.51   40.06
10287.58   40.4610571.81   43.8311834.72   39.22 18098.2   39.6218788.49   45.65
18935.95   40.5619067.39   48.3319135.22   47.4119159.76   39.8519196.85   44.86
19719.57   43.5919750.85   47.2919766.42   44.0119947.96    47.720009.71   40.66
20085.32    45.920196.37   43.1620504.12   47.1120611.88   42.98 20657.1   47.63
20858.97   42.5121724.39   42.7321741.14   45.8921775.18   43.2224549.31   42.28
#Mann= 3 , 0 , 0
  159.37     .12       0 9156.49     .06       0 9205.51     .12       0
#XS Ineff= 2 , 0
         3065.24   46.5811529.81           46.98
Permanent Ineff=
       F       F
Bank Sta=9156.49,9205.51
XS Rating Curve= 0
Exp/Cntr=.3,.1

Type RM Length L Ch R = 1 ,9320.684,639.68,867.07,1193.26
XS GIS Cut Line= 5
     2138811.409      192324.746     2137568.081      189118.301
     2134900.219      186602.889      2129793.17      184697.274
     2117902.129       186450.44
#Sta/Elev= 30
       0   42.31 8251.22   40.22 8278.97   35.25 8306.64   40.2615237.39   39.08
17617.41   41.8817735.17   41.7917751.15   38.8417854.34   42.6618089.95   40.77
18198.09   43.6518490.72   39.7518685.98   46.9318843.51   42.9819005.99   47.57
19108.28   42.9519427.14   44.26 19461.7   40.1319526.52   45.9319609.08   42.76
20261.63    48.6 20462.3   44.0320782.36   46.7820977.84    42.621629.99    44.9
21650.29   41.69 21664.9   45.3322229.81   46.35 22269.1   43.4424576.35   41.53
#Mann= 3 , 0 , 0
       0     .12       0 8251.22     .06       0 8306.64     .12       0
#XS Ineff= 2 , 0
         2643.42   47.5811361.08           47.56
Permanent Ineff=
       F       F
Bank Sta=8251.22,8306.64
XS Rating Curve= 0
Exp/Cntr=.3,.1

Type RM Length L Ch R = 1 ,8453.612,7263.99,8453.61,7339.29
XS GIS Cut Line= 6
     2139823.495      190508.945     2139294.637      189190.856
     2132904.324      184521.012     2130016.395      184090.895
     2117604.441      185811.364     2110599.676      190358.317
#Sta/Elev= 30
       0   40.74 7452.21   39.91  7476.4   35.01 7487.85   39.9516859.61   39.45
17437.39   43.9518039.59   38.9518921.12   40.4719036.18   45.6719507.68    46.9
19712.38   45.9119853.39   39.9420022.93    44.521415.93   42.2721435.96   45.51
24012.11   40.7627629.88   41.9728876.12   43.5128908.19   48.2329178.69   44.37
30854.08   49.2530923.66   45.9131003.96   50.3631078.29   44.7131482.44   44.97
32973.88   53.4832993.83   48.8133006.34    53.4 33034.8   50.1733144.58   56.76
#Mann= 3 , 0 , 0
       0     .12       0 7452.21     .06       0 7487.85     .12       0
#XS Ineff= 2 , 0
         2204.72   52.69 10787.4           52.65
Permanent Ineff=
       F       F
Bank Sta=7452.21,7487.85
XS Rating Curve= 0
Exp/Cntr=.3,.1

Chan Stop Cuts=-1