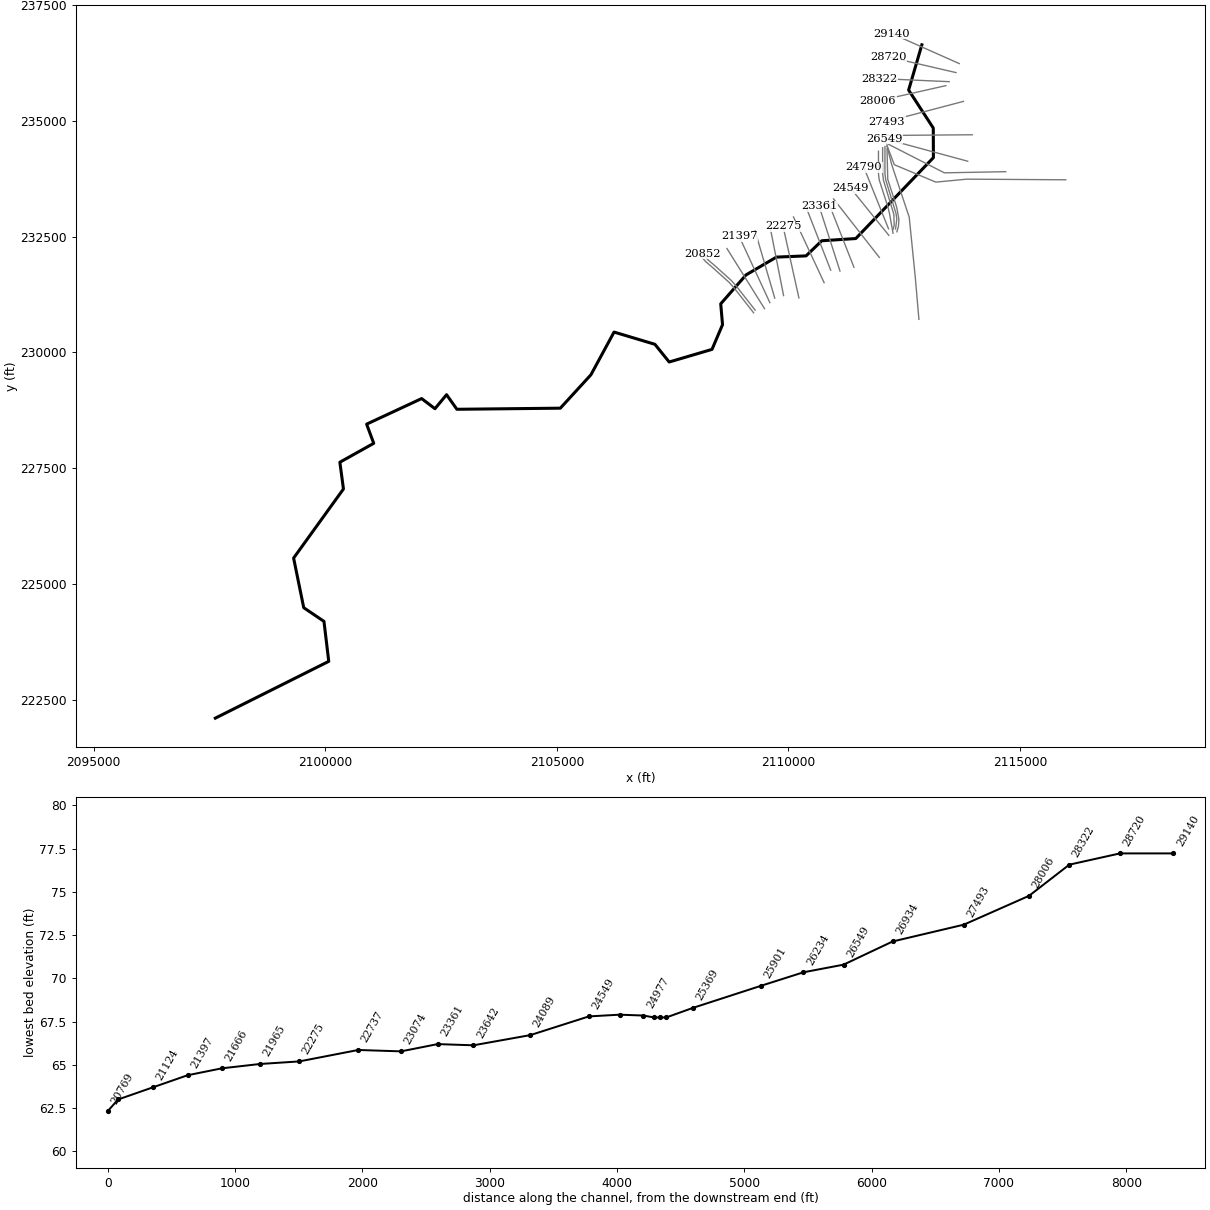
--- welch.prj (project) ---

Proj Title=Welch Creek - Approximate Study
Current Plan=p01
Default Exp/Contr=.3,.1
English Units
Geom File=g01
Flow File=f01
Plan File=p01
Y Axis Title=Elevation
X Axis Title(PF)=Main Channel Distance
X Axis Title(XS)=Station
BEGIN DESCRIPTION:
Welch Creek - Approximate Study
END DESCRIPTION:

--- welch.p01 (plan) ---

Plan Title=100 YR Storm Event
Version=September 1998 Version 2.2
Short Identifier=WelchCreek
Geom File=g01
Flow File=f01
Interactive Comp Mode
Subcritical Flow
K Sum by GR= 0
Std Step Tol= 0.01
Critical Tol= 0.01
Num of Std Step Trials= 20
Max Error Tol= 0.3
Flow Tol Ratio= 0.001
Log Output Level= 0
Friction Slope Method= 1
Parabolic Critical Depth
Global Vel Dist= 0 , 0 , 0
Global Log Level= 0
Encroach Param=-1 ,0,0, 2
Encroach River=Welch Creek
Encroach Reach=Welch Creek
Encroach Node=29140
       4      .9
Encroach Node=28720
       4      .9
Encroach Node=28322
       4      .9
Encroach Node=28006
       4      .9
Encroach Node=27493
       4      .8
Encroach Node=26934
       4      .9
Encroach Node=26549
       4      .9
Encroach Node=26234
       4      .9
Encroach Node=25901
       4      .9
Encroach Node=25369
       4      .9
Encroach Node=25157
       4      .9
Encroach Node=25111
       1  637.09     732
Encroach Node=25087
       1     647     692
Encroach Node=25061
       1  634.81     712
Encroach Node=24977
       4      .8
Encroach Node=24790
       4      .9
Encroach Node=24549
       4      .9
Encroach Node=24089
       4      .9
Encroach Node=23642
       4      .9
Encroach Node=23361
       4      .9
Encroach Node=23074
       4      .9
Encroach Node=22737
       4      .9
Encroach Node=22275
       4      .9
Encroach Node=21965
       4      .9
Encroach Node=21666
       4      .9
Encroach Node=21397
       4      .9
Encroach Node=21124
       4      .9
Encroach Node=20852
       4      .9
Encroach Node=20769
       1     560     661
Encroach Node=20727
       1     580     641
Encroach Node=20687
       1     560     661
Encroach Node=20550
       4      .9
Encroach Node=20327
       4      .9
Encroach Node=20075
       4      .9
Encroach Node=19471
       4      .9
Encroach Node=19154
       4      .9
Encroach Node=18797
       4      .9
Encroach Node=18150
       4      .9
Encroach Node=17823
       4      .9
Encroach Node=17609
       4      .9
Encroach Node=17203
       4      .9
Encroach Node=16927
       4      .9
Encroach Node=16651
       4      .9
Encroach Node=16387
       4      .9
Encroach Node=15981
       4      .9
Encroach Node=15659
       4      .9
Encroach Node=15326
       1  717.37    1000
Encroach Node=14936
       4      .9
Encroach Node=14522
       4      .9
Encroach Node=14465
       1  827.81  915.81
Encroach Node=14431
       1     830     886
Encroach Node=14394
       1  813.42  901.59
Encroach Node=14280
       4      .9
Encroach Node=13875
       4      .9
Encroach Node=13272
       4      .9
Encroach Node=12686
       4      .9
Encroach Node=12231
       4      .9
Encroach Node=11871
       4      .9
Encroach Node=11453
       4      .9
Encroach Node=11253
       4      .9
Encroach Node=10925
       4      .9
Encroach Node=10672
       4      .9
Encroach Node=10294
       4      .9
Encroach Node=9800
       4      .9
Encroach Node=9435
       4      .9
Encroach Node=8942
       4      .9
Encroach Node=8543
       4      .9
Encroach Node=8134
       4      .9
Encroach Node=8034
       1 1251.03 1317.67
Encroach Node=7990
       1    1251 1317.67
Encroach Node=7950
       1    1251 1317.46
Encroach Node=7801
       4      .9
Encroach Node=7152
       4      .9
Encroach Node=6497
       4      .9
Encroach Node=5960
       4      .9
Encroach Node=5421
       4      .9
Encroach Node=4918
       4      .9
Encroach Node=4466
       4      .9
Encroach Node=4016
       4      .9
Encroach Node=3496
       4      .9
Encroach Node=3006
       4      .9
Encroach Node=2508
       4      .9
Encroach Node=2020
       4      .9
Encroach Node=1460
       4      .9
Encroach Node=987
       4      .9
Encroach Node=495
       4      .9
Encroach Node=23
       4      .9

--- welch.f01 (steady flow) ---

Flow Title=Welch Creek Flowrates
Version=September 1998 Version 2.2
Number of Profiles= 2
Profile Names=100 YR,FLOODWAY
River Rch & RM=Welch Creek,Welch Creek     ,29140
     430     430
River Rch & RM=Welch Creek,Welch Creek     ,27493
     470     470
River Rch & RM=Welch Creek,Welch Creek     ,26549
     560     560
River Rch & RM=Welch Creek,Welch Creek     ,25157
    1140    1140
River Rch & RM=Welch Creek,Welch Creek     ,22275
    1190    1190
River Rch & RM=Welch Creek,Welch Creek     ,19154
    1220    1220
River Rch & RM=Welch Creek,Welch Creek     ,16927
    1320    1320
River Rch & RM=Welch Creek,Welch Creek     ,16387
    1430    1430
River Rch & RM=Welch Creek,Welch Creek     ,13272
    1460    1460
River Rch & RM=Welch Creek,Welch Creek     ,9800
    1510    1510
River Rch & RM=Welch Creek,Welch Creek     ,5421
    1580    1580
Boundary for River Rch & Prof#=Welch Creek,Welch Creek     , 1
Up Type= 0
Dn Type= 3
Dn Slope=.0005
Boundary for River Rch & Prof#=Welch Creek,Welch Creek     , 2
Up Type= 0
Dn Type= 3
Dn Slope=.0005
DSS Import GetInterval= 0
DSS Import GetPeak= 0
DSS Import FillOption= 0

--- welch.g01 (geometry) ---

Geom Title=Welch Creek Layout
Version=September 1998 Version 2.2

River Reach=Welch Creek     ,Welch Creek
Reach XY= 30
      2112879.16      236640.513     2112593.692      235663.005
     2113125.767       234843.23     2113128.289      234204.502
      2111452.83      232457.862     2110719.565      232410.085
     2110379.493      232083.481     2109739.202      232057.006
     2109082.211      231671.868     2108537.178      231048.193
     2108575.953      230598.112     2108349.053      230065.153
     2107424.547       229792.51     2107116.391      230174.441
     2106234.369        230438.7     2105735.037      229516.883
     2105074.109      228795.665     2102841.526      228771.932
     2102618.481      229086.589     2102367.554      228784.337
     2102080.244      229003.127     2100892.651      228450.707
     2101045.876      228036.947     2100314.973      227628.829
     2100392.316      227051.035     2099316.342      225559.649
      2099534.78      224488.526     2099971.558      224193.004
     2100075.004      223330.061     2097626.299      222103.893

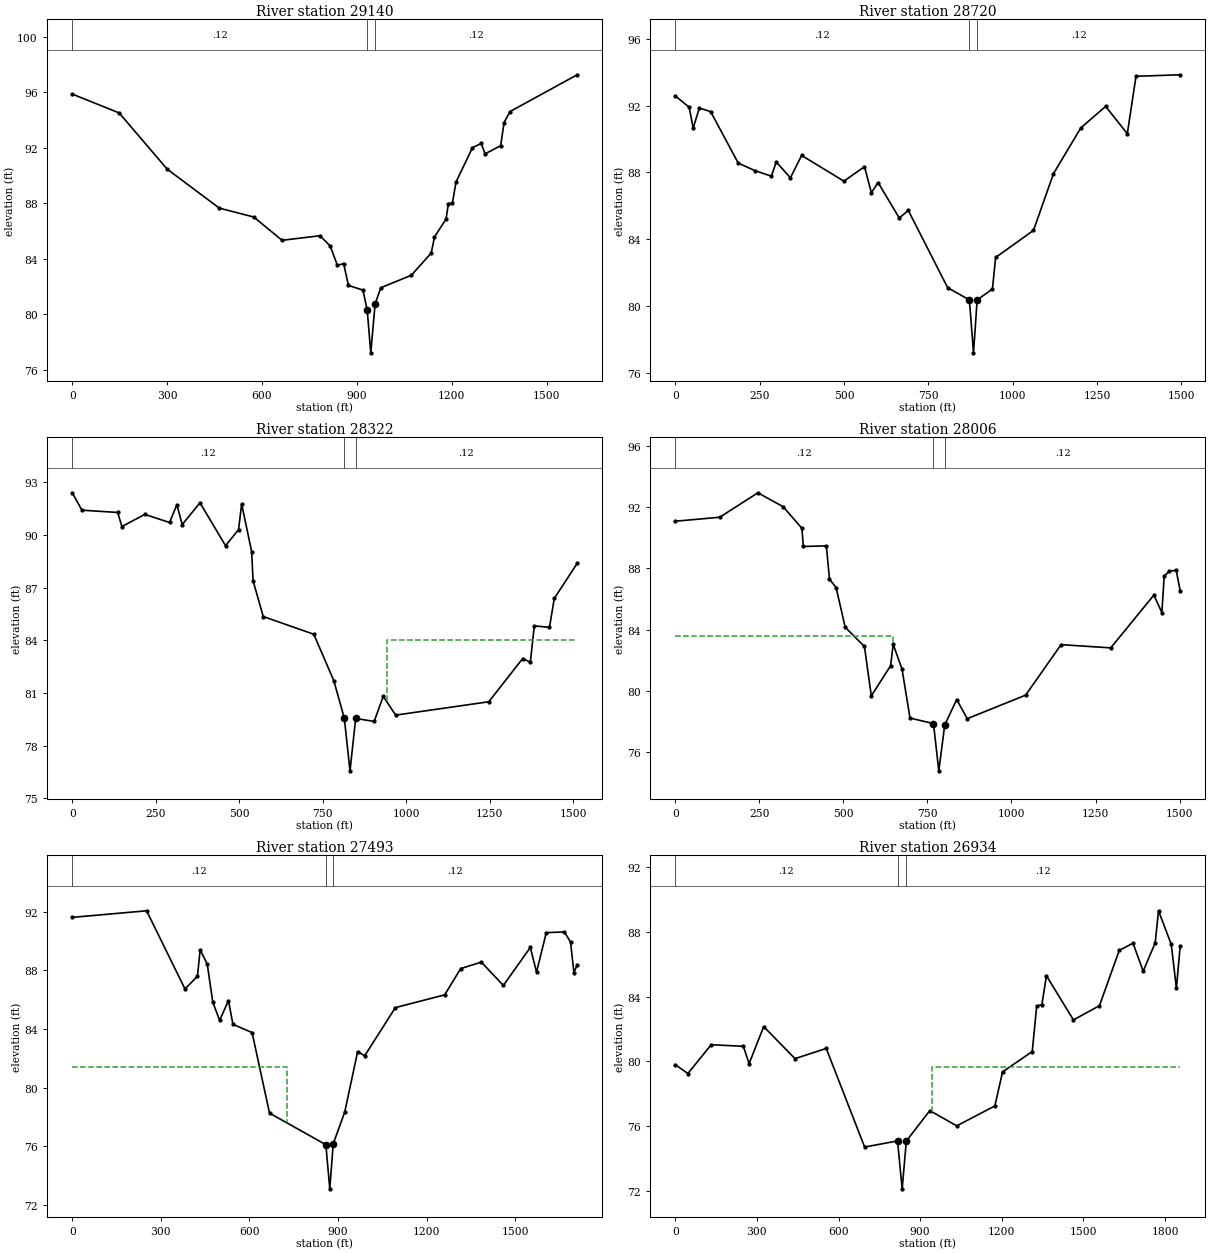
Type RM Length L Ch R = 1 ,29140   ,383.28,419.96,405.88
XS GIS Cut Line= 2
      2113687.42      236234.624     2112228.498      236883.034
#Sta/Elev= 30
       0   95.87  148.44   94.51  300.16   90.46   465.1   87.65  573.85   87.01
  663.55   85.33  783.32   85.66  815.75   84.92  838.25   83.53  858.17   83.65
   873.3   82.08  919.32   81.74  932.75   80.29  944.01   77.22  957.75   80.75
  975.66   81.91 1072.14   82.81 1135.12   84.41 1145.45   85.57 1181.96   86.86
  1189.6   87.98 1202.06      88 1213.49   89.53 1265.62   92.01 1293.27   92.31
 1305.55   91.56 1354.72   92.15 1365.47   93.82 1384.37   94.61 1596.52   97.26
#Mann= 3 , 0 , 0
       0     .12       0  932.75     .06       0  957.75     .12       0
Bank Sta=932.75,957.75
Exp/Cntr=.3,.1

Type RM Length L Ch R = 1 ,28720   ,365,397.85,389.24
XS GIS Cut Line= 3
 2113616.2923674  236040.3764067     2113606.551      236042.636
 2112158.8723674  236378.4374067
#Sta/Elev= 30
       0   92.58   41.27    91.9   53.05   90.65   71.24   91.85  104.79   91.64
  186.71   88.56  236.14   88.11  284.89   87.78   299.2   88.63   341.3   87.68
  374.41   89.02  499.76   87.48  560.75   88.35  581.11   86.79  600.91    87.4
  663.77   85.28  690.56   85.73  807.07   81.12  871.62   80.38  883.71   77.22
  894.54   80.38  939.94   81.04  949.23   82.92 1061.49   84.54 1120.71   87.93
 1201.85   90.67 1275.18   91.95 1339.49   90.32 1365.28   93.75 1496.11   93.84
#Mann= 3 , 0 , 0
       0     .12       0  871.62     .06       0  894.54     .12       0
Bank Sta=871.62,894.54
Exp/Cntr=.3,.1

Type RM Length L Ch R = 1 ,28322   ,304.82,315.99,324.25
XS GIS Cut Line= 4
 2113469.0880968  235844.2721794     2112058.981      235907.412
 2111969.0710871  235911.4378614 2111959.0810968  235911.8851794
#Sta/Elev= 30
       0   92.39   29.08    91.4  136.09   91.27  148.77   90.47  217.17   91.16
  291.38    90.7  313.29   91.71   329.2   90.58  382.47   91.82  458.94   89.38
  497.81   90.29   507.2   91.75  537.24   89.03  541.26   87.39   571.8   85.35
  723.22   84.34  783.27   81.69  814.57   79.56  831.58   76.57  848.51   79.55
  903.92   79.38  931.02   80.81  968.16   79.74 1247.12    80.5 1348.51   82.96
 1371.44   82.75 1383.23   84.82 1428.65   84.73 1443.11   86.38 1511.52   88.37
#Mann= 3 , 0 , 0
       0     .12       0  814.57     .06       0  848.51     .12       0
#XS Ineff= 2 , 0
                          941.07           83.99
Bank Sta=814.57,848.51
Exp/Cntr=.3,.1

Type RM Length L Ch R = 1 ,28006   ,477.32,513.2,507.3
XS GIS Cut Line= 4
 2113397.1011686  235758.5980274     2112058.981      235456.663
 2111941.9239249  235430.2501023 2111932.1691686  235428.0490274
#Sta/Elev= 30
       0   91.09  132.23   91.35  245.74   92.95  320.78   92.04   376.7   90.63
  381.01   89.44  449.43   89.48  458.71    87.3  478.44   86.75  505.44   84.16
  562.74    82.9  583.08   79.67  640.47   81.64  648.19   83.04  674.43   81.43
  698.23   78.22  768.06   77.86  783.86   74.77  801.49   77.77  837.08   79.43
  868.52   78.18 1042.16   79.72 1147.56   83.02  1295.3   82.81 1423.53   86.26
  1447.3   85.12 1454.21   87.49 1469.36   87.83 1489.93   87.88 1501.76   86.56
#Mann= 3 , 0 , 0
       0     .12       0  768.06     .06       0  801.49     .12       0
#XS Ineff= 2 , 0
          648.01   83.59
Bank Sta=768.06,801.49
Exp/Cntr=.3,.1

Type RM Length L Ch R = 1 ,27493   ,562.97,558.59,527.06
XS GIS Cut Line= 4
 2113778.2968147  235419.2367886 2113773.4620122  235417.9621572
     2113749.288      235411.589 2112125.5528147  234983.5127886
#Sta/Elev= 30
       0    91.6   251.8   92.05  381.74   86.72  423.93   87.59  433.06   89.39
   457.2    88.4  475.72   85.83  498.99   84.58  528.82   85.93   544.1   84.31
  608.82   83.75  667.89   78.26  858.57   76.11  871.83    73.1  883.57   76.17
  922.45   78.33  966.12   82.45  990.13   82.17 1093.85   85.45 1260.78   86.32
 1314.99   88.11  1384.9   88.55 1459.46   86.96 1550.71   89.55 1571.76   87.87
 1604.74   90.56  1666.1   90.61 1686.83   89.92  1698.3   87.84 1709.22   88.36
#Mann= 3 , 0 , 0
       0     .12       0  858.57     .06       0  883.57     .12       0
#XS Ineff= 2 , 0
          726.96   81.41
Bank Sta=858.57,883.57
Exp/Cntr=.3,.1

Type RM Length L Ch R = 1 ,26934   ,396.9,385.51,345.76
XS GIS Cut Line= 3
 2113967.0980166   234698.146908     2113937.099      234697.904
 2112111.5180166   234683.121908
#Sta/Elev= 30
       0    79.8   46.39   79.25  132.12   81.03  250.41   80.93  271.42   79.86
  324.97   82.15  440.02   80.17  554.96    80.8  695.98   74.71  816.97   75.09
  833.93   72.13  849.17   75.08  935.47   76.96 1034.68   76.02 1174.67   77.25
 1202.84   79.35 1312.03   80.61 1328.38   83.43 1347.43    83.5 1364.14   85.29
 1463.35   82.56 1559.07   83.44 1631.65   86.85 1682.25    87.3 1719.68   85.57
 1763.82   87.32 1776.09    89.3 1822.94   87.22 1841.76   84.51 1855.64   87.12
#Mann= 3 , 0 , 0
       0     .12       0  816.97     .06       0  849.17     .12       0
#XS Ineff= 2 , 0
                          941.98           79.66
Bank Sta=816.97,849.17
Exp/Cntr=.3,.1

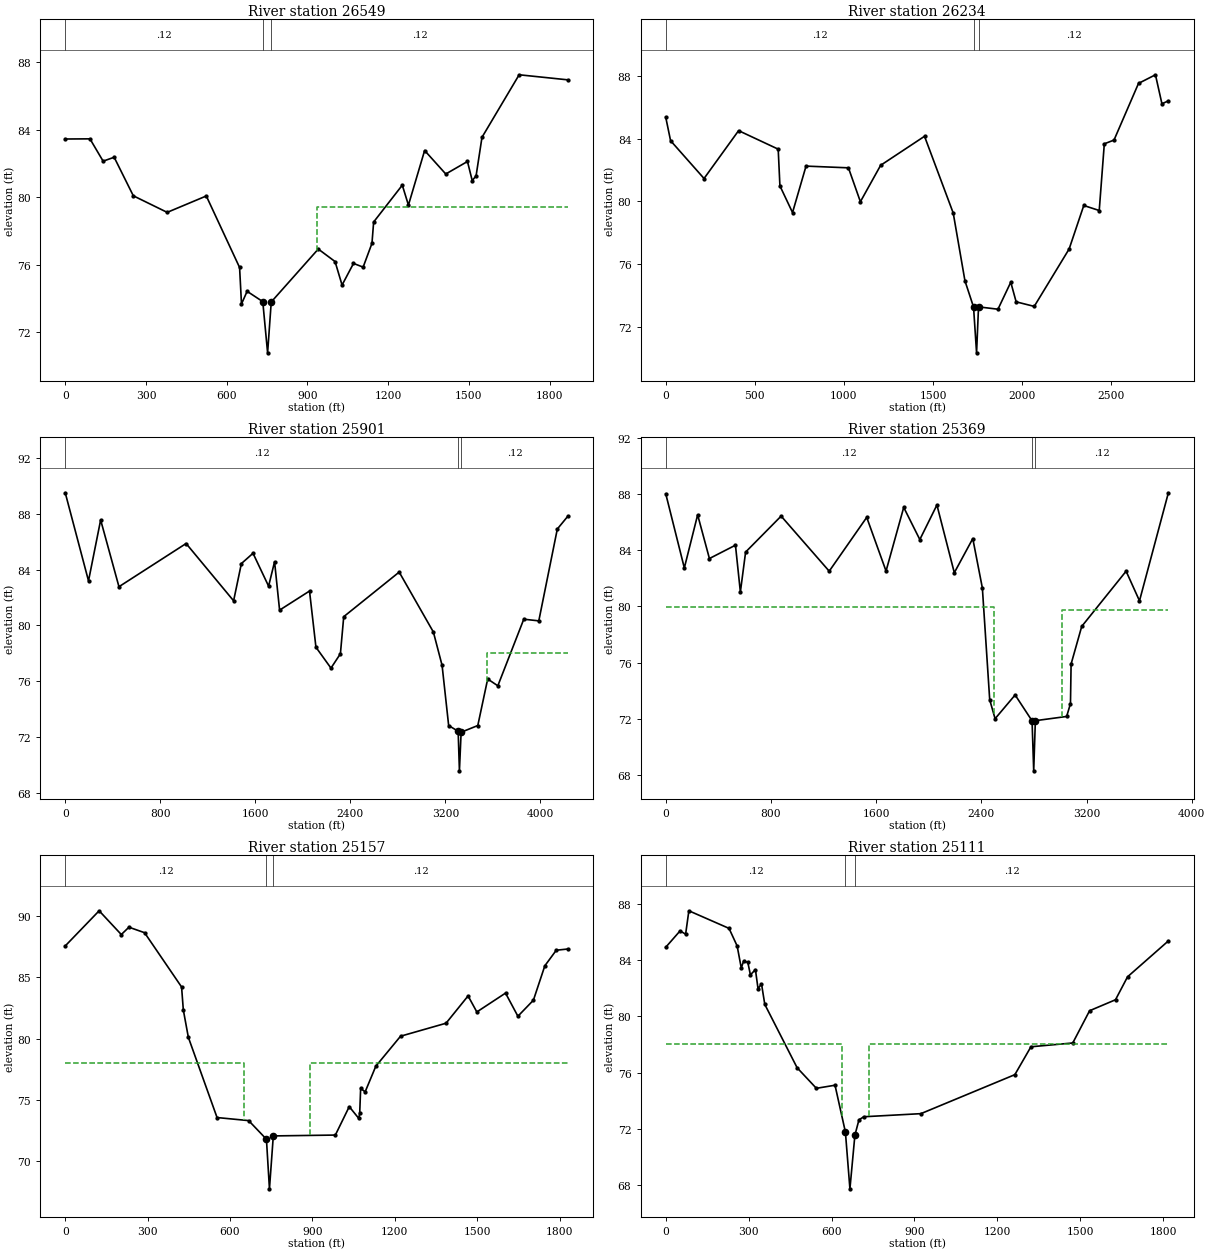
Type RM Length L Ch R = 1 ,26549   ,326.82,314.67,288.7
XS GIS Cut Line= 2
     2113869.487      234126.956     2112066.494      234615.267
#Sta/Elev= 30
       0   83.44   91.84   83.45  140.76   82.13  181.84   82.36  253.05   80.08
  378.89    79.1  524.23   80.07  647.94   75.84  655.01   73.68  675.92   74.43
   734.1   73.82  752.08   70.79   765.6    73.8  940.37   76.93 1002.77   76.19
 1028.81    74.8 1071.28   76.08 1107.09   75.86 1139.95   77.27 1146.15   78.53
 1252.64   80.71 1275.45   79.53 1335.63   82.76 1414.19   81.37 1494.84   82.11
  1512.5   80.98 1526.87   81.26 1548.77   83.54 1686.86   87.24 1867.95   86.94
#Mann= 3 , 0 , 0
       0     .12       0   734.1     .06       0   765.6     .12       0
#XS Ineff= 2 , 0
                          935.15           79.43
Bank Sta=734.1,765.6
Exp/Cntr=.3,.1

Type RM Length L Ch R = 1 ,26234   ,316.28,333.21,337.17
XS GIS Cut Line= 4
 2114690.3993862  233901.0019848     2113364.158      233876.594
     2112051.469      234547.654 2112033.6610215  234556.7576202
#Sta/Elev= 30
       0   85.36    27.1   83.87  214.89   81.46  408.84   84.51  631.06   83.33
  640.73   80.99   711.5   79.29  787.26   82.25 1025.27   82.14 1092.31   79.98
 1205.89    82.3 1452.21   84.15 1613.28   79.26 1679.08   74.94 1727.31   73.27
  1744.3   70.35 1755.28   73.28 1864.41   73.13 1936.25   74.85 1966.41    73.6
 2067.89   73.31 2263.83   76.97 2345.95   79.74 2432.67   79.42 2461.18   83.67
 2515.65   83.91 2653.07   87.52 2748.17   88.07 2784.59   86.22 2820.74   86.41
#Mann= 3 , 0 , 0
       0     .12       0 1727.31     .06       0 1755.28     .12       0
Bank Sta=1727.31,1755.28
Exp/Cntr=.3,.1

Type RM Length L Ch R = 1 ,25901   ,653.89,532.25,441.95
XS GIS Cut Line= 5
     2115985.709      233726.127     2113850.116      233739.861
     2113180.476      233675.965     2112284.356      234051.831
     2112124.106      234473.314
#Sta/Elev= 30
       0   89.52  195.88    83.2  298.11   87.57  452.17   82.78 1017.42   85.88
 1417.29   81.77 1482.72   84.44 1580.74   85.18 1711.86   82.82 1762.09   84.57
 1804.37    81.1 2056.28   82.47 2110.31   78.44  2236.8   76.94 2316.31   77.97
 2344.27   80.63 2811.09   83.83 3098.89   79.53 3172.19   77.14  3227.5   72.82
 3307.48   72.41 3318.13   69.57 3332.48   72.34 3472.79   72.82 3556.04   76.16
 3641.47   75.67  3859.9   80.45 3986.32   80.33 4142.23   86.92    4231   87.84
#Mann= 3 , 0 , 0
       0     .12       0 3307.48     .06       0 3332.48     .12       0
#XS Ineff= 2 , 0
       0                    3550       0      78
Bank Sta=3307.48,3332.48
Exp/Cntr=.3,.1

Type RM Length L Ch R = 1 ,25369   ,187.13,211.83,192.7
XS GIS Cut Line= 5
     2112815.662      230712.952     2112736.924      231622.456
      2112606.52      232918.448     2112226.262      234059.223
     2112127.131      234451.416
#Sta/Elev= 30
       0   88.02  141.31   82.74  242.54   86.52  332.07   83.41   530.1   84.36
  567.51   81.03  607.29   83.87  877.48   86.43 1243.14   82.51 1528.35   86.34
  1675.3   82.52 1809.73   87.05 1932.18   84.76 2062.23   87.22 2194.49    82.4
 2334.99   84.83 2407.88   81.31 2463.65   73.36 2504.49   72.01 2656.97    73.7
 2785.75   71.86 2798.27    68.3 2810.81   71.87 3048.85   72.17  3077.9   73.09
  3082.6    75.9 3163.46   78.58 3501.01   82.51 3602.77    80.4 3822.45   88.09
#Mann= 3 , 0 , 0
       0     .12       0 2785.75     .06       0 2810.81     .12       0
#XS Ineff= 2 , 0
       0 2498.29   79.95 3017.06       0   79.77
Bank Sta=2785.75,2810.81
Exp/Cntr=.3,.1

Type RM Length L Ch R = 1 ,25157   ,45.27,45.71,45
XS GIS Cut Line= 6
 2112340.5671322  232604.3212736     2112374.218      232722.235
     2112383.316      232875.481     2112336.378      233133.266
     2112142.712       233736.42     2112127.282      234393.842
#Sta/Elev= 30
       0   87.57  123.47   90.44  204.18    88.5  231.94    89.1   288.9   88.65
  423.69   84.22     430   82.35  448.33   80.11  552.89   73.56  667.99   73.31
  732.71   71.79   743.7   67.74  757.71   72.06  983.73   72.13 1034.27   74.45
 1068.95   73.49 1072.39   73.91 1075.77   75.94 1092.21   75.66 1131.04   77.75
 1221.13    80.2 1386.76   81.26 1467.05   83.49 1498.91   82.18 1603.41   83.72
 1648.45   81.83 1704.95   83.14  1746.6   85.95 1788.25   87.22 1830.43   87.32
#Mann= 3 , 0 , 0
       0     .12       0  732.71     .06       0  757.71     .12       0
#XS Ineff= 2 , 0
       0  650.68      78  889.65       0   77.98
Bank Sta=732.71,757.71
Exp/Cntr=.5,.3

Type RM Length L Ch R = 1 ,25111   ,50.33,50.15,50
XS GIS Cut Line= 6
 2112310.6610017  232663.2432519     2112338.316      232875.481
     2112322.603      232993.061     2112098.884       233725.76
     2112082.294      233863.219     2112082.294      234443.792
#Sta/Elev= 30
       0    84.9   51.78   86.06   71.95   85.83   83.67   87.49  229.09   86.24
  258.46   84.99  273.36   83.43  281.62    83.9  296.91   83.84  306.46   82.94
  324.62   83.31  334.11   81.95  346.59    82.3  358.54   80.84  475.56   76.34
  545.28   74.88  612.73    75.1  650.36   71.77  666.68   67.74  684.68   71.55
  699.38   72.64  716.78   72.86  923.56   73.08 1263.73   75.85 1321.91   77.83
 1473.35    78.1 1534.28   80.39 1628.06   81.17 1671.68    82.8 1819.48   85.35
#Mann= 3 , 0 , 0
       0     .12       0  650.36     .06       0  684.68     .12       0
#XS Ineff= 2 , 0
       0  637.09      78  734.93       0      78
Bank Sta=650.36,684.68
Exp/Cntr=.5,.3

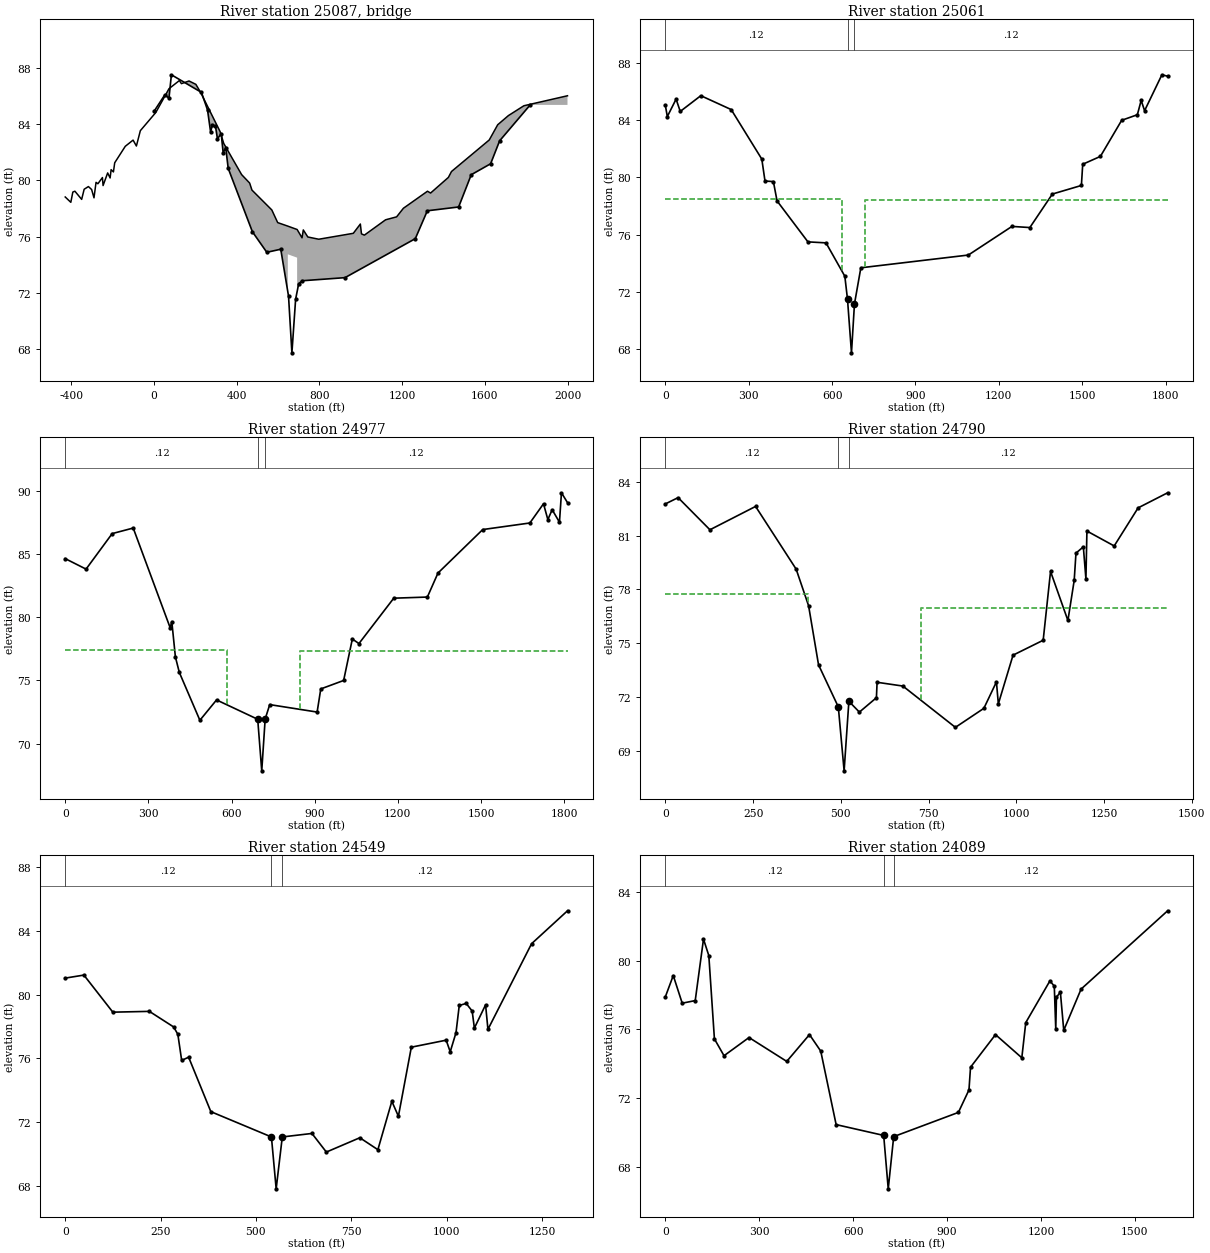
Type RM Length L Ch R = 3 ,25087   ,,,
BEGIN DESCRIPTION:
SR 1728 - 0.7 Mi. N. JCT 1710
END DESCRIPTION:
Bridge Culvert--1,0,-1,-1, 0
Deck Dist Width WeirC Skew NumUp NumDn MinLoCord MaxHiCord MaxSubmerge Is_Ogee
11,27,2.6,0, 60, 60,,,.95,0,0,0,,
    -430 -402.89 -393.21 -383.14 -350.47 -338.36 -317.79 -302.25 -290.77 -280.89
 -271.93 -249.95 -246.86 -224.63 -212.78 -207.94 -196.77 -190.56 -139.45  -101.7
  -85.62  -66.56    8.17   71.98  122.29  132.14  169.04  202.05  224.69  319.45
  336.98  423.39  462.23  473.41  569.48  597.92     647     647     692     692
  715.67  721.84   743.6  796.48  963.76  997.84 1003.31 1017.21  1119.9 1173.28
 1206.11 1322.63 1337.53 1423.66 1438.74  1621.4 1662.23 1713.93 1788.94    2000
   78.81   78.43   79.16   79.22   78.64   79.36   79.55   79.34   78.75   79.85
   79.75   80.19   79.62   80.52   80.16   80.75   80.59   81.24   82.41   82.85
   82.43   83.52   84.81    86.5   87.08   86.86   87.05   86.81   86.25   83.45
   82.61    80.4    79.8    79.3   77.89   76.99   76.74   76.74    76.5    76.5
   75.91   76.47   75.97   75.81   76.23   76.89   76.19    76.1   77.19    77.4
   78.01   79.22   79.09    80.2   80.62   82.86   83.94   84.59   85.29      86
                                                                                
                                                                                
                                                                                
                                                           74.74    74.5
                                                                                
                                                                                
    -430 -402.89 -393.21 -383.14 -350.47 -338.36 -317.79 -302.25 -290.77 -280.89
 -271.93 -249.95 -246.86 -224.63 -212.78 -207.94 -196.77 -190.56 -139.45  -101.7
  -85.62  -66.56    8.17   71.98  122.29  132.14  169.04  202.05  224.69  319.45
  336.98  423.39  462.23  473.41  569.48  597.92     647     647     692     692
  715.67  721.84   743.6  796.48  963.76  997.84 1003.31 1017.21  1119.9 1173.28
 1206.11 1322.63 1337.53 1423.66 1438.74  1621.4 1662.23 1713.93 1788.94    2000
   78.81   78.43   79.16   79.22   78.64   79.36   79.55   79.34   78.75   79.85
   79.75   80.19   79.62   80.52   80.16   80.75   80.59   81.24   82.41   82.85
   82.43   83.52   84.81    86.5   87.08   86.86   87.05   86.81   86.25   83.45
   82.61    80.4    79.8    79.3   77.89   76.99   76.74   76.74    76.5    76.5
   75.91   76.47   75.97   75.81   76.23   76.89   76.19    76.1   77.19    77.4
   78.01   79.22   79.09    80.2   80.62   82.86   83.94   84.59   85.29      86
                                                                                
                                                                                
                                                                                
                                                           74.74    74.5
                                                                                
                                                                                
BR Coef= 1 , 0 , 0 ,, 0 ,,,.8,0,1.2,0,
WSPro=,,,, 1 ,,,, 0 ,,,, 0 ,,,,-1 ,-1 ,-1 , 0 , 0 , 0 , 0 , 0
BR U #Sta/Elev= 30
       0    84.9   51.78   86.06   71.95   85.83   83.67   87.49  229.09   86.24
  258.46   84.99  273.36   83.43  281.62    83.9  296.91   83.84  306.46   82.94
  324.62   83.31  334.11   81.95  346.59    82.3  358.54   80.84  475.56   76.34
  545.28   74.88  612.73    75.1  650.36   71.77  666.68   67.74  684.68   71.55
  699.38   72.64  716.78   72.86  923.56   73.08 1263.73   75.85 1321.91   77.83
 1473.35    78.1 1534.28   80.39 1628.06   81.17 1671.68    82.8 1819.48   85.35
BR U #Mann= 3
       0     .12  650.36    .055  684.68     .12
BR D #Sta/Elev= 30
       0   85.03    7.04   84.24   38.64   85.46    53.6    84.6  127.61    85.7
  236.94   84.73  347.07   81.27  358.52   79.74  388.74    79.7  401.92   78.35
     513   75.49  578.06   75.42  645.77   73.09   655.4   71.48  669.69   67.74
   680.4   71.15  703.39   73.68 1090.21   74.57 1247.13   76.57 1311.49   76.49
 1392.46   78.83 1496.96   79.43 1501.71   80.91 1565.36   81.46 1641.89   83.98
 1698.34   84.37 1712.04   85.37 1724.31   84.65  1786.6   87.16 1807.26   87.06
BR D #Mann= 3
       0     .12   655.4    .055   680.4     .12
BC Design=,, 0 ,, 0 ,,,,,,

Type RM Length L Ch R = 1 ,25061   ,89.16,84.02,88.08
XS GIS Cut Line= 6
 2112255.0312813  232650.2270665     2112281.547      232743.139
      2112274.49      232979.454      2112049.54      233719.239
     2112032.308      233862.017     2112032.308       234417.59
#Sta/Elev= 30
       0   85.03    7.04   84.24   38.64   85.46    53.6    84.6  127.61    85.7
  236.94   84.73  347.07   81.27  358.52   79.74  388.74    79.7  401.92   78.35
     513   75.49  578.06   75.42  645.77   73.09   655.4   71.48  669.69   67.74
   680.4   71.15  703.39   73.68 1090.21   74.57 1247.13   76.57 1311.49   76.49
 1392.46   78.83 1496.96   79.43 1501.71   80.91 1565.36   81.46 1641.89   83.98
 1698.34   84.37 1712.04   85.37 1724.31   84.65  1786.6   87.16 1807.26   87.06
#Mann= 3 , 0 , 0
       0     .12       0   655.4     .06       0   680.4     .12       0
#XS Ineff= 2 , 0
       0  634.81   78.45  716.72       0   78.41
Bank Sta=655.4,680.4
Exp/Cntr=.5,.3

Type RM Length L Ch R = 1 ,24977   ,184.91,187.32,185.44
XS GIS Cut Line= 6
  2112256.996942  232572.9498238     2112181.834      232992.661
     2112152.294      233120.668     2111958.173      233725.188
     2111942.529      233854.804     2111942.529      234343.377
#Sta/Elev= 30
       0   84.64   75.21   83.81  169.42   86.62  245.32   87.06  378.64   79.17
   384.5   79.66   397.5   76.86  411.61   75.64  485.82   71.85  545.96   73.46
  694.46   71.93  709.02   67.85  721.36   71.95  737.81   73.09  908.84    72.5
  921.94   74.33 1004.47      75 1035.82   78.28 1059.69   77.92 1185.27   81.51
 1306.51    81.6 1344.85    83.5 1506.25   86.94  1676.3   87.46 1725.55   88.98
 1741.18   87.73 1756.81   88.51 1783.11   87.52 1790.27   89.85  1812.1   89.07
#Mann= 3 , 0 , 0
       0     .12       0  694.46     .06       0  721.36     .12       0
#XS Ineff= 2 , 0
          582.48   77.45  848.69           77.32
Bank Sta=694.46,721.36
Exp/Cntr=.3,.1

Type RM Length L Ch R = 1 ,24790   ,214,240.85,287.34
XS GIS Cut Line= 3
 2112159.0997736  232668.5502379     2111659.769      233913.675
 2111626.2697736  233997.2082379
#Sta/Elev= 30
       0   82.76   36.34   83.11  127.05   81.32  257.15   82.62  372.74   79.13
  408.25   77.09   436.6    73.8  492.95   71.46  509.48    67.9  523.06   71.77
  552.99   71.17  601.55   71.97  603.44   72.83  676.93   72.62  826.62   70.32
  907.78   71.38  943.58   72.85  949.04   71.63  990.91   74.34 1076.82   75.17
  1097.8      79  1147.3   76.27 1165.21    78.5 1170.27   80.02 1191.29   80.37
 1198.63   78.58 1201.47   81.25  1279.2   80.42 1347.36   82.54 1431.52   83.38
#Mann= 3 , 0 , 0
       0     .12       0  492.95     .06       0  523.06     .12       0
#XS Ineff= 2 , 0
       0  407.21   77.75   728.1       0   76.96
Bank Sta=492.95,523.06
Exp/Cntr=.3,.1

Type RM Length L Ch R = 1 ,24549   ,467,459.59,453.65
XS GIS Cut Line= 3
 2112165.9650454  232527.4699028     2112134.463      232566.298
 2111336.2020454  233550.2009028
#Sta/Elev= 30
       0   81.04   48.95   81.23  124.86    78.9  220.67   78.95  284.34   77.97
   295.3   77.51  305.33   75.87  323.62   76.07  381.81   72.65  540.67   71.06
   553.1    67.8  569.17   71.06  646.93   71.28   684.7   70.11  772.46   71.01
  819.79   70.26  856.41    73.3  873.62   72.36  907.52    76.7  998.85   77.14
 1009.48   76.41 1024.63   77.61 1033.17   79.32 1051.35   79.45 1067.01   78.97
 1072.83    77.9 1102.18   79.36  1108.4   77.82 1222.79    83.2    1317   85.27
#Mann= 3 , 0 , 0
       0     .12       0  540.67     .06       0  569.17     .12       0
Bank Sta=540.67,569.17
Exp/Cntr=.3,.1

Type RM Length L Ch R = 1 ,24089   ,446,447.28,362.66
XS GIS Cut Line= 3
 2111961.6021777  232049.6140481     2110991.127      233289.928
 2110972.6401777  233313.5550481
#Sta/Elev= 30
       0    77.9   25.26   79.14   53.86   77.53   95.46   77.68  121.88   81.26
  138.88    80.3  156.76   75.45  187.44   74.47  267.34   75.53  387.88   74.14
  460.48    75.7  496.48   74.74  545.67   70.46   697.6   69.83  712.14   66.72
  729.57   69.76  936.27   71.17   970.1   72.48  975.06    73.8 1054.84    75.7
 1138.93   74.35 1151.57    76.4 1228.79   78.83 1242.71   78.52 1247.41   76.01
 1249.58   77.87 1262.11   78.18 1272.92   75.95 1328.35   78.35 1604.86   82.91
#Mann= 3 , 0 , 0
       0     .12       0   697.6     .06       0  729.57     .12       0
Bank Sta=697.6,729.57
Exp/Cntr=.3,.1

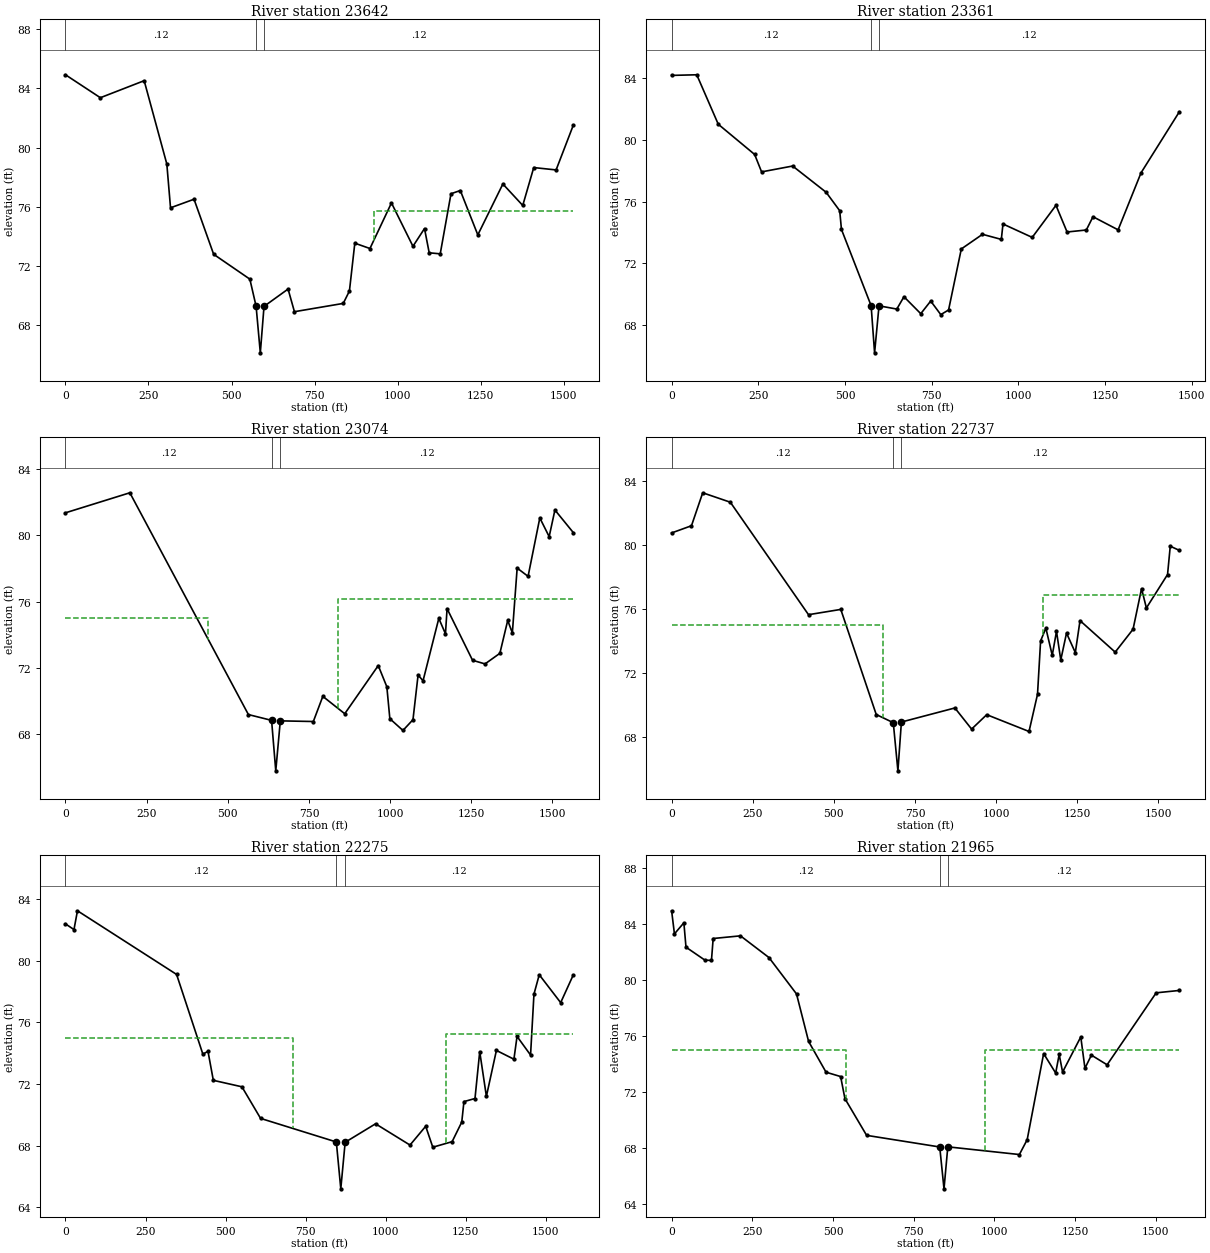
Type RM Length L Ch R = 1 ,23642   ,284,280.76,269.46
XS GIS Cut Line= 3
 2111413.1620989  231837.1597292     2110860.874      233241.686
 2110853.5550989  233260.2987292
#Sta/Elev= 30
       0   84.92  105.01   83.37  236.97   84.52   305.2   78.89  316.34   75.93
  387.14   76.51  446.22   72.79  555.28   71.11  574.07   69.28  586.78   66.13
  597.95   69.27  670.35   70.44  689.52   68.91  836.59   69.47  855.16   70.31
  871.39   73.54  916.96   73.18  981.77   76.26 1046.51   73.33 1081.29   74.53
  1095.4   72.89 1128.66   72.82 1161.04   76.88 1189.12    77.1 1241.86    74.1
 1317.31   77.54 1377.18   76.09 1410.29   78.65 1477.65   78.49 1529.21    81.5
#Mann= 3 , 0 , 0
       0     .12       0  574.07     .06       0  597.95     .12       0
#XS Ineff= 2 , 0
                          928.33           75.69
Bank Sta=574.07,597.95
Exp/Cntr=.3,.1

Type RM Length L Ch R = 1 ,23361   ,215,287.5,242.2
XS GIS Cut Line= 2
     2111111.732      231755.832     2110663.082      233150.026
#Sta/Elev= 30
       0    84.2    72.5   84.24  134.58   81.03  239.49   79.07  259.52   77.94
  349.09   78.32  445.57   76.62  484.87   75.42  489.86   74.21  575.47   69.26
  585.46    66.2  598.25   69.25  649.57   69.04  670.18   69.84  718.66   68.74
  747.36   69.56   776.4   68.68  798.88   68.98  835.62   72.94  896.73   73.89
  951.05   73.56  955.84   74.56 1040.13   73.69  1108.7   75.77 1140.71   74.04
 1196.21   74.17 1215.49   75.03 1287.93   74.18 1354.08   77.88  1464.6   81.84
#Mann= 3 , 0 , 0
       0     .12       0  575.47     .06       0  598.25     .12       0
Bank Sta=575.47,598.25
Exp/Cntr=.3,.1

Type RM Length L Ch R = 1 ,23074   ,275,336.21,294.47
XS GIS Cut Line= 4
 2110911.2312066  231775.2744503  2110896.673837  231812.5314362
     2110392.926      233101.784 2110341.9752066  233232.1834503
#Sta/Elev= 30
       0   81.37  198.25   82.58  563.49   69.18   634.9   68.83  647.78   65.78
  661.79    68.8  763.53   68.76  792.76   70.28   860.3   69.23  963.55   72.14
  989.94   70.86  999.25   68.93 1039.58   68.22 1070.49   68.87 1086.24   71.57
  1101.5   71.22 1150.06   74.99 1170.58   74.06 1175.52   75.58 1254.02   72.46
  1292.5   72.24 1338.19   72.88 1362.37   74.87 1376.64   74.11 1391.43   78.03
 1425.07   77.53 1461.24   81.06 1490.05   79.93 1507.77   81.54 1564.17   80.18
#Mann= 3 , 0 , 0
       0     .12       0   634.9     .06       0  661.79     .12       0
#XS Ineff= 2 , 0
       0     440      75     840       0   76.15
Bank Sta=634.9,661.79
Exp/Cntr=.3,.1

Type RM Length L Ch R = 1 ,22737   ,476,462.46,405.17
XS GIS Cut Line= 2
     2110769.214      231504.974     2110108.298      232923.289
#Sta/Elev= 30
       0   80.73    61.2   81.18   95.82   83.24  180.91   82.65  421.87   75.62
  521.31   75.95  630.59   69.38  683.11   68.87  697.39   65.86  708.11   68.91
  872.95   69.79  924.49   68.47  971.12   69.37 1101.44   68.32 1127.58   70.64
 1137.12   73.98 1153.36   74.78    1173   73.08 1186.11   74.58 1199.28   72.79
 1216.98   74.47 1244.13   73.25  1258.6   75.25 1366.98   73.28 1422.05   74.71
 1448.25   77.25 1463.11   76.04 1528.34   78.13 1536.68    79.9 1564.74   79.64
#Mann= 3 , 0 , 0
       0     .12       0  683.11     .06       0  708.11     .12       0
#XS Ineff= 2 , 0
       0     650      75 1144.94       0   76.84
Bank Sta=683.11,708.11
Exp/Cntr=.3,.1

Type RM Length L Ch R = 1 ,22275   ,298,309.74,294.48
XS GIS Cut Line= 3
 2110224.7245167  231176.1189152     2110209.607      231244.467
 2109882.2055167  232724.6879152
#Sta/Elev= 30
       0   82.39   26.48   82.02   37.39   83.24  347.04   79.11   429.1   73.94
  445.12   74.12  461.79   72.24  551.12   71.82  609.41   69.77  846.02   68.24
  859.95    65.2  873.57   68.22  968.51   69.42 1076.13   68.04 1125.16   69.26
 1147.34    67.9 1207.69   68.26  1237.8   69.53 1244.65   70.86 1279.13   71.06
 1293.92    74.1 1314.75    71.2 1346.04   74.18 1400.74   73.61  1410.5   75.09
 1452.71   73.88 1463.33   77.83 1479.85   79.09 1546.78   77.28    1586   79.07
#Mann= 3 , 0 , 0
       0     .12       0  846.02     .06       0  873.57     .12       0
#XS Ineff= 2 , 0
       0     710      75    1190       0   75.25
Bank Sta=846.02,873.57
Exp/Cntr=.3,.1

Type RM Length L Ch R = 1 ,21965   ,255,298.9,287.46
XS GIS Cut Line= 3
 2109894.0919705  231226.1489517     2109601.757      232711.024
 2109590.1669705  232769.8939517
#Sta/Elev= 30
       0   84.91    8.72   83.26   37.97   84.05   44.53   82.31  102.86   81.39
  123.43   81.36  128.76   82.93  213.33   83.12   301.6   81.57  387.03   78.97
  424.42   75.58  478.54   73.38  523.69   73.07  537.08   71.49  604.26   68.87
  830.82   68.04  844.06   65.05  855.85   68.05 1077.65    67.5 1101.79   68.56
 1152.81   74.71 1190.12   73.32 1200.98   74.65 1211.53   73.39 1267.91    75.9
  1280.8   73.66 1300.77    74.6 1349.48   73.91 1501.58   79.05 1573.38   79.22
#Mann= 3 , 0 , 0
       0     .12       0  830.82     .06       0  855.85     .12       0
#XS Ineff= 2 , 0
       0     540      75     970       0      75
Bank Sta=830.82,855.85
Exp/Cntr=.3,.1

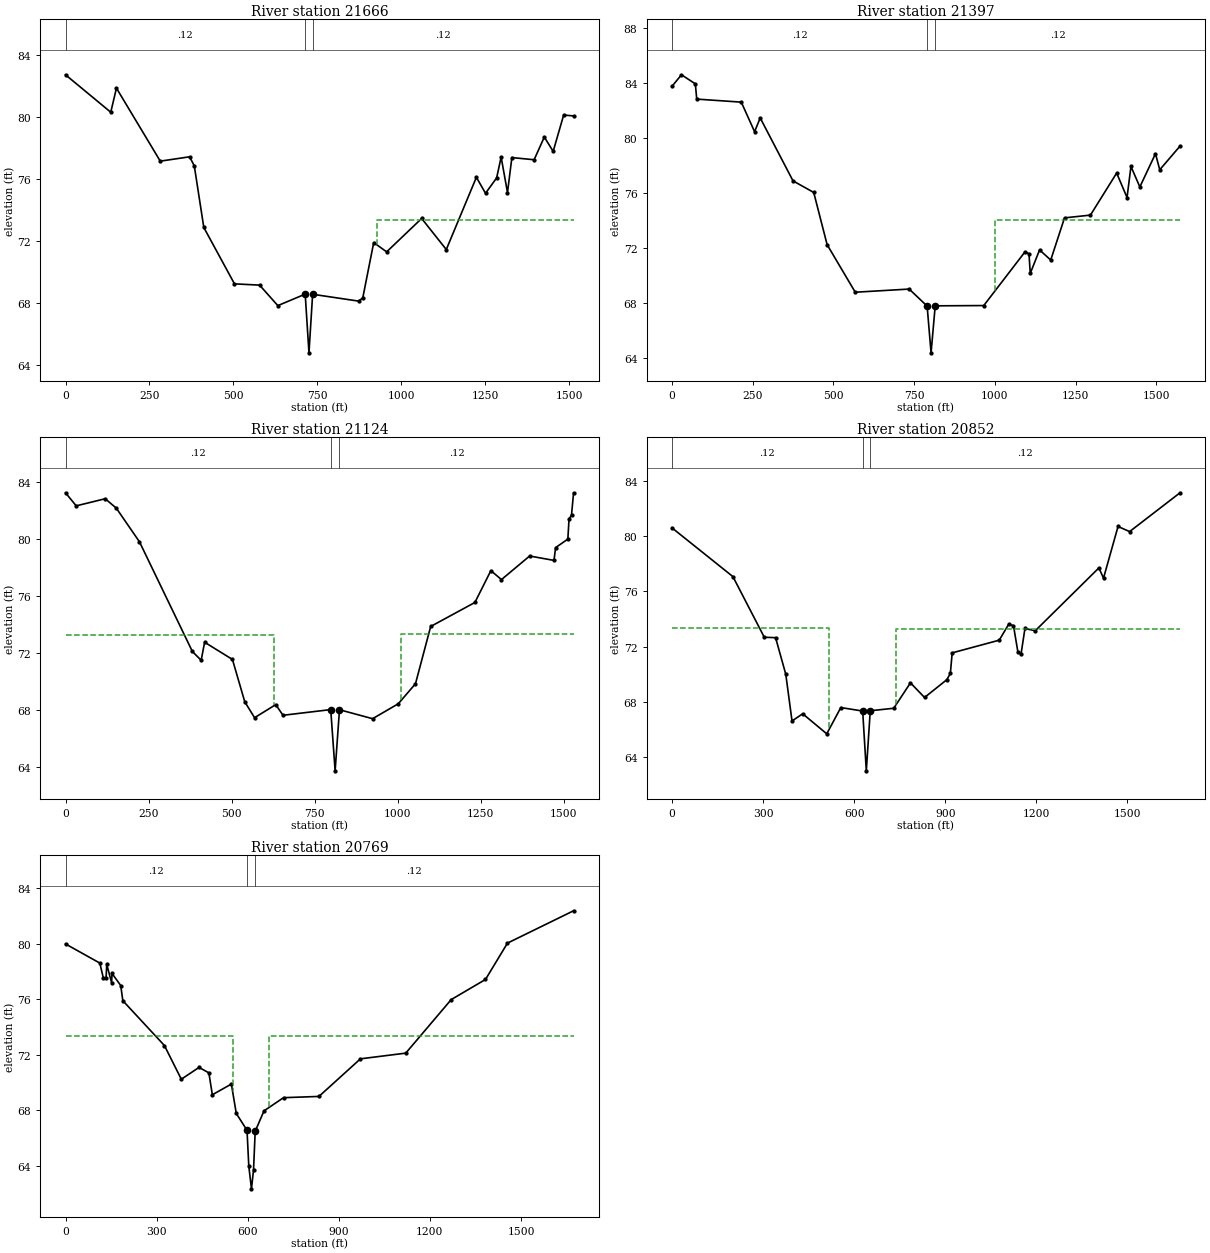
Type RM Length L Ch R = 1 ,21666   ,231,269.14,262.76
XS GIS Cut Line= 2
     2109703.065      231172.104     2109278.536      232624.188
#Sta/Elev= 30
       0    82.7  134.76   80.29  151.68   81.84   282.2   77.14  369.65   77.42
  383.56   76.83  411.84   72.87  503.17   69.24  577.89   69.16  632.29   67.84
  713.77   68.58  724.98    64.8   735.9   68.57  872.91   68.13  885.25   68.34
  917.82    71.9  956.28    71.3 1060.56   73.45  1133.9   71.45 1223.56    76.1
 1250.76   75.07 1283.82   76.06 1297.25    77.4 1316.17   75.12 1329.23   77.37
 1395.44   77.23 1425.78   78.69 1452.21   77.77 1483.45   80.11 1512.87   80.05
#Mann= 3 , 0 , 0
       0     .12       0  713.77     .06       0   735.9     .12       0
#XS Ineff= 2 , 0
                          928.33           73.36
Bank Sta=713.77,735.9
Exp/Cntr=.3,.1

Type RM Length L Ch R = 1 ,21397   ,244,272.81,280.53
XS GIS Cut Line= 2
     2109596.933       231075.62     2108936.017      232503.583
#Sta/Elev= 30
       0   83.79   29.45   84.63   72.37   83.97   76.69   82.86  214.63   82.64
  255.85   80.49  273.28   81.49  374.92   76.91  439.02   76.07  480.51   72.27
  567.64   68.81  734.72   69.04  790.29    67.8  802.46    64.4  815.29   67.82
  965.64   67.84 1092.49   71.72 1105.71   71.62 1109.68   70.18 1138.52   71.89
 1173.05   71.15 1215.79   74.22 1296.03   74.42 1377.27   77.48  1409.4    75.7
 1421.53   77.96  1449.1   76.47 1497.54   78.89 1510.72   77.72 1573.49   79.44
#Mann= 3 , 0 , 0
       0     .12       0  790.29     .06       0  815.29     .12       0
#XS Ineff= 2 , 0
       0                    1000       0   74.05
Bank Sta=790.29,815.29
Exp/Cntr=.3,.1

Type RM Length L Ch R = 1 ,21124   ,247,272.64,342.05
XS GIS Cut Line= 3
 2109482.5714685  230944.0417406      2109466.68      230969.487
 2108672.1054685  232241.7517406
#Sta/Elev= 30
       0   83.27   32.25   82.35  119.46   82.85  152.94   82.19   222.7   79.82
  382.07    72.1  408.51   71.48  418.99   72.75   502.7   71.54  539.84   68.56
  569.36   67.44  633.14   68.36  655.04   67.61  798.73   68.01  811.96    63.7
  825.07      68  924.81   67.37 1002.17   68.42 1053.98   69.83 1099.74   73.86
 1232.92   75.55 1281.03   77.79 1312.91   77.16 1397.77   78.82  1471.1   78.51
 1475.96   79.41 1512.86   80.01  1516.4   81.42 1523.85   81.71    1530   83.24
#Mann= 3 , 0 , 0
       0     .12       0  798.73     .06       0  825.07     .12       0
#XS Ineff= 2 , 0
       0  628.95   73.27 1011.09       0   73.32
Bank Sta=798.73,825.07
Exp/Cntr=.3,.1

Type RM Length L Ch R = 1 ,20852   ,62,82.43,61.99
XS GIS Cut Line= 6
 2109280.3091208  230912.0033936     2108877.761      231425.682
     2108763.507      231553.925     2108393.516        231886.9
     2108258.277      232001.153 2108144.9732221  232132.9017104
#Sta/Elev= 30
       0   80.59  200.72   77.06  304.06   72.67  341.21   72.64  374.81   69.99
  395.36   66.61  430.52   67.13  509.75   65.68  556.02   67.58  628.04   67.33
     640      63  653.04   67.35   730.3   67.53   785.4   69.37  831.79   68.31
  905.21    69.6  916.79   70.05  922.81   71.54 1077.84   72.46 1109.11   73.62
  1124.7   73.51 1139.47   71.57 1149.69   71.47 1162.48   73.31 1196.31   73.14
 1405.98   77.69 1421.21   76.95 1469.03   80.69 1507.17   80.32 1673.14   83.13
#Mann= 3 , 0 , 0
       0     .12       0  628.04     .06       0  653.04     .12       0
#XS Ineff= 2 , 0
       0  516.52   73.32  736.35       0   73.27
Bank Sta=628.04,653.04
Exp/Cntr=.5,.3

Type RM Length L Ch R = 1 ,20769   ,82,82.53,79.92
XS GIS Cut Line= 6
     2109247.382      230854.185      2108832.34       231383.48
     2108718.087      231511.724     2108348.095      231844.698
     2108212.857      231958.952     2108112.594      232075.537
#Sta/Elev= 30
       0   79.97  113.03   78.59   124.4   77.53  133.68   77.53  135.78    78.5
  151.82   77.18  153.24   77.84  181.95   76.97  188.77   75.88  325.68   72.65
   381.4   70.22  439.71   71.07  472.17   70.68  483.53    69.1  546.23   69.87
  562.44   67.75   597.8   66.54  603.59   63.97  612.41   62.32  619.21   63.68
  624.69   66.47  653.77   67.94  717.93   68.89  834.68   68.98  971.34   71.69
 1120.54    72.1 1270.27   75.96 1383.17   77.41 1455.54   80.03 1673.14   82.36
#Mann= 3 , 0 , 0
       0     .12       0   597.8     .06       0  624.69     .12       0
#XS Ineff= 2 , 0
       0  550.85   73.36  671.67       0   73.32
Bank Sta=597.8,624.69
Exp/Cntr=.5,.3