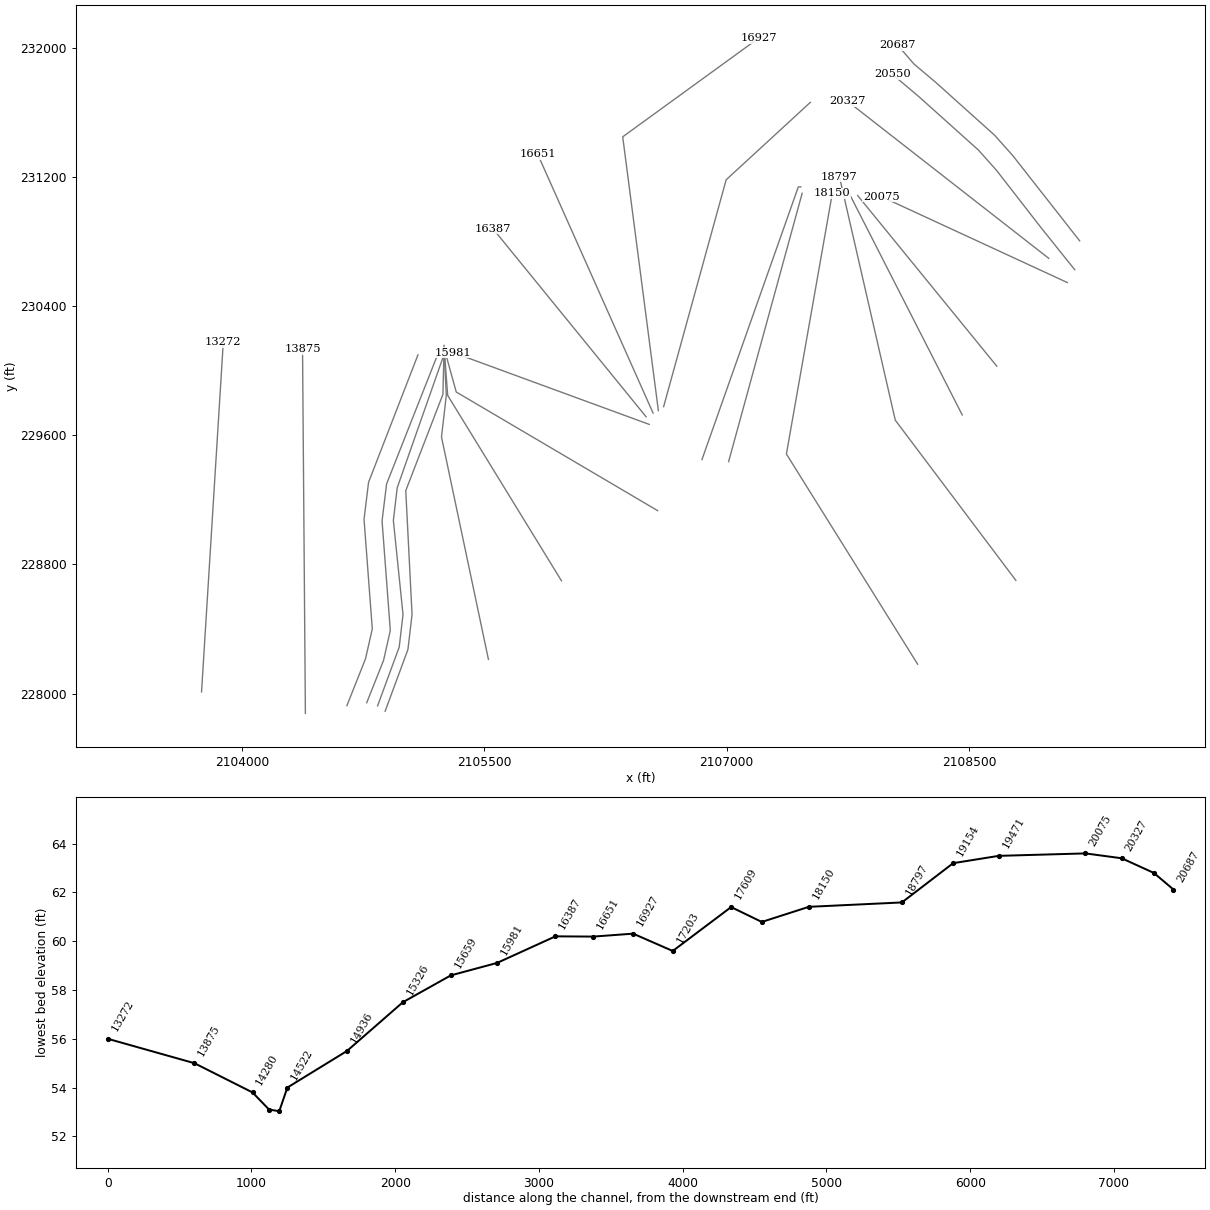
HEC-RAS study welch.prj: Welch Creek - Approximate Study

--- welch.g01 (geometry) --- (continued)

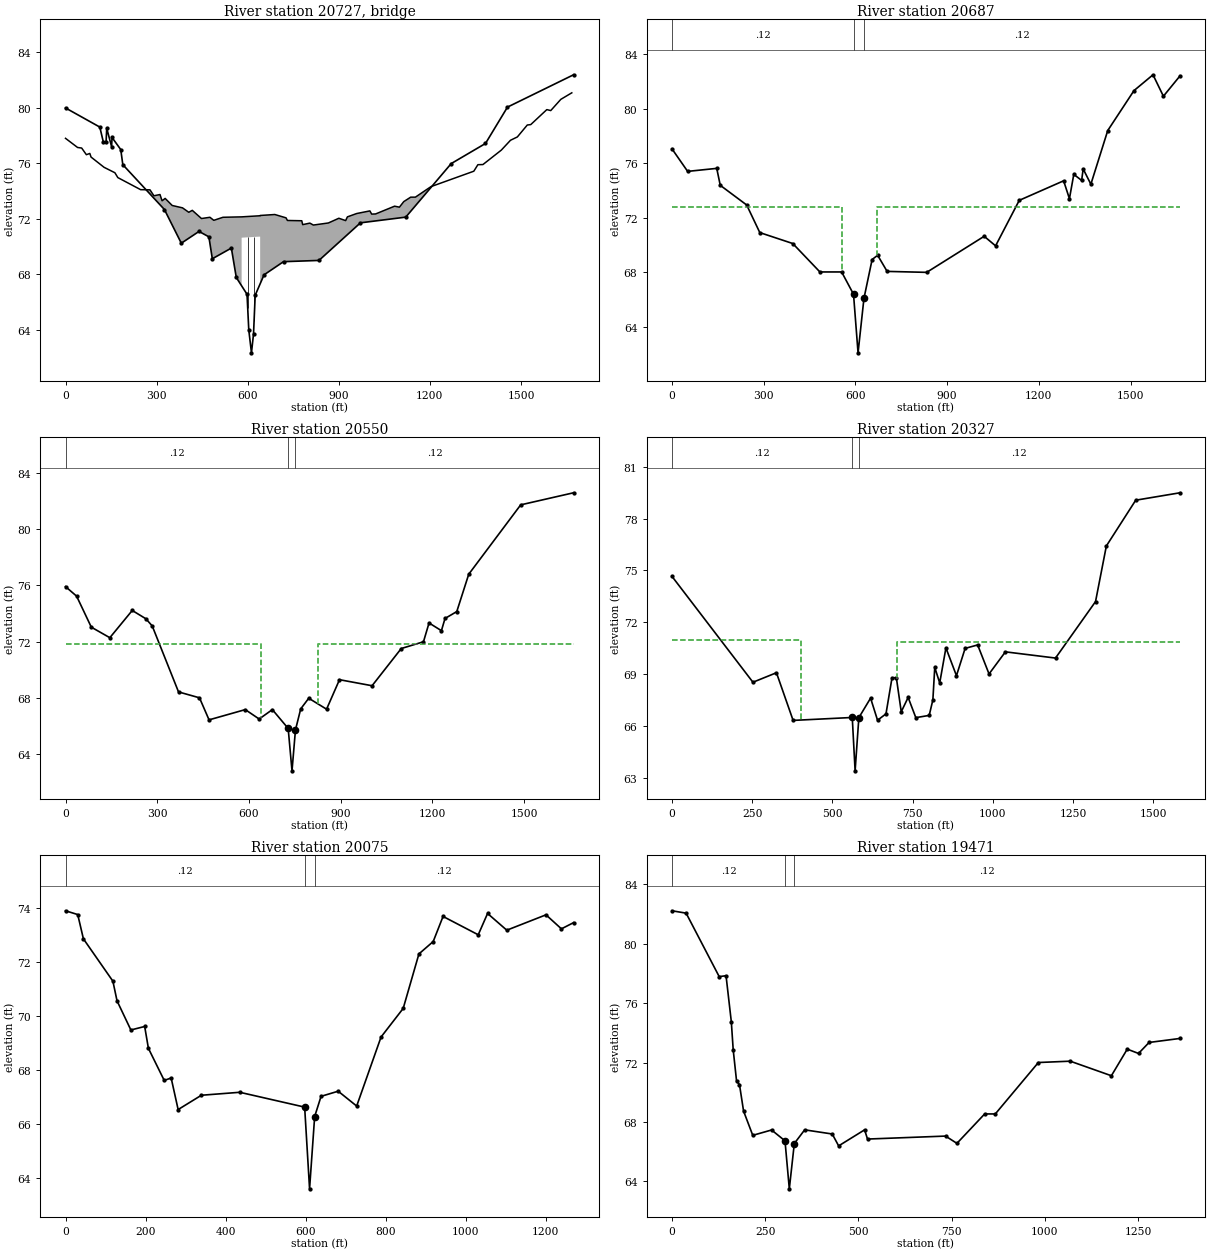
Type RM Length L Ch R = 3 ,20727   ,,,
BEGIN DESCRIPTION:
SR 1710 - 0.4 Mi. W. JCT 1429
END DESCRIPTION:
Bridge Culvert--1,0,-1,-1, 0
Deck Dist Width WeirC Skew NumUp NumDn MinLoCord MaxHiCord MaxSubmerge Is_Ogee
28.1,28.2,2.6,0, 60, 60,72,,.95,0,0,0,,
       0   39.77   53.23   68.75   80.06   84.08  127.05  162.62  172.35  247.42
  278.21  291.14  311.19  318.01  328.18  351.43  385.34  405.94  417.52  447.82
  475.62  488.33  518.48     580     580     641     641  689.26   726.3  730.83
  778.07  781.14  804.75  816.25   865.7  900.22  922.58  928.34  958.87 1002.37
 1008.32 1021.19 1083.74 1099.65 1114.01 1136.77 1152.24 1203.68 1344.66 1358.11
 1374.71 1435.22 1465.47 1488.09 1520.81 1532.21  1585.1 1598.06 1631.26 1667.39
   77.78   77.12   77.08    76.6   76.69   76.43   75.69    75.3   74.95   74.08
   74.07   73.64   73.73   73.28   73.45   72.94   72.77   72.45   72.59      72
   72.09   71.87   72.09   72.12   72.12    72.2   72.22   72.29   72.05   71.86
   71.84   71.56   71.67   71.53   71.68   72.02   71.85   72.12   72.36   72.55
   72.32   72.33   72.89   72.82   73.22   73.54   73.54    74.3   75.41   75.88
   75.89   76.93   77.64   77.88   78.74   78.77   79.85   79.78   80.59   81.06
                                                                                
                                                                                
                                   70.62    70.7
                                                                                
                                                                                
                                                                                
       0   39.77   53.23   68.75   80.06   84.08  127.05  162.62  172.35  247.42
  278.21  291.14  311.19  318.01  328.18  351.43  385.34  405.94  417.52  447.82
  475.62  488.33  518.48     580     580     641     641  689.26   726.3  730.83
  778.07  781.14  804.75  816.25   865.7  900.22  922.58  928.34  958.87 1002.37
 1008.32 1021.19 1083.74 1099.65 1114.01 1136.77 1152.24 1203.68 1344.66 1358.11
 1374.71 1435.22 1465.47 1488.09 1520.81 1532.21  1585.1 1598.06 1631.26 1667.39
   77.78   77.12   77.08    76.6   76.69   76.43   75.69    75.3   74.95   74.08
   74.07   73.64   73.73   73.28   73.45   72.94   72.77   72.45   72.59      72
   72.09   71.87   72.09   72.12   72.12    72.2   72.22   72.29   72.05   71.86
   71.84   71.56   71.67   71.53   71.68   72.02   71.85   72.12   72.36   72.55
   72.32   72.33   72.89   72.82   73.22   73.54   73.54    74.3   75.41   75.88
   75.89   76.93   77.64   77.88   78.74   78.77   79.85   79.78   80.59   81.06
                                                                                
                                                                                
                                   70.62    70.7
                                                                                
                                                                                
                                                                                
Pier Skew, UpSta & Num, DnSta & Num=,600, 2 ,600, 2 , 0 , 0 , 0 ,,
       1       1
       0      71
       1       1
       0      71
Pier Skew, UpSta & Num, DnSta & Num=,621, 2 ,621, 2 , 0 , 0 , 0 ,,
       1       1
       0      71
       1       1
       0      71
BR Coef= 1 , 0 , 0 ,, 0 ,,,.8,-1,1.2,0,
WSPro=,,,, 1 ,,,, 0 ,,,, 0 ,,,,-1 ,-1 ,-1 , 0 , 0 , 0 , 0 , 0
BR U #Sta/Elev= 30
       0   79.97  113.03   78.59   124.4   77.53  133.68   77.53  135.78    78.5
  151.82   77.18  153.24   77.84  181.95   76.97  188.77   75.88  325.68   72.65
   381.4   70.22  439.71   71.07  472.17   70.68  483.53    69.1  546.23   69.87
  562.44   67.75   597.8   66.54  603.59   63.97  612.41   62.32  619.21   63.68
  624.69   66.47  653.77   67.94  717.93   68.89  834.68   68.98  971.34   71.69
 1120.54    72.1 1270.27   75.96 1383.17   77.41 1455.54   80.03 1673.14   82.36
BR U #Mann= 3
       0     .12   597.8    .055  624.69     .12
BR D #Sta/Elev= 30
       0   77.05   51.26    75.4  146.41   75.62  157.95   74.38  244.36   72.94
  287.29   70.92  395.12   70.12  483.86   68.04   554.9   68.04  593.78   66.41
  608.61   62.12  627.86    66.1  654.63   68.95  672.69   69.26  703.69   68.08
  833.06   68.01 1021.14   70.65 1058.43   69.95 1135.84   73.28 1280.98   74.71
 1299.95    73.4 1314.19   75.18 1339.93   74.74 1344.86   75.58 1370.07   74.46
 1425.29   78.39 1511.01   81.31  1573.3   82.47 1607.32    80.9 1661.64   82.39
BR D #Mann= 3
       0     .12  593.78    .055  627.86     .12
BC Design=,, 0 ,, 0 ,,,,,,

Type RM Length L Ch R = 1 ,20687   ,143,136.41,136.15
XS GIS Cut Line= 6
     2109185.064      230804.021     2108770.022      231333.316
      2108658.75      231458.213     2108293.607      231786.124
     2108158.368      231900.377     2108058.106      232016.962
#Sta/Elev= 30
       0   77.05   51.26    75.4  146.41   75.62  157.95   74.38  244.36   72.94
  287.29   70.92  395.12   70.12  483.86   68.04   554.9   68.04  593.78   66.41
  608.61   62.12  627.86    66.1  654.63   68.95  672.69   69.26  703.69   68.08
  833.06   68.01 1021.14   70.65 1058.43   69.95 1135.84   73.28 1280.98   74.71
 1299.95    73.4 1314.19   75.18 1339.93   74.74 1344.86   75.58 1370.07   74.46
 1425.29   78.39 1511.01   81.31  1573.3   82.47 1607.32    80.9 1661.64   82.39
#Mann= 3 , 0 , 0
       0     .12       0  593.78     .06       0  627.86     .12       0
#XS Ineff= 2 , 0
       0  554.95   72.82  669.62       0   72.82
Bank Sta=593.78,627.86
Exp/Cntr=.5,.3

Type RM Length L Ch R = 1 ,20550   ,207,223.24,245.65
XS GIS Cut Line= 6
  2109154.147575  230625.5555268     2108945.529      230886.328
     2108670.389      231240.746     2108559.117      231365.642
     2108193.974      231693.553 2108025.3008444  231836.0519392
#Sta/Elev= 30
       0   75.92   36.29   75.24   84.41   73.03  144.99   72.28  218.29   74.22
  262.78   73.63  283.59   73.12  369.63   68.42   438.2      68  469.48   66.43
  587.97   67.16   633.4   66.49  676.53   67.16  728.28   65.82   740.8    62.8
  752.09   65.71  769.26   67.21  795.54   67.97  853.85   67.19  896.11   69.29
 1002.68   68.86 1098.11   71.51 1170.77   71.99 1189.02   73.33  1229.5   72.78
 1241.25   73.65 1279.71   74.14 1318.83    76.8  1488.8   81.74 1661.64    82.6
#Mann= 3 , 0 , 0
       0     .12       0  728.28     .06       0  752.09     .12       0
#XS Ineff= 2 , 0
       0  639.15   71.86  824.78       0   71.82
Bank Sta=728.28,752.09
Exp/Cntr=.3,.1

Type RM Length L Ch R = 1 ,20327   ,182,252.35,242.39
XS GIS Cut Line= 4
 2108993.8773036   230695.565942 2108970.2339554  230714.0319131
     2107793.341      231633.211 2107746.0543036   231670.142942
#Sta/Elev= 30
       0   74.66  252.34   68.53  325.59   69.08  377.55   66.32  561.87   66.49
  570.74    63.4  582.41   66.48  618.98   67.61  640.66   66.33  666.98    66.7
  685.69   68.78  699.24    68.8  714.52   66.82  736.02   67.65  759.95   66.48
  801.64   66.61  813.11   67.51  818.94   69.39  834.41   68.49  853.78   70.52
  886.61   68.91  913.58   70.49  952.65   70.69  988.15   69.01  1039.1   70.29
 1195.28   69.93 1320.03    73.2 1353.76   76.42 1445.25   79.07 1583.31    79.5
#Mann= 3 , 0 , 0
       0     .12       0  561.87     .06       0  582.41     .12       0
#XS Ineff= 2 , 0
       0  403.22   70.97     700       0   70.87
Bank Sta=561.87,582.41
Exp/Cntr=.3,.1

Type RM Length L Ch R = 1 ,20075   ,552,603.36,379.54
XS GIS Cut Line= 3
 2109108.9986233   230545.577925     2108972.852      230608.539
 2107956.8126233   231078.406925
#Sta/Elev= 30
       0   73.91   30.56   73.77    44.7   72.87  118.39    71.3  128.77   70.57
  163.34   69.49  197.83   69.62  207.14   68.81  246.65   67.62  263.99   67.71
  281.43   66.54   339.5   67.07  435.47   67.18  597.55   66.63  609.83    63.6
  622.55   66.28  638.54   67.03  681.31   67.22  727.54   66.67  788.46   69.23
  843.79   70.29  883.05   72.31  918.76   72.77  943.38    73.7 1031.28   73.02
  1054.6   73.81 1102.65   73.19 1200.57   73.76 1239.12   73.24 1269.43   73.47
#Mann= 3 , 0 , 0
       0     .12       0  597.55     .06       0  622.55     .12       0
Bank Sta=597.55,622.55
Exp/Cntr=.3,.1

Type RM Length L Ch R = 1 ,19471   ,303,317.14,209.06
XS GIS Cut Line= 3
 2108671.9829119  230027.8362072     2108640.403      230066.601
 2107811.2589119  231084.3872072
#Sta/Elev= 30
       0   82.21   37.94   82.05  126.68   77.78  145.04   77.84  159.16   74.75
  164.23   72.86  173.31   70.74  181.07   70.52  192.06   68.73  216.72    67.1
  267.19   67.46  303.17   66.73  314.76    63.5  328.17   66.55  355.96   67.47
  429.92   67.19  447.07   66.39  516.68   67.47  524.52   66.85  733.89   67.05
  764.35   66.56  838.82   68.54  867.31   68.54   982.8      72 1068.26   72.09
 1178.67   71.11 1221.26    72.9 1251.45   72.61 1279.81   73.35 1362.77   73.62
#Mann= 3 , 0 , 0
       0     .12       0  303.17     .06       0  328.17     .12       0
Bank Sta=303.17,328.17
Exp/Cntr=.3,.1

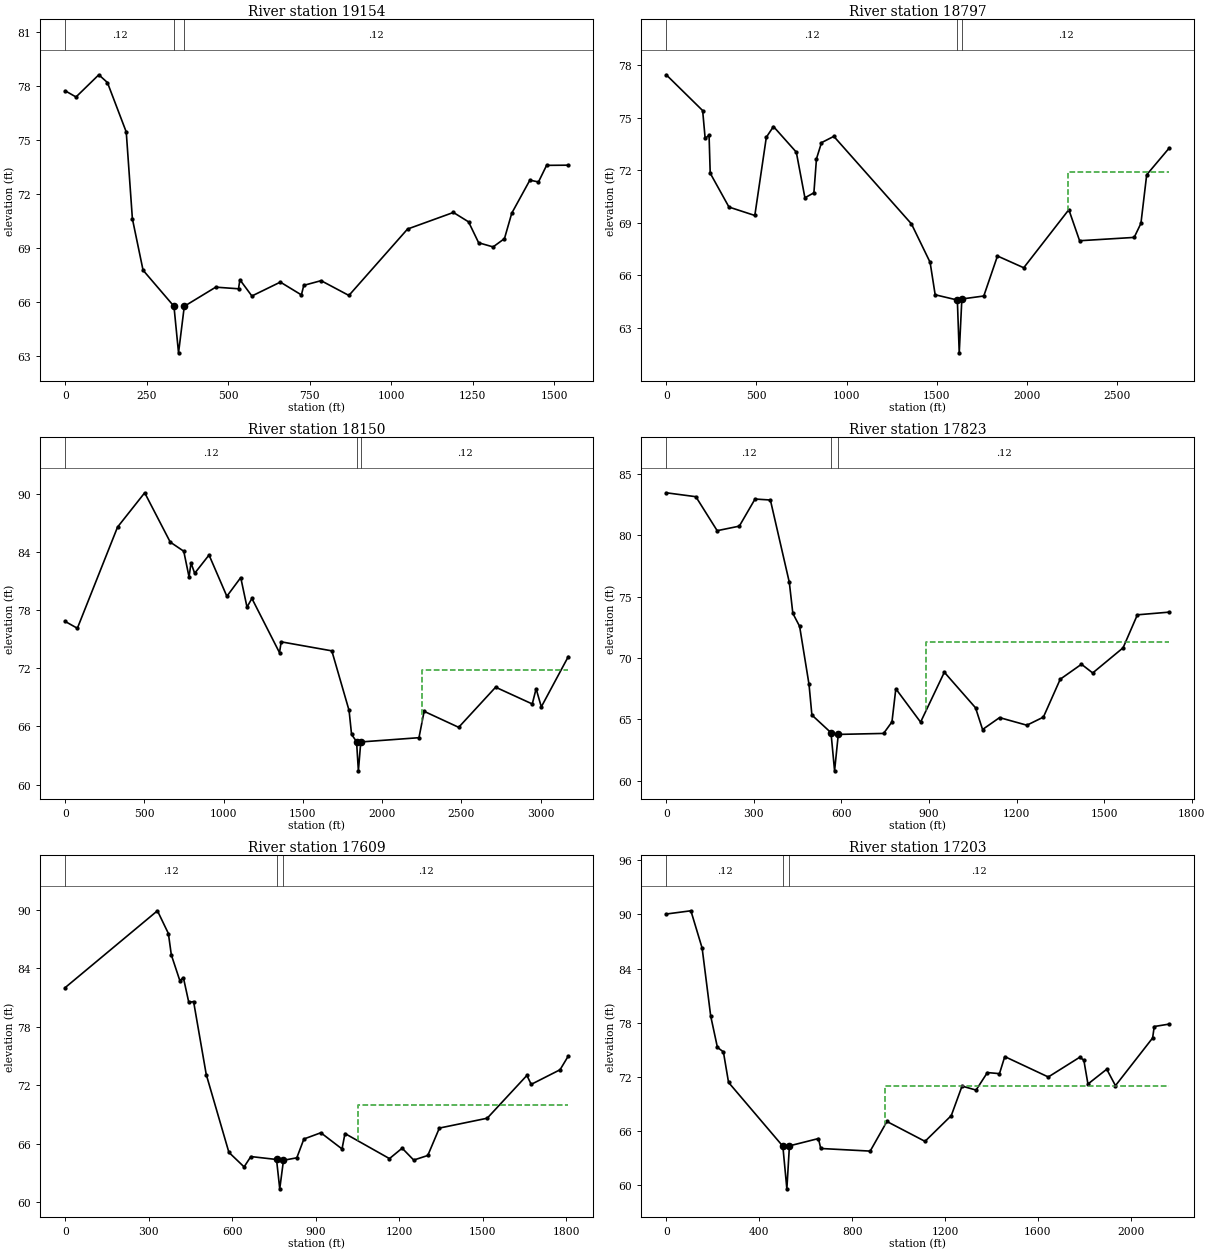
Type RM Length L Ch R = 1 ,19154   ,346,356.84,246.21
XS GIS Cut Line= 3
 2108458.2165822  229725.4428118     2108449.131       229743.26
 2107756.8855822  231100.7808118
#Sta/Elev= 30
       0   77.72   33.02   77.38  102.98   78.61  129.39   78.18  187.18   75.44
  206.02   70.63  238.76   67.78  333.62   65.78  347.65    63.2  365.33   65.78
  461.83   66.84   531.7   66.75  535.96   67.25  572.76   66.35   660.1   67.12
   724.7   66.41  732.02   66.94  785.11    67.2   870.5   66.38 1050.45   70.06
 1191.19   70.98 1237.66   70.46 1268.65    69.3 1313.04   69.07 1347.89   69.53
 1370.31   70.94 1425.88   72.77  1452.3   72.67 1477.15   73.59 1543.83    73.6
#Mann= 3 , 0 , 0
       0     .12       0  333.62     .06       0  365.33     .12       0
Bank Sta=333.62,365.33
Exp/Cntr=.3,.1

Type RM Length L Ch R = 1 ,18797   ,621,647.47,428.54
XS GIS Cut Line= 6
 2108789.9782197  228701.0888227     2108043.816      229693.165
     2107715.921      231123.152 2107706.9810412  231162.1401666
 2107700.2760721  231191.3812916 2107698.0410824  231201.1283332
#Sta/Elev= 30
       0   77.44  201.84    75.4  215.82   73.81  237.37      74  243.82   71.83
  347.75    69.9  491.05   69.42  554.86   73.88  594.44   74.49  721.01   73.03
  768.71   70.43  818.46   70.71   832.8   72.65  860.62   73.57  928.91   73.93
 1359.26   68.94 1462.65   66.75 1490.77    64.9 1613.65    64.6 1624.16   61.59
 1638.65   64.66 1760.23   64.83 1836.08   67.11 1981.69   66.44  2231.7   69.75
 2291.33   67.98 2593.88   68.17  2631.3   68.97 2663.22   71.74 2788.46   73.27
#Mann= 3 , 0 , 0
       0     .12       0 1613.65     .06       0 1638.65     .12       0
#XS Ineff= 2 , 0
                         2225.26           71.91
Bank Sta=1613.65,1638.65
Exp/Cntr=.3,.1

Type RM Length L Ch R = 1 ,18150   ,329,327.17,265.96
XS GIS Cut Line= 5
   2108182.11956  228181.8371402 2108179.4727067  228186.0790935
     2108174.179      228194.563      2107369.81      229483.677
 2107654.1182839  231099.2710018
#Sta/Elev= 30
       0   76.82   76.42   76.12     330   86.56  501.37    90.1  662.63   85.01
  747.89   84.07  781.35   81.41  793.64   82.86  816.85   81.79  907.43   83.68
 1019.96   79.42 1107.56   81.35 1147.08    78.3 1177.95    79.2 1352.24    73.6
 1362.74   74.72 1682.38   73.79 1791.23   67.64 1807.02   65.16 1838.46   64.43
 1850.01   61.41 1865.12   64.39 2232.42   64.83 2264.96   67.55 2482.97    65.9
 2716.13   70.04 2947.42   68.31  2971.7   69.88 3004.57   68.01  3174.9    73.2
#Mann= 3 , 0 , 0
       0     .12       0 1838.46     .06       0 1865.12     .12       0
#XS Ineff= 2 , 0
       0                    2250       0   71.84
Bank Sta=1838.46,1865.12
Exp/Cntr=.3,.1

Type RM Length L Ch R = 1 ,17823   ,129,213.52,101.29
XS GIS Cut Line= 4
 2107012.1352976  229436.5946071 2107013.4560813  229441.4170059
      2107020.06      229465.529 2107467.3642976  231098.7106071
#Sta/Elev= 30
       0   83.46  101.49   83.14  174.49   80.37  250.33   80.74  304.21   82.95
  356.79   82.87  421.63   76.16  433.72   73.63  456.95   72.57  489.14   67.84
  499.01   65.34  564.42    63.9  576.71   60.79  589.42   63.76  744.61   63.84
  773.28   64.78  786.53   67.48  871.34   64.76  952.71   68.83 1059.58   65.93
  1083.7   64.16 1141.92   65.13 1235.46   64.51 1292.06   65.17 1349.76   68.26
 1422.48   69.48 1461.01   68.77 1565.03   70.82    1614   73.51 1723.33   73.73
#Mann= 3 , 0 , 0
       0     .12       0  564.42     .06       0  589.42     .12       0
#XS Ineff= 2 , 0
       0                     890       0   71.27
Bank Sta=564.42,589.42
Exp/Cntr=.3,.1

Type RM Length L Ch R = 1 ,17609   ,376,406.09,386.72
XS GIS Cut Line= 4
 2106847.0438722  229449.0706793     2107443.529      231138.231
     2107454.116      231138.231     2107459.116      231138.231
#Sta/Elev= 30
       0   82.04   331.1   89.91  370.44   87.58  380.98   85.39  411.44   82.76
   424.4   83.05  443.72   80.52  460.99    80.6  506.45   73.12   587.8   65.14
  642.44   63.65  666.64   64.71   758.9   64.41  770.43    61.4   783.9   64.33
  831.73   64.58  857.19   66.51  918.05   67.15  994.17   65.49 1004.76   67.07
 1164.56    64.5 1210.17   65.57 1251.65   64.35 1302.18   64.82  1343.8   67.63
 1515.63   68.64 1658.24   73.03 1673.62   72.11 1777.27   73.61 1806.97   75.02
#Mann= 3 , 0 , 0
       0     .12       0   758.9     .06       0   783.9     .12       0
#XS Ineff= 2 , 0
       0                    1050       0      70
Bank Sta=758.9,783.9
Exp/Cntr=.3,.1

Type RM Length L Ch R = 1 ,17203   ,240,275.68,333.37
XS GIS Cut Line= 4
 2106609.8328154  229776.8921594     2106996.798      231182.185
     2107510.294      231654.817 2107517.6517701  231661.5892389
#Sta/Elev= 30
       0   90.04  106.17    90.4  154.59   86.26  191.42   78.74  220.34   75.27
  246.07   74.77  268.23   71.39  501.98   64.32  519.28    59.6  530.31   64.36
  655.13   65.17   665.2   64.07  877.94   63.78  950.05   67.06 1113.98   64.86
    1227   67.71 1273.37   70.98 1333.72   70.54 1382.46   72.48 1434.47   72.36
  1457.3   74.25 1644.64   71.99 1779.58   74.17 1797.63   73.86 1815.34   71.21
 1896.29   72.85 1933.77   71.03 2093.76   76.31 2100.71   77.58 2165.49   77.85
#Mann= 3 , 0 , 0
       0     .12       0  501.98     .06       0  530.31     .12       0
#XS Ineff= 2 , 0
       0                     940       0      71
Bank Sta=501.98,530.31
Exp/Cntr=.3,.1

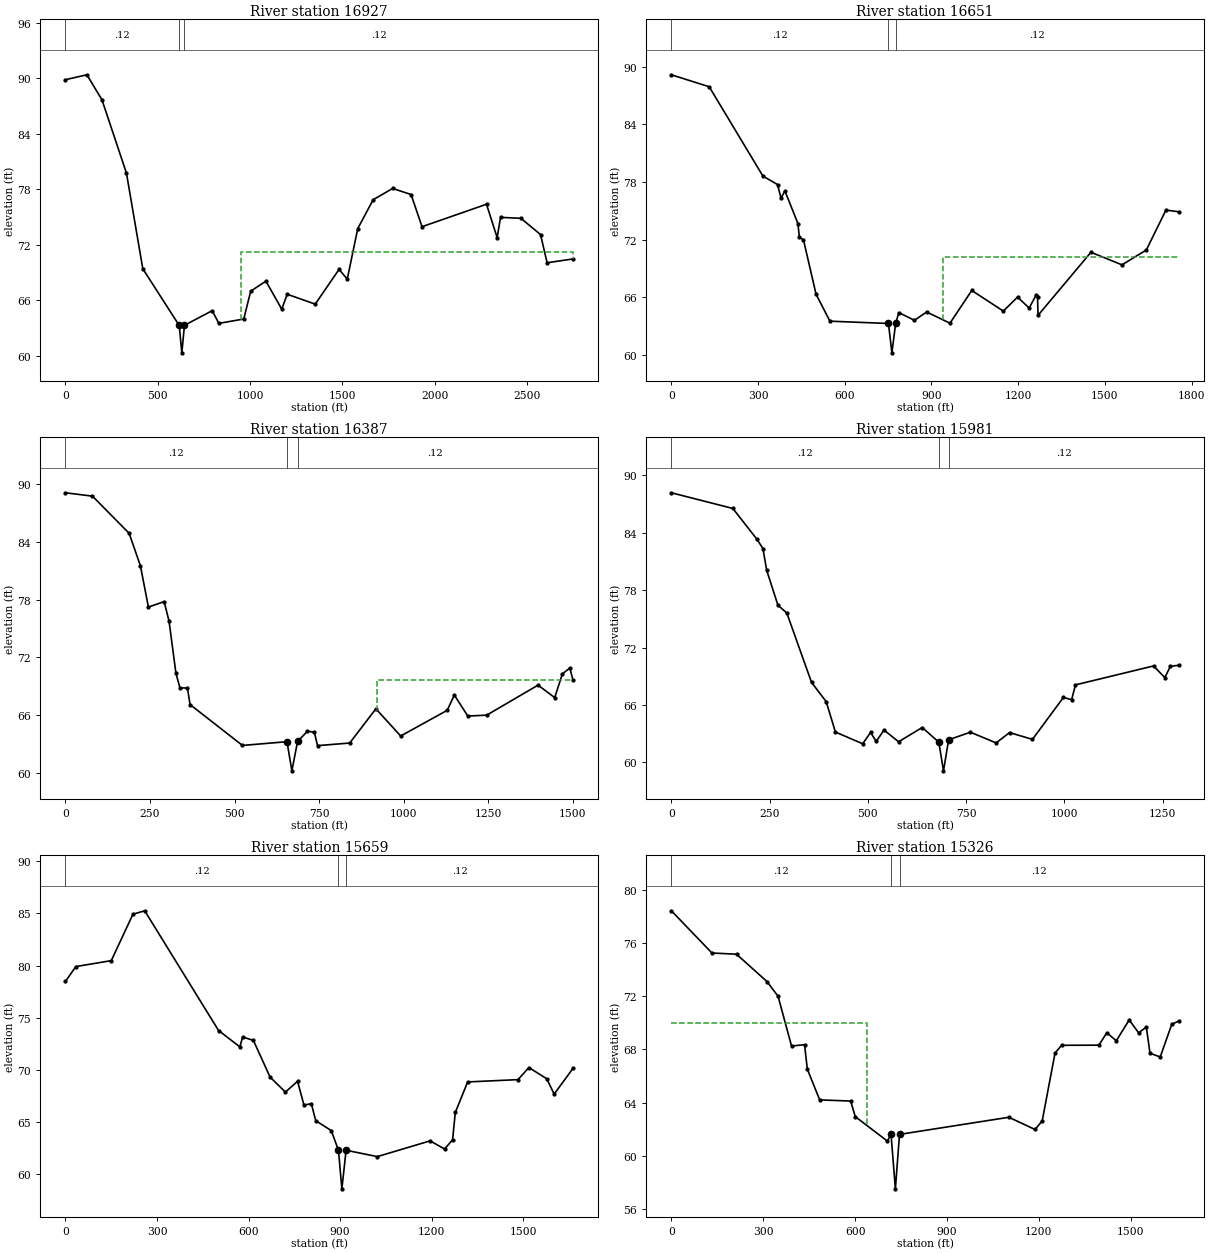
Type RM Length L Ch R = 1 ,16927   ,222,276.33,284.21
XS GIS Cut Line= 4
 2106577.3543278  229752.3765039     2106575.418      229767.251
     2106356.576      231448.353 2107196.3910635  232058.4151595
#Sta/Elev= 30
       0   89.87  115.97    90.4  197.42    87.7  330.17   79.76  418.68   69.41
  615.94   63.27  630.03   60.31  644.29   63.29  794.53   64.87  830.49    63.5
  965.36   63.97 1003.03   66.98 1085.31   68.07  1171.1   65.04 1200.66   66.65
 1352.43   65.58 1481.42   69.34 1525.98   68.29 1582.75   73.76 1666.23   76.88
 1771.92    78.1 1871.49   77.44 1930.73   73.96    2280   76.39 2337.55   72.78
 2355.99   74.97 2466.11   74.87 2572.45   73.11 2608.07   70.06  2748.3   70.47
#Mann= 3 , 0 , 0
       0     .12       0  615.94     .06       0  644.29     .12       0
#XS Ineff= 2 , 0
       0                     950       0    71.2
Bank Sta=615.94,644.29
Exp/Cntr=.3,.1

Type RM Length L Ch R = 1 ,16651   ,215,264.12,277.68
XS GIS Cut Line= 4
 2106544.4686645  229737.6694281 2106542.4337763  229742.2366188
     2106538.364      229751.371 2105829.8646645  231341.5574281
#Sta/Elev= 30
       0   89.17  130.97   87.92  316.75   78.61  367.31   77.73  379.42    76.3
  392.76   77.07  437.82   73.67  442.69   72.27  457.13   71.96   500.6    66.3
  548.56   63.49  751.05   63.25     763   60.19  776.05   63.28  787.07   64.38
  841.04   63.58  883.22   64.45  963.86   63.28 1039.35   66.69 1148.56   64.54
 1197.73      66  1237.9   64.86 1262.44   66.24 1266.88   65.96 1268.66    64.1
 1451.64   70.67 1559.07   69.36 1643.25   70.91 1711.16   75.07 1755.88   74.89
#Mann= 3 , 0 , 0
       0     .12       0  751.05     .06       0  776.05     .12       0
#XS Ineff= 2 , 0
       0                     940       0   70.15
Bank Sta=751.05,776.05
Exp/Cntr=.3,.1

Type RM Length L Ch R = 1 ,16387   ,323,406.18,472.39
XS GIS Cut Line= 2
     2106501.311      229714.317     2105553.799      230878.857
#Sta/Elev= 30
       0    89.1   79.76   88.75  188.28   84.89  221.66   81.51  245.33   77.22
  291.83   77.79  306.43   75.75  326.78   70.33  338.65   68.83  360.72    68.8
  368.55   67.09   523.5   62.84   655.3   63.23  669.72    60.2  686.54   63.25
  715.74   64.32  736.16   64.21  745.61   62.82  840.84   63.09  918.23   66.65
  991.56   63.82 1129.25   66.49 1150.32   68.08 1190.12   65.89 1246.21   65.99
    1398   69.11 1447.13   67.81  1469.9   70.27 1492.04   70.89 1501.31   69.62
#Mann= 3 , 0 , 0
       0     .12       0   655.3     .06       0  686.54     .12       0
#XS Ineff= 2 , 0
                          922.87            69.6
Bank Sta=655.3,686.54
Exp/Cntr=.3,.1

Type RM Length L Ch R = 1 ,15981   ,332,321.58,299.36
XS GIS Cut Line= 3
   2106520.58692  229667.1874708     2106464.257       229687.85
   2105308.40692  230111.8304708
#Sta/Elev= 30
       0   88.19  156.43   86.55  217.88   83.32  232.92   82.36  242.58   80.07
  271.11   76.43  293.77   75.61  356.52   68.37  393.97   66.34  417.31   63.17
  486.64   61.94  506.77   63.12  521.23   62.19  540.94   63.38  578.01   62.15
  638.17   63.64  680.42   62.11  692.28   59.11  705.42   62.36  760.82   63.15
   826.2   62.03  860.38   63.11  918.63    62.4  997.46   66.79  1018.3   66.55
 1028.09    68.1 1226.73   70.08 1255.41   68.86 1269.53   70.04 1291.16   70.15
#Mann= 3 , 0 , 0
       0     .12       0  680.42     .06       0  705.42     .12       0
Bank Sta=680.42,705.42
Exp/Cntr=.3,.1

Type RM Length L Ch R = 1 ,15659   ,376,333.64,266.74
XS GIS Cut Line= 4
 2106572.8220112  229132.9073233     2106538.364      229153.221
     2105326.184      229867.825 2105268.6013316  230075.9898012
#Sta/Elev= 30
       0   78.49   33.96   79.91   150.1   80.48     221   84.93  259.62   85.26
  501.64   73.78  571.43   72.21  580.64   73.16   615.8   72.83  670.55   69.31
  720.65   67.88  760.48   68.91  781.41   66.64  805.76   66.76     820   65.14
  871.17   64.18  894.56   62.29  905.73    58.6  919.56    62.3 1021.86   61.69
 1194.86    63.2 1242.21   62.42  1268.5    63.3 1277.43   65.92 1317.92   68.85
 1482.88   69.07 1518.65   70.23 1577.21   69.15 1601.37   67.68 1663.12   70.15
#Mann= 3 , 0 , 0
       0     .12       0  894.56     .06       0  919.56     .12       0
Bank Sta=894.56,919.56
Exp/Cntr=.3,.1

Type RM Length L Ch R = 1 ,15326   ,409,389.16,297.4
XS GIS Cut Line= 5
  2105977.593564  228698.2668879     2105273.251      229846.651
 2105256.0865348  230076.4543348     2105253.852      230106.371
 2105250.1277753  230156.2321086
#Sta/Elev= 30
       0   78.44  132.51   75.26  212.75   75.17  312.74    73.1  348.52      72
  392.42   68.26  434.99   68.35  444.16   66.51  484.43    64.2  585.67   64.11
  600.58   62.94  705.87   61.09  717.37   61.64  731.66    57.5  745.17    61.6
 1102.35   62.89 1187.62   61.97 1211.14   62.61 1253.16   67.73 1274.48   68.31
 1396.46   68.32 1422.21   69.26  1453.2   68.65 1495.34   70.22 1526.13   69.25
 1551.31   69.68 1563.32   67.71  1596.7   67.43 1634.35   69.89 1657.62   70.14
#Mann= 3 , 0 , 0
       0     .12       0  717.37     .06       0  745.17     .12       0
#XS Ineff= 2 , 0
       0     640      70               0
Bank Sta=717.37,745.17
Exp/Cntr=.3,.1

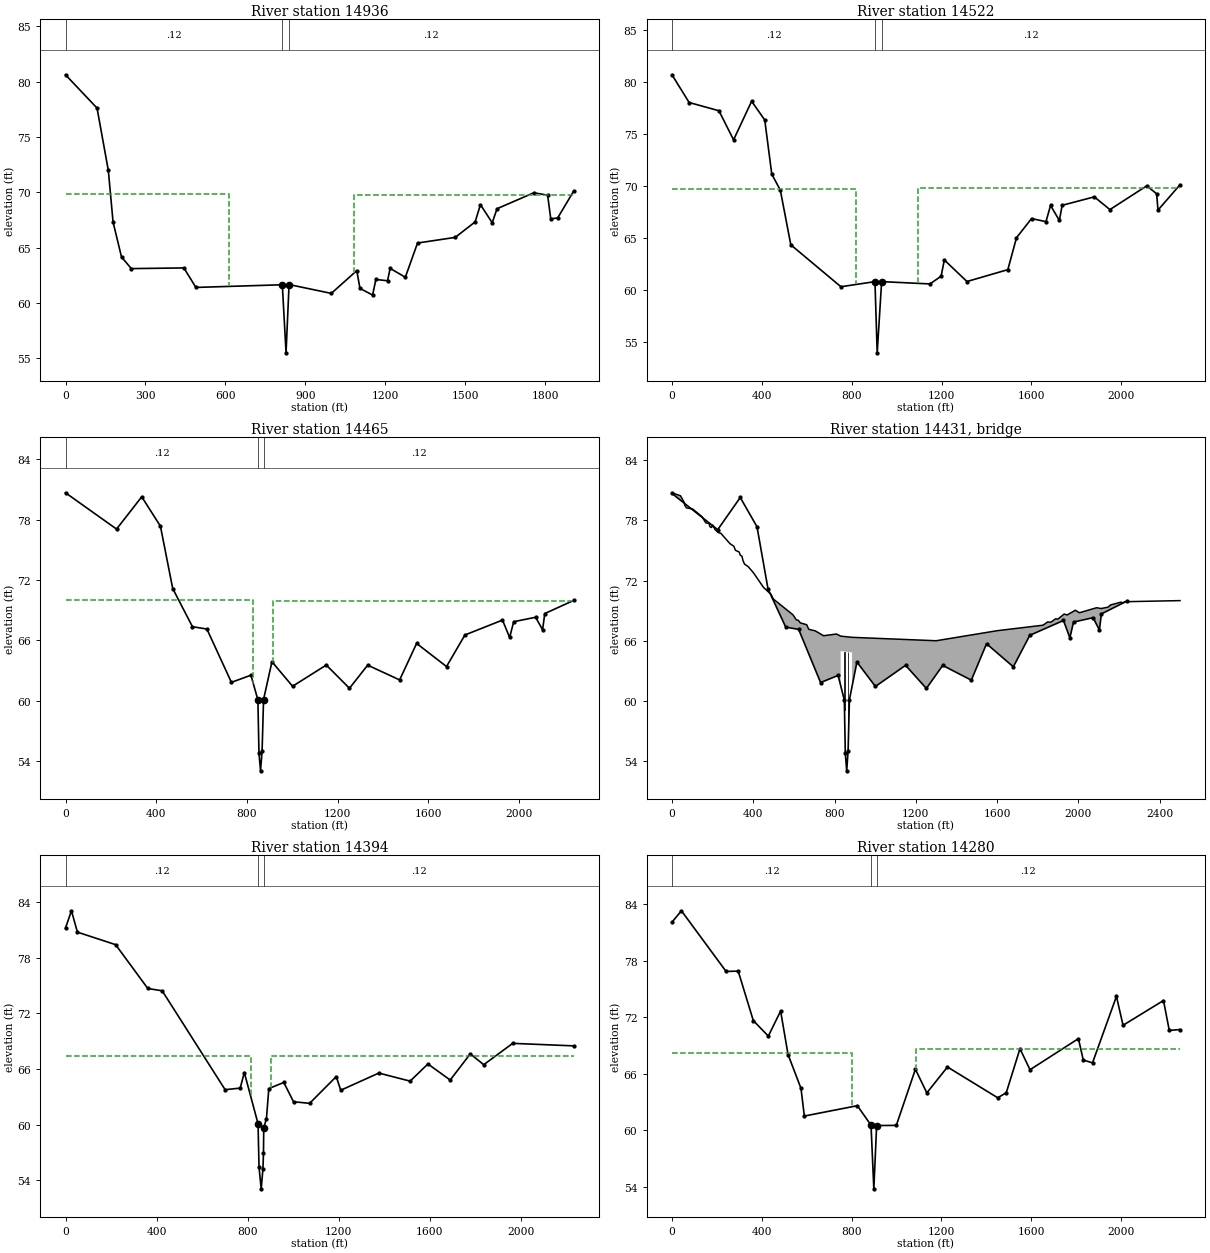
Type RM Length L Ch R = 1 ,14936   ,403,414.82,495.26
XS GIS Cut Line= 5
 2105525.3425374  228211.8018869     2105522.247      228226.479
     2105234.901      229588.895     2105264.626      229846.515
 2105252.6256484  230085.6948443
#Sta/Elev= 30
       0   80.62  118.32   77.61  160.66   71.98  178.46   67.31  210.12   64.16
  246.92   63.11  444.19   63.17  489.17   61.41  813.48   61.65  827.46    55.5
  838.78   61.67  997.28   60.87  1092.9   62.93 1104.82   61.32 1152.27   60.72
 1164.52   62.13 1208.28   62.01 1218.02   63.13 1275.04   62.33 1320.85   65.42
 1462.19   65.93 1537.01   67.33 1556.84   68.89  1601.1   67.25 1619.04   68.52
 1757.28   69.96 1808.97   69.74 1820.66   67.61 1846.47   67.68  1906.2   70.09
#Mann= 3 , 0 , 0
       0     .12       0  813.48     .06       0  838.78     .12       0
#XS Ineff= 2 , 0
       0  612.06   69.84 1083.05       0   69.78
Bank Sta=813.48,838.78
Exp/Cntr=.3,.1

Type RM Length L Ch R = 1 ,14522   ,56,56.19,57.13
XS GIS Cut Line= 6
 2104886.0243248  227890.5426802     2105027.108      228272.766
      2105052.66       228489.67     2105013.717      229256.634
     2105243.627      229852.965 2105249.2643002  230077.6222936
#Sta/Elev= 30
       0   80.67   76.45   78.01   209.1   77.22  274.23   74.43  354.58   78.13
  413.08   76.33   444.3   71.14  482.41    69.6  529.07   64.36  752.11   60.34
  903.67   60.83  913.61      54  933.41   60.83 1148.69   60.61 1198.12   61.35
 1212.48   62.91 1313.28   60.84 1495.26   61.98 1533.75   65.04 1600.78   66.88
 1665.07   66.58 1685.29   68.14 1724.62    66.7  1737.1   68.15 1880.04   68.96
 1949.65   67.74  2113.9   70.02 2157.84   69.25 2163.61   67.69 2261.72   70.12
#Mann= 3 , 0 , 0
       0     .12       0  903.67     .06       0  933.41     .12       0
#XS Ineff= 2 , 0
       0  819.02   69.73 1094.99       0   69.79
Bank Sta=903.67,933.41
Exp/Cntr=.5,.3

Type RM Length L Ch R = 1 ,14465   ,70,71.25,72.15
XS GIS Cut Line= 6
     2104839.451      227924.129     2104973.153      228287.764
      2104996.66       228489.67     2104936.916      229071.995
     2104960.749      229274.558     2105244.514      230083.025
#Sta/Elev= 30
       0   80.68  225.08   77.07  336.01   80.28  418.47   77.36  472.64   71.16
  559.72   67.36  623.37   67.13  731.37   61.83  817.47   62.54  848.14   60.09
  852.88   54.81  859.81   53.03  866.74   55.03  873.14   60.12  910.11   63.88
 1001.07   61.44 1149.67   63.55 1251.91   61.24 1332.18   63.54 1473.11   62.07
 1547.95    65.7 1679.77    63.4 1760.94   66.54 1926.54   68.02 1958.04   66.29
 1975.96   67.86 2072.53    68.3 2103.28   67.06 2113.03   68.67  2239.8   69.97
#Mann= 3 , 0 , 0
       0     .12       0  848.14     .06       0  873.14     .12       0
#XS Ineff= 2 , 0
       0  827.81      70  915.81       0   69.92
Bank Sta=848.14,873.14
Exp/Cntr=.5,.3

Type RM Length L Ch R = 3 ,14431   ,,,
BEGIN DESCRIPTION:
SR 1722 - 0.8 Mi. N. JCT SR 1700
END DESCRIPTION:
Bridge Culvert--1,0,-1,-1, 0
Deck Dist Width WeirC Skew NumUp NumDn MinLoCord MaxHiCord MaxSubmerge Is_Ogee
22.3,25.3,2.6,0, 60, 60,,,.95,0,0,0,,
       0   41.95   60.89   62.53   70.74  102.01  148.03  166.45  182.36   186.7
  194.68  200.24  212.16  228.64  239.89  285.28  304.48  312.23  330.92  335.62
  344.05  349.63  356.84  375.25  400.45  450.64  487.19  498.69  595.68  612.21
  621.65   631.6  662.82  673.28  705.66  745.72  809.91     830     830     886
     886    1300    1600 1826.25 1848.29 1864.95 1887.06 1899.14 1929.73 1944.26
 1985.02 2005.01 2089.39  2111.5  2145.9 2158.45 2210.41    2219  2227.2    2500
   80.75   80.45   79.76   79.53   79.25   79.13   78.36   77.75    77.7   77.37
   77.29   77.54   77.08   76.77   76.72   75.68   75.42   75.02   74.84   74.54
   74.43   73.99   73.64   73.38   72.79   71.31   70.63   70.16   68.58   68.08
   68.04   67.78    67.6   67.14   66.98    66.5   66.67   66.46   66.46   66.34
   66.34      66      67   67.55   67.87   67.85   68.18   68.16   68.66   68.57
   69.04   68.79   69.29   69.21   69.35   69.57   69.85   69.75   69.89      70
                                                                                
                                                                                
                                                                                
                                                                   64.96   64.84
                                                                                
                                                                                
       0   41.95   60.89   62.53   70.74  102.01  148.03  166.45  182.36   186.7
  194.68  200.24  212.16  228.64  239.89  285.28  304.48  312.23  330.92  335.62
  344.05  349.63  356.84  375.25  400.45  450.64  487.19  498.69  595.68  612.21
  621.65   631.6  662.82  673.28  705.66  745.72  809.91     830     830     886
     886    1300    1600 1826.25 1848.29 1864.95 1887.06 1899.14 1929.73 1944.26
 1985.02 2005.01 2089.39  2111.5  2145.9 2158.45 2210.41    2219  2227.2    2500
   80.75   80.45   79.76   79.53   79.25   79.13   78.36   77.75    77.7   77.37
   77.29   77.54   77.08   76.77   76.72   75.68   75.42   75.02   74.84   74.54
   74.43   73.99   73.64   73.38   72.79   71.31   70.63   70.16   68.58   68.08
   68.04   67.78    67.6   67.14   66.98    66.5   66.67   66.46   66.46   66.34
   66.34      66      67   67.55   67.87   67.85   68.18   68.16   68.66   68.57
   69.04   68.79   69.29   69.21   69.35   69.57   69.85   69.75   69.89      70
                                                                                
                                                                                
                                                                                
                                                                   64.96   64.84
                                                                                
                                                                                
Pier Skew, UpSta & Num, DnSta & Num=,849, 2 ,849, 2 , 0 , 0 , 0 ,,
       1       1
       0      66
       1       1
       0      66
Pier Skew, UpSta & Num, DnSta & Num=,867, 2 ,867, 2 , 0 , 0 , 0 ,,
       1       1
       0      66
       1       1
       0      66
BR Coef= 1 , 0 , 0 ,, 0 ,,,.8,-1,1.2,0,
WSPro=,,,, 1 ,,,, 0 ,,,, 0 ,,,,-1 ,-1 ,-1 , 0 , 0 , 0 , 0 , 0
BR U #Sta/Elev= 30
       0   80.68  225.08   77.07  336.01   80.28  418.47   77.36  472.64   71.16
  559.72   67.36  623.37   67.13  731.37   61.83  817.47   62.54  848.14   60.09
  852.88   54.81  859.81   53.03  866.74   55.03  873.14   60.12  910.11   63.88
 1001.07   61.44 1149.67   63.55 1251.91   61.24 1332.18   63.54 1473.11   62.07
 1547.95    65.7 1679.77    63.4 1760.94   66.54 1926.54   68.02 1958.04   66.29
 1975.96   67.86 2072.53    68.3 2103.28   67.06 2113.03   68.67  2239.8   69.97
BR U #Mann= 3
       0     .12  848.14    .055  873.14     .12
BR D #Sta/Elev= 30
       0    81.2   26.16   83.05   52.22   80.75  220.05    79.4  361.37   74.68
  424.59   74.43  700.81   63.78  767.09   63.95  785.13   65.63  845.42   60.11
  849.65   55.47  859.24    53.1  866.89   55.26  869.29   56.96  870.42    59.7
  882.15   60.62  892.72    63.9  958.48   64.56 1001.18   62.48 1071.87   62.31
 1188.79   65.19 1208.55   63.72  1375.7   65.57 1513.19    64.7 1591.29   66.55
 1689.09   64.82 1777.36   67.64 1836.34   66.47 1963.48   68.77 2230.72    68.5
BR D #Mann= 3
       0     .12  845.42    .055  870.42     .12
BC Design=,, 0 ,, 0 ,,,,,,

Type RM Length L Ch R = 1 ,14394   ,110,114.6,110.82
XS GIS Cut Line= 6
     2104772.049      227943.026     2104876.143      228205.189
     2104918.089      228390.553      2104866.98      229069.003
     2104895.051      229298.501     2105204.958      230084.125
#Sta/Elev= 30
       0    81.2   26.16   83.05   52.22   80.75  220.05    79.4  361.37   74.68
  424.59   74.43  700.81   63.78  767.09   63.95  785.13   65.63  845.42   60.11
  849.65   55.47  859.24    53.1  866.89   55.26  869.29   56.96  870.42    59.7
  882.15   60.62  892.72    63.9  958.48   64.56 1001.18   62.48 1071.87   62.31
 1188.79   65.19 1208.55   63.72  1375.7   65.57 1513.19    64.7 1591.29   66.55
 1689.09   64.82 1777.36   67.64 1836.34   66.47 1963.48   68.77 2230.72    68.5
#Mann= 3 , 0 , 0
       0     .12       0  845.42     .06       0  870.42     .12       0
#XS Ineff= 2 , 0
       0  813.42   67.37  901.59       0   67.44
Bank Sta=845.42,870.42
Exp/Cntr=.5,.3

Type RM Length L Ch R = 1 ,14280   ,414,404.74,394.14
XS GIS Cut Line= 6
 2104649.4369872  227925.2655203     2104764.602       228215.31
     2104806.548      228400.675     2104755.439      229079.125
     2104783.509      229308.623 2105089.1354165    230097.57236
#Sta/Elev= 30
       0   82.12   42.14   83.33  240.89   76.89     295   76.92  362.19   71.67
  429.11   70.02  483.81   72.68  516.99   68.06  574.58   64.47  589.53   61.53
  825.53   62.63  886.48   60.56     899    53.8  911.48   60.52   999.1   60.54
 1084.16    66.5 1135.02   63.99  1226.9   66.74 1450.78   63.47 1488.79   64.01
 1549.82   68.68 1594.51   66.45 1810.07   69.75 1831.73   67.48  1872.9   67.18
 1979.47   74.24 2008.84   71.17 2188.99    73.8 2214.77   70.62 2262.56   70.72
#Mann= 3 , 0 , 0
       0     .12       0  886.48     .06       0  911.48     .12       0
#XS Ineff= 2 , 0
       0  800.49   68.26 1086.46       0   68.65
Bank Sta=886.48,911.48
Exp/Cntr=.3,.1

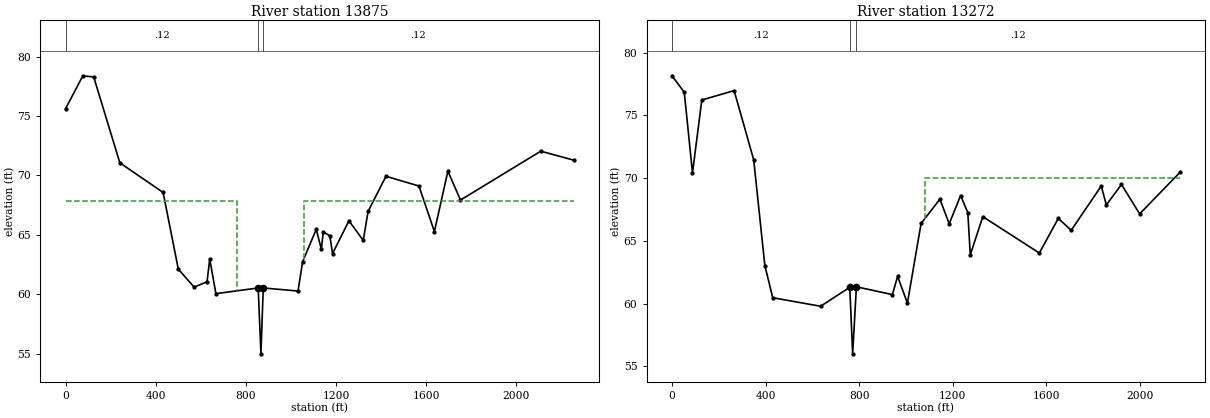
Type RM Length L Ch R = 1 ,13875   ,609,602.61,588.85
XS GIS Cut Line= 3
 2104392.3838378  227877.1836071     2104392.228      227897.183
 2104374.8158378  230131.7666071
#Sta/Elev= 30
       0    75.6   76.94   78.38  125.15   78.28   241.2   71.06  433.15   68.57
  500.64   62.12  570.72   60.61  628.21   61.06  639.98   62.97  667.43   60.06
   855.2   60.54  867.25      55  877.58   60.54 1031.94   60.28 1052.07   62.74
 1112.79   65.47 1135.39    63.8 1144.21   65.26 1173.17   64.92 1185.09   63.43
 1257.88   66.19 1321.31   64.54  1342.8   66.97 1422.17   69.93 1568.62   69.11
  1637.1   65.28 1696.97   70.36 1752.76   67.93  2109.2   72.04 2254.65   71.29
#Mann= 3 , 0 , 0
       0     .12       0   855.2     .06       0  877.58     .12       0
#XS Ineff= 2 , 0
          762.23   67.82 1058.02           67.86
Bank Sta=855.2,877.58
Exp/Cntr=.3,.1

Type RM Length L Ch R = 1 ,13272   ,548,586.22,543.35
XS GIS Cut Line= 4
  2103749.613056  228009.9758381 2103749.9232672  228014.9662057
     2103882.751      230151.766  2103884.302056  230176.7178381
#Sta/Elev= 30
       0   78.15   52.53   76.84   87.71   70.41  127.55   76.22  265.53   76.97
   349.2   71.46   396.9   63.03  430.59   60.47   635.2   59.79  759.76    61.3
  772.13      56  788.05   61.34   941.9   60.72  964.23   62.17    1006   60.04
 1064.58   66.39 1144.91   68.32 1184.67   66.36 1233.35   68.61 1264.12   67.25
 1274.76   63.89 1328.25   66.93 1569.78   64.03 1650.86   66.79 1706.02   65.84
 1834.45   69.37 1855.99   67.86 1920.76   69.49  1998.5   67.15 2170.93   70.46
#Mann= 3 , 0 , 0
       0     .12       0  759.76     .06       0  788.05     .12       0
#XS Ineff= 2 , 0
       0                    1080       0      70
Bank Sta=759.76,788.05
Exp/Cntr=.3,.1