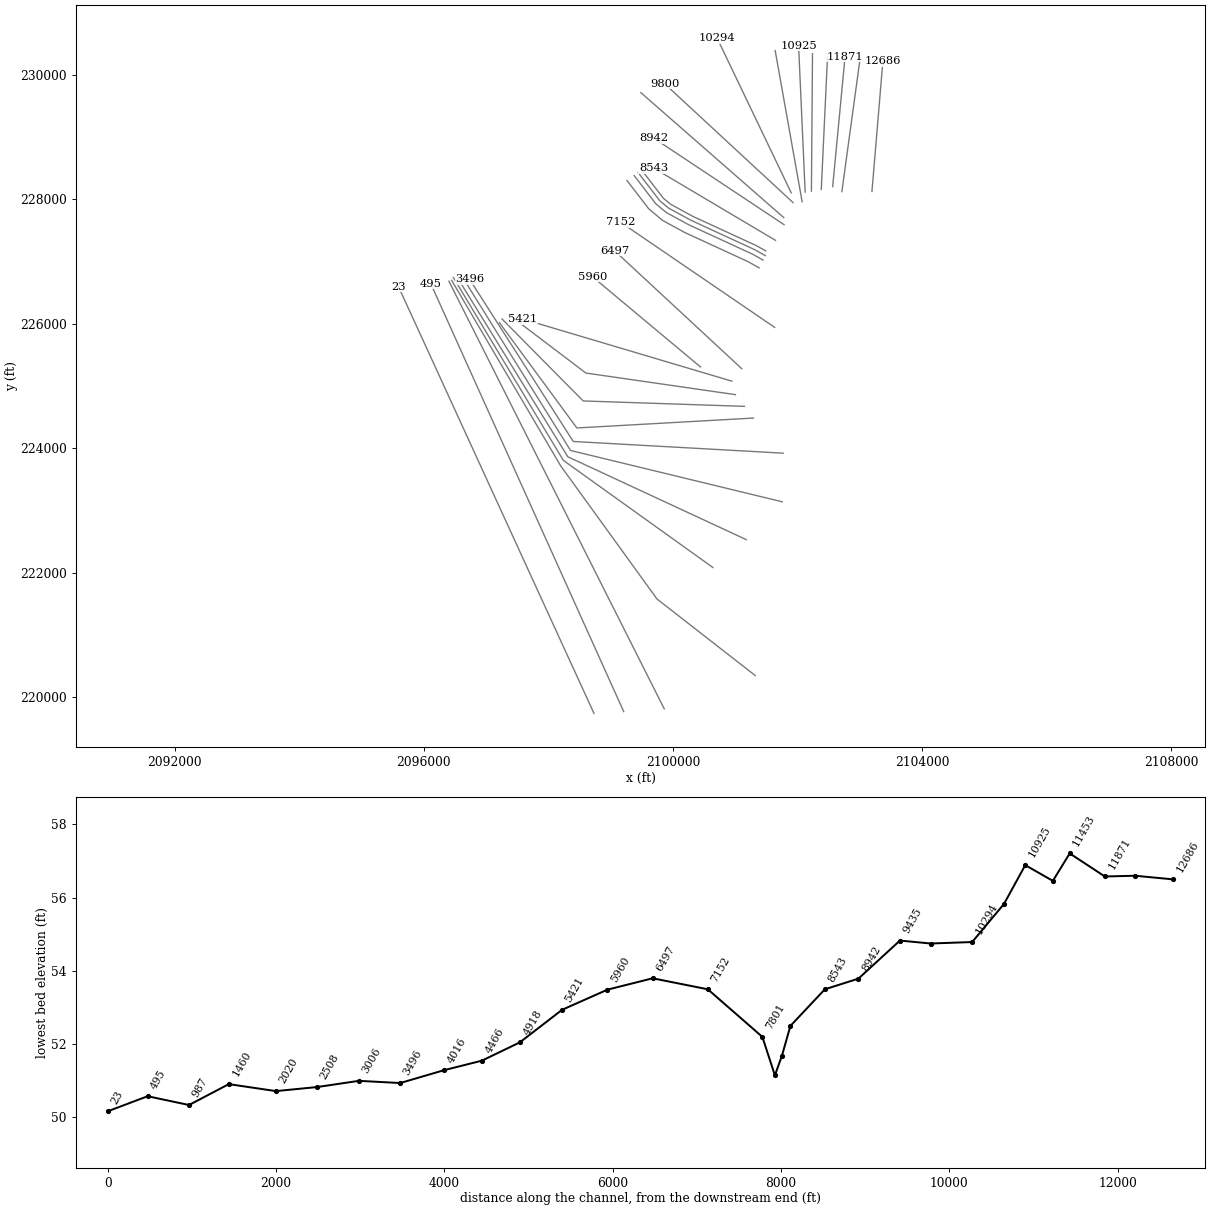
HEC-RAS study welch.prj: Welch Creek - Approximate Study

--- welch.g01 (geometry) --- (continued)

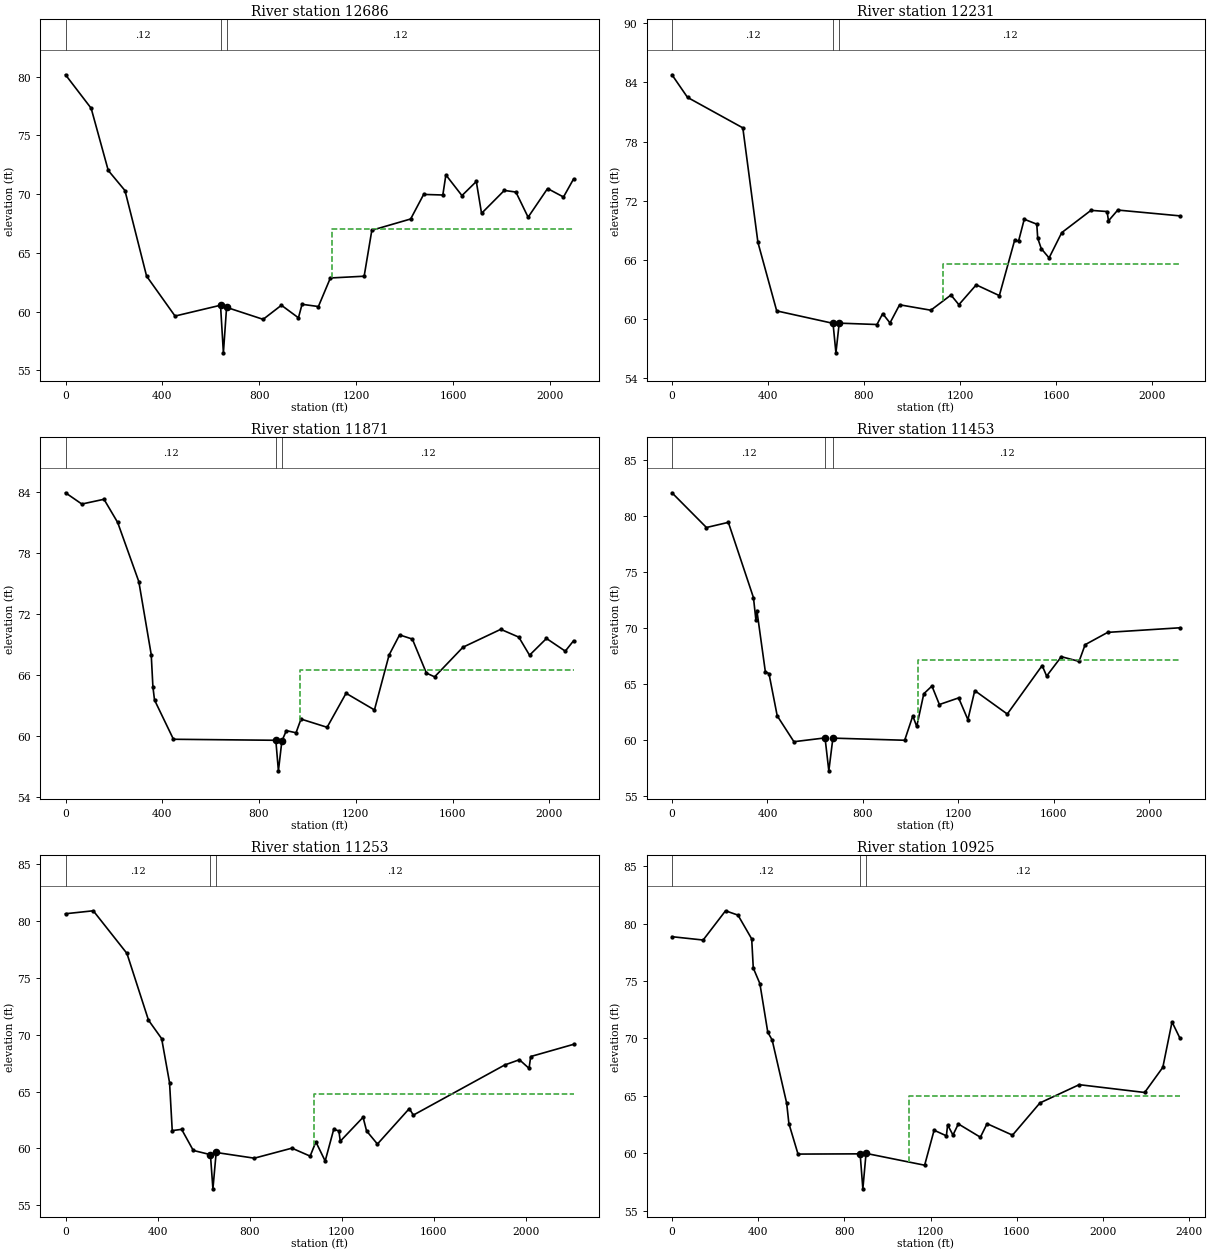
Type RM Length L Ch R = 1 ,12686   ,453,454.83,440.88
XS GIS Cut Line= 2
     2103197.592      228125.569     2103373.274      230216.182
#Sta/Elev= 30
       0   80.16  105.91   77.31  176.51   72.02  245.48   70.31  334.79   63.03
  452.35   59.63  640.16   60.55  652.01    56.5  665.16   60.37  816.11   59.35
  891.59   60.55  961.92   59.48   976.8   60.63 1044.31   60.44  1093.8   62.87
 1233.27   63.02 1264.98   66.93 1425.32   67.89 1479.01   69.98 1558.17   69.93
 1570.79   71.64 1637.14   69.88 1696.43   71.08 1718.06   68.37 1812.12   70.32
 1859.96   70.18 1910.35   68.04 1990.73   70.48 2056.44   69.76 2097.98   71.29
#Mann= 3 , 0 , 0
       0     .12       0  640.16     .06       0  665.16     .12       0
#XS Ineff= 2 , 0
       0                    1100       0      67
Bank Sta=640.16,665.16
Exp/Cntr=.3,.1

Type RM Length L Ch R = 1 ,12231   ,180,360.31,198.37
XS GIS Cut Line= 3
 2102714.6838645  228123.3217453     2102717.396      228143.137
 2103001.6298645  230219.7907453
#Sta/Elev= 30
       0   84.78   64.74   82.49   295.1    79.4  358.03   67.79  436.23   60.85
  670.78   59.59  682.88    56.6  696.56   59.61  853.73   59.47  877.65   60.57
  908.11   59.63     948   61.47 1078.15   60.92    1162   62.46 1194.93   61.48
 1267.21   63.49  1363.5    62.4 1427.91   68.07 1443.47   67.91 1467.24   70.14
 1519.43   69.64 1523.34   68.22 1538.12   67.16 1570.66   66.22 1623.35   68.78
 1745.13   71.04 1812.24   70.92 1818.11   69.98 1856.74   71.07 2116.02   70.48
#Mann= 3 , 0 , 0
       0     .12       0  670.78     .06       0  696.56     .12       0
#XS Ineff= 2 , 0
       0                    1130       0   65.58
Bank Sta=670.78,696.56
Exp/Cntr=.3,.1

Type RM Length L Ch R = 1 ,11871   ,205,417.8,230.82
XS GIS Cut Line= 3
 2102567.0341819  228204.0399095     2102764.244      230274.743
 2102766.1401819  230294.6529095
#Sta/Elev= 30
       0   83.97    67.5   82.86  159.08   83.33  215.54   81.05  303.05   75.22
  354.32   68.03  361.29   64.86  367.92   63.56  446.18   59.69  869.37   59.59
  880.08   56.58  894.37   59.51  912.78   60.54  952.93   60.33  973.47   61.68
 1081.37   60.87 1159.73   64.22 1277.03   62.58 1337.56   67.99 1380.87   69.97
 1433.71   69.56 1491.74   66.21 1525.82   65.84 1643.09   68.76 1799.23   70.52
 1873.78   69.75 1918.14   67.97 1988.13   69.62 2065.88   68.37 2100.07   69.39
#Mann= 3 , 0 , 0
       0     .12       0  869.37     .06       0  894.37     .12       0
#XS Ineff= 2 , 0
       0                     970       0   66.56
Bank Sta=869.37,894.37
Exp/Cntr=.3,.1

Type RM Length L Ch R = 1 ,11453   ,180,200.08,198.53
XS GIS Cut Line= 3
 2102384.0678069  228158.9830518 2102482.2173862  230254.7648963
 2102483.6208069  230284.7320518
#Sta/Elev= 30
       0   82.03  144.39   78.93  236.13   79.39  341.34   72.67  351.64   70.66
  355.64   71.52  391.11   66.06  406.29   65.89  440.84   62.12  510.77   59.81
  641.17   60.15  657.03   57.21  674.04   60.13  974.76   59.94 1008.73   62.11
 1025.25   61.17 1054.83   64.09 1088.94   64.78  1120.1   63.13 1200.73   63.72
 1239.53   61.78 1268.33   64.37 1404.57   62.28 1550.63   66.61 1569.37   65.67
 1630.91    67.4 1705.28   66.98 1730.59   68.47  1825.2   69.57 2128.08   69.98
#Mann= 3 , 0 , 0
       0     .12       0  641.17     .06       0  674.04     .12       0
#XS Ineff= 2 , 0
       0                    1030       0   67.11
Bank Sta=641.17,674.04
Exp/Cntr=.3,.1

Type RM Length L Ch R = 1 ,11253   ,132,327.91,152.85
XS GIS Cut Line= 2
     2102225.487      228131.425     2102243.055      230339.159
#Sta/Elev= 30
       0    80.6  120.65   80.86  266.91   77.12  360.62   71.26  417.83   69.64
  452.18   65.77  463.81   61.57  504.66   61.68  555.25   59.83  629.76   59.46
  640.62   56.46  654.76   59.65  820.47   59.15  983.91   60.03 1063.09   59.33
 1088.04   60.58 1128.44    58.9 1165.44   61.67 1187.86   61.55 1194.16   60.64
 1293.13   62.74 1308.39   61.54 1355.54   60.39    1494    63.5 1511.58   62.93
 1908.76   67.33 1972.53   67.79 2014.47   67.03 2021.59   68.07  2207.8   69.14
#Mann= 3 , 0 , 0
       0     .12       0  629.76     .06       0  654.76     .12       0
#XS Ineff= 2 , 0
       0                    1080       0   64.82
Bank Sta=629.76,654.76
Exp/Cntr=.3,.1

Type RM Length L Ch R = 1 ,10925   ,153,253.07,207.12
XS GIS Cut Line= 3
 2102125.0393746  228116.2689811     2102020.525      230450.425
 2102019.6303746  230470.4049811
#Sta/Elev= 30
       0   78.87  144.54   78.58  248.47   81.13  306.22   80.75  369.79   78.68
  377.12   76.14  407.76   74.78  444.41   70.54  464.66   69.87  531.99   64.36
  542.33   62.58  584.63   59.92  872.77   59.94  885.41   56.89  900.18   59.98
 1171.97   58.95 1215.87      62 1272.87   61.51 1278.52   62.47 1303.38   61.58
 1328.25   62.55 1430.52   61.39 1461.52   62.57 1579.49   61.57 1706.87   64.38
 1888.87   65.97 2192.51   65.29 2276.75   67.48 2319.44   71.44  2356.5   70.01
#Mann= 3 , 0 , 0
       0     .12       0  872.77     .06       0  900.18     .12       0
#XS Ineff= 2 , 0
       0                    1100       0      65
Bank Sta=872.77,900.18
Exp/Cntr=.3,.1

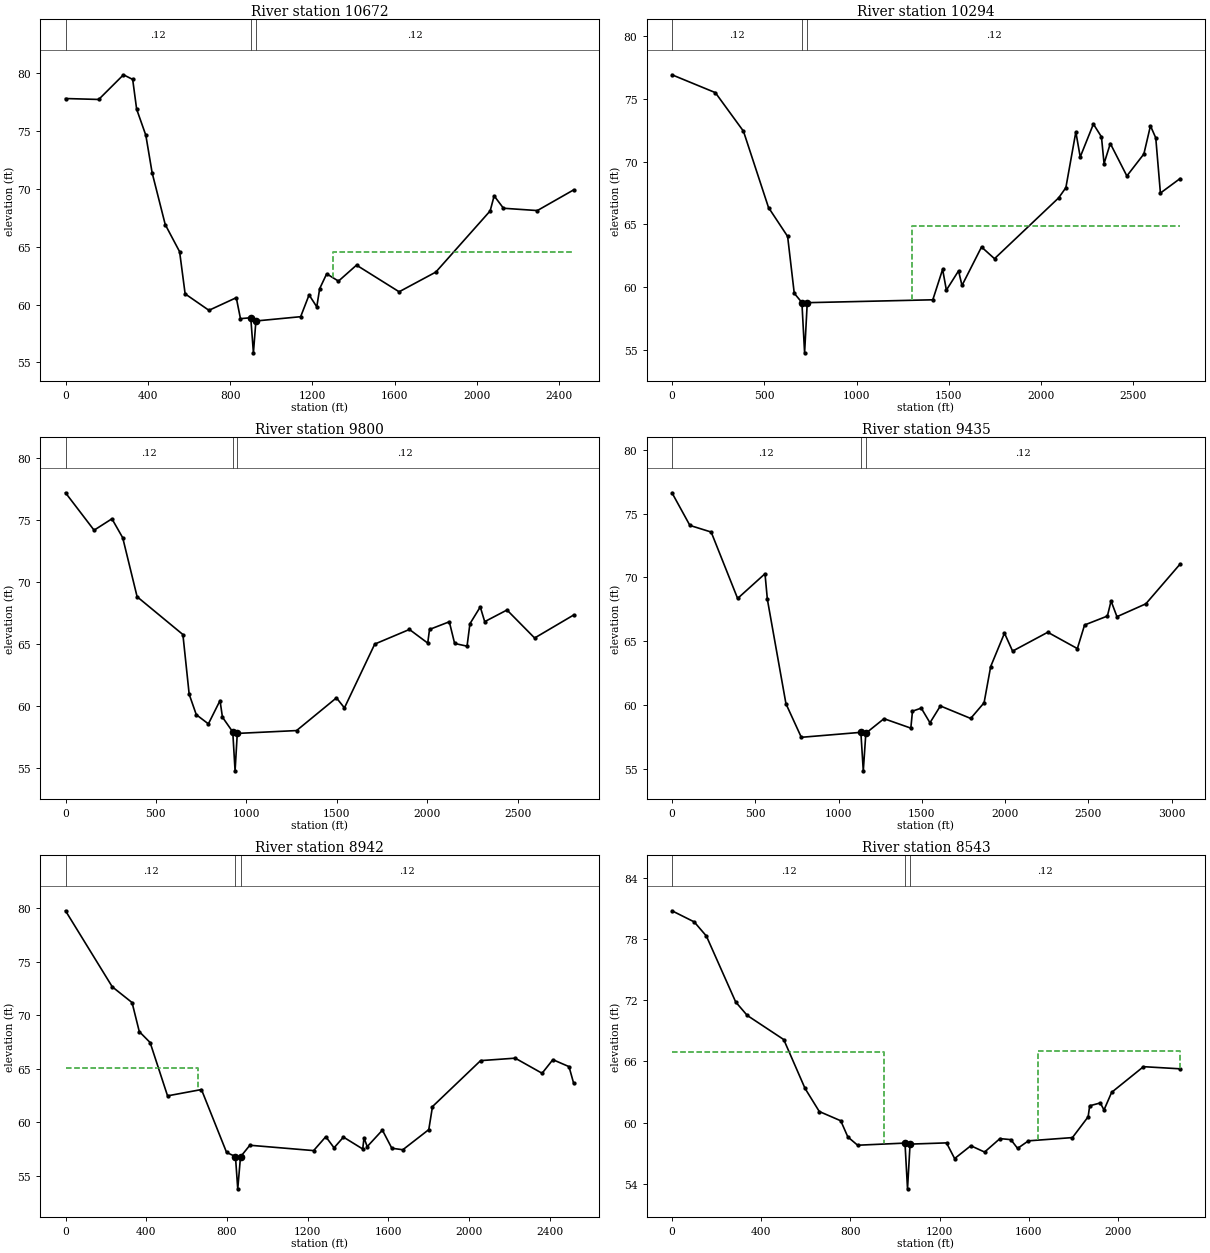
Type RM Length L Ch R = 1 ,10672   ,309,377.9,413.1
XS GIS Cut Line= 4
 2102076.7263053  227960.5844142 2102074.9708632  227970.4291297
     2102055.661      228078.721 2101643.3783053  230390.8484142
#Sta/Elev= 30
       0   77.78  161.41    77.7  281.68   79.83   326.4   79.43  345.67   76.86
  390.31   74.61  420.92   71.37  484.61    66.9  554.43   64.56  581.27   60.92
  696.93    59.5  829.77   60.59  850.12   58.78  900.15   58.86  913.09   55.83
  925.15   58.58 1142.59   58.95 1183.59   60.83 1220.94    59.8 1234.99   61.37
 1269.08   62.65 1326.36   62.02 1414.08    63.4 1621.09    61.1 1799.34    62.8
  2063.4   68.08 2082.81   69.38 2128.02   68.31 2292.66   68.11  2468.6   69.89
#Mann= 3 , 0 , 0
       0     .12       0  900.15     .06       0  925.15     .12       0
#XS Ineff= 2 , 0
       0                    1300       0   64.55
Bank Sta=900.15,925.15
Exp/Cntr=.3,.1

Type RM Length L Ch R = 1 ,10294   ,350,493.95,509.15
XS GIS Cut Line= 4
 2101901.2128172  228104.4994141     2100755.616      230497.273
 2100721.0694537  230569.4293313 2100712.4328172  230587.4684141
#Sta/Elev= 30
       0   76.91  235.01   75.49  387.37   72.42   523.1   66.35  626.69   64.05
  662.57   59.53  704.01   58.79  718.64   54.79  733.01   58.78 1413.39   59.01
 1466.54   61.43  1486.9   59.78 1552.83   61.31 1571.55   60.15 1677.29   63.21
 1747.72   62.28 2095.41   67.12 2134.36   67.93 2188.39   72.36 2212.14   70.37
 2283.52   72.99 2327.22   71.97 2341.31   69.85 2375.21   71.44 2464.93   68.86
 2557.07   70.61  2592.7   72.85 2621.47   71.89 2646.69    67.5 2752.88   68.65
#Mann= 3 , 0 , 0
       0     .12       0  704.01     .06       0  733.01     .12       0
#XS Ineff= 2 , 0
       0                    1300       0   64.89
Bank Sta=704.01,733.01
Exp/Cntr=.3,.1

Type RM Length L Ch R = 1 ,9800    ,330,364.83,327.77
XS GIS Cut Line= 3
 2101929.7896756  227948.0101786     2101915.116        227961.6
 2099868.4566756  229857.0851786
#Sta/Elev= 30
       0   77.19  158.05   74.17   256.7   75.09   316.4   73.56     396    68.8
   649.2   65.75  683.94   60.93  723.27   59.28  790.19   58.54   854.5   60.42
  867.96   59.08  924.99   57.89  937.74   54.75  949.99   57.77 1277.88      58
 1498.34   60.64 1542.53   59.83 1710.18   64.98 1901.99   66.16  2003.2   65.06
 2013.02   66.16 2122.51   66.78 2151.92   65.03 2220.61   64.81 2236.52   66.62
 2293.76   67.98 2318.23   66.79 2441.49   67.73 2594.33   65.47 2809.57   67.32
#Mann= 3 , 0 , 0
       0     .12       0  924.99     .06       0  949.99     .12       0
Bank Sta=924.99,949.99
Exp/Cntr=.3,.1

Type RM Length L Ch R = 1 ,9435    ,210,493.58,275.77
XS GIS Cut Line= 3
 2101781.2727028  227706.1201424     2099508.276      229694.993
 2099485.6987028  229714.7481424
#Sta/Elev= 30
       0   76.64  107.59   74.08  235.35   73.56  394.14   68.35  558.56   70.29
  572.76   68.28  684.39   60.09  776.62   57.46 1134.11   57.85 1148.64   54.83
 1164.02   57.78 1272.94   58.92 1434.12   58.18 1443.98   59.51 1496.66   59.75
 1549.03    58.6 1611.51   59.92 1793.45   58.94 1873.91   60.17 1913.52   63.01
 1996.41   65.63 2045.09   64.22 2256.26    65.7 2433.96   64.42 2477.27   66.27
 2614.24   66.97 2636.36   68.15 2671.75   66.92 2845.13   67.93 3050.29   71.04
#Mann= 3 , 0 , 0
       0     .12       0 1134.11     .06       0 1164.02     .12       0
Bank Sta=1134.11,1164.02
Exp/Cntr=.3,.1

Type RM Length L Ch R = 1 ,8942    ,353,398.45,362.14
XS GIS Cut Line= 3
 2101787.1920419  227592.0245334     2099705.974      228974.909
 2099689.3160419  228985.9775334
#Sta/Elev= 30
       0   79.75  231.87   72.65  330.01   71.18  365.78   68.47  419.45   67.45
  505.93   62.47     674   63.06  798.58   57.19  842.59    56.8  853.96   53.79
  867.59   56.78  913.95   57.86 1230.11   57.36 1290.55   58.66 1331.41   57.62
 1377.98   58.62 1473.58   57.51    1480   58.56 1495.73   57.73  1571.1   59.27
 1617.87   57.58 1672.49   57.44 1801.04   59.32 1819.42   61.47 2057.96   65.76
 2229.48   65.99 2362.78   64.58 2416.22   65.85 2496.25    65.2 2518.77   63.68
#Mann= 3 , 0 , 0
       0     .12       0  842.59     .06       0  867.59     .12       0
#XS Ineff= 2 , 0
           658.7   65.05
Bank Sta=842.59,867.59
Exp/Cntr=.3,.1

Type RM Length L Ch R = 1 ,8543    ,357,409.47,353.35
XS GIS Cut Line= 4
 2101648.1028161  227340.7629998     2099697.812      228498.936
 2099693.5129081  228501.4889999 2099689.2138161  228504.0419998
#Sta/Elev= 30
       0   80.79   99.67    79.7  154.33   78.31  285.75   71.84  337.46   70.52
  501.23   68.15  596.62   63.36  660.63   61.09  756.84   60.18  788.76   58.59
   832.6   57.78 1044.93   57.99 1056.31    53.5  1067.7   57.89 1231.17   58.01
 1267.53   56.47 1340.15   57.73 1401.89   57.11 1470.76   58.43  1519.6   58.33
 1549.95   57.47 1598.37   58.21 1795.83   58.53 1866.29   60.57  1873.2   61.65
 1920.72   61.93 1937.39   61.24 1971.64   62.97 2114.48   65.49 2278.26   65.28
#Mann= 3 , 0 , 0
       0     .12       0 1044.93     .06       0  1067.7     .12       0
#XS Ineff= 2 , 0
       0     950   66.93    1640       0   66.99
Bank Sta=1044.93,1067.7
Exp/Cntr=.3,.1

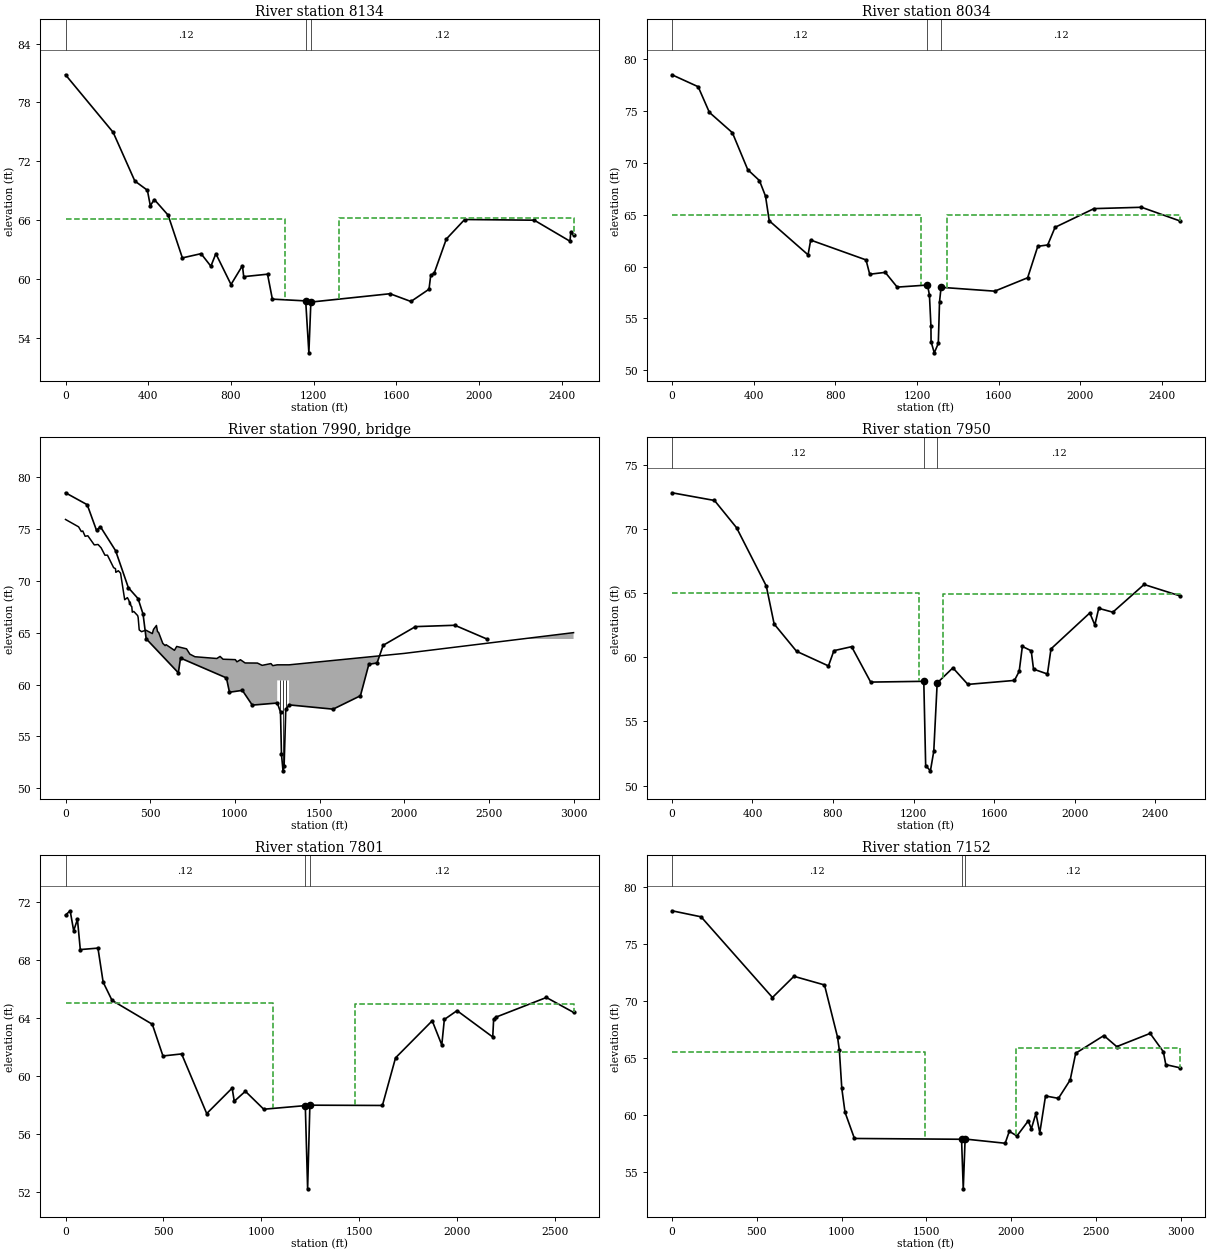
Type RM Length L Ch R = 1 ,8134    ,73,99.97,70.31
XS GIS Cut Line= 6
 2101490.6073427  227172.0885689     2101338.169      227256.969
     2100321.088      227725.922     2099963.791      227920.812
     2099847.688      228016.833 2099480.0843557  228495.2500106
#Sta/Elev= 30
       0   80.82  230.32   74.96   335.1      70  395.81   69.06  409.98   67.49
   429.4   68.11  496.21   66.52  564.95   62.17  655.32    62.6  702.75   61.32
  726.76    62.6  800.09   59.46  855.26   61.38  861.48   60.26  976.61   60.51
  999.95   57.97 1161.06   57.79 1176.46    52.5 1186.06   57.67 1568.75   58.52
 1669.82   57.73 1757.22   58.98 1765.54    60.4 1782.07    60.6 1840.84   64.09
 1929.61   66.08 2266.01   66.01 2438.53   63.87 2442.93    64.8 2455.91   64.48
#Mann= 3 , 0 , 0
       0     .12       0 1161.06     .06       0 1186.06     .12       0
#XS Ineff= 2 , 0
       0 1059.49   66.13 1322.53       0   66.23
Bank Sta=1161.06,1186.06
Exp/Cntr=.5,.3

Type RM Length L Ch R = 1 ,8034    ,83,84.32,80.64
XS GIS Cut Line= 6
     2101485.291      227094.995     2101306.643       227194.47
     2100289.562      227663.424     2099932.265      227858.313
     2099791.824      227974.652     2099442.647      228429.395
#Sta/Elev= 30
       0   78.47  128.24   77.32  183.13   74.85  295.84   72.89   371.1   69.33
  428.32   68.28  458.05   66.78  476.25   64.41  666.37   61.13  679.16   62.55
  950.16   60.64   968.2   59.26 1044.27   59.44 1102.81   58.02 1251.03   58.22
 1260.65   57.27 1268.01   54.26 1268.67   52.77 1284.37   51.69 1304.11    52.6
 1310.13   56.61 1317.67      58 1580.22   57.63 1741.58   58.92 1791.24   61.95
  1839.8   62.08 1875.81   63.78 2066.41   65.58 2299.07   65.71 2487.66   64.39
#Mann= 3 , 0 , 0
       0     .12       0 1251.03     .06       0 1317.67     .12       0
#XS Ineff= 2 , 0
       0  1220.2      65 1345.28       0   64.95
Bank Sta=1251.03,1317.67
Exp/Cntr=.5,.3

Type RM Length L Ch R = 3 ,7990    ,,,
BEGIN DESCRIPTION:
SR 1700 - 0.7 Mi. N. JCT SR 1722
END DESCRIPTION:
Bridge Culvert--1,0,-1,-1, 0
Deck Dist Width WeirC Skew NumUp NumDn MinLoCord MaxHiCord MaxSubmerge Is_Ogee
31.4,25.7,2.6,0, 60, 60,62,,.95,0,0,0,,
       0   77.28   93.31  101.93  115.85  131.78  169.93   192.2  210.26  232.82
  247.68  284.03  295.12  297.16     312  325.01   349.5   365.6  374.71  378.04
  382.25  386.27  391.38  394.37  403.19  426.12  428.93   435.3  449.09  474.28
  512.74   519.6  536.98  543.06  550.18  574.35  588.36  593.93  643.18  656.69
  714.59  734.29   764.1  893.52  912.82  930.23 1002.89 1012.04 1033.04 1060.62
 1133.34 1161.03 1213.34  1223.6    1250    1250    1320    1320    2000    3000
    75.9   75.19   74.74   74.79   74.28   74.33   73.45   73.49   73.17   72.46
   72.46   71.26   71.16   70.81   70.96   70.73   68.17   68.37   68.09    67.7
   67.95   67.58   67.51   66.97   67.04   66.64   66.46   65.26   65.09   65.24
   64.91   65.31   65.69   65.11   65.01   63.97   63.75   63.84    63.3   63.67
   63.44   62.93   62.68   62.51   62.71   62.44    62.4   62.19   62.39   62.08
   62.07   61.85   62.02   61.82    61.9    61.9    61.9    61.9      63      65
                                                                                
                                                                                
                                                                                
                                                                                
                                                                                
                                            60.4    60.4
       0   77.28   93.31  101.93  115.85  131.78  169.93   192.2  210.26  232.82
  247.68  284.03  295.12  297.16     312  325.01   349.5   365.6  374.71  378.04
  382.25  386.27  391.38  394.37  403.19  426.12  428.93   435.3  449.09  474.28
  512.74   519.6  536.98  543.06  550.18  574.35  588.36  593.93  643.18  656.69
  714.59  734.29   764.1  893.52  912.82  930.23 1002.89 1012.04 1033.04 1060.62
 1133.34 1161.03 1213.34  1223.6    1250    1250    1320    1320    2000    3000
    75.9   75.19   74.74   74.79   74.28   74.33   73.45   73.49   73.17   72.46
   72.46   71.26   71.16   70.81   70.96   70.73   68.17   68.37   68.09    67.7
   67.95   67.58   67.51   66.97   67.04   66.64   66.46   65.26   65.09   65.24
   64.91   65.31   65.69   65.11   65.01   63.97   63.75   63.84    63.3   63.67
   63.44   62.93   62.68   62.51   62.71   62.44    62.4   62.19   62.39   62.08
   62.07   61.85   62.02   61.82    61.9    61.9    61.9    61.9      63      65
                                                                                
                                                                                
                                                                                
                                                                                
                                                                                
                                            60.4    60.4
Pier Skew, UpSta & Num, DnSta & Num=,1268, 2 ,1268, 2 , 0 , 0 , 0 ,,
       1       1
       0      61
       1       1
       0      61
Pier Skew, UpSta & Num, DnSta & Num=,1285, 2 ,1285, 2 , 0 , 0 , 0 ,,
       1       1
       0      61
       1       1
       0      61
Pier Skew, UpSta & Num, DnSta & Num=,1302, 2 ,1302, 2 , 0 , 0 , 0 ,,
       1       1
       0      61
       1       1
       0      61
BR Coef= 1 , 0 , 0 ,, 0 ,,,.8,0,1.2,0,
WSPro=,,,, 1 ,,,, 0 ,,,, 0 ,,,,-1 ,-1 ,-1 , 0 , 0 , 0 , 0 , 0
BR U #Sta/Elev= 30
       0   78.47  128.24   77.32  183.13   74.85   206.2    75.2  295.84   72.89
   371.1   69.33  428.32   68.28  458.05   66.78  476.25   64.41  666.37   61.13
  679.16   62.55  950.16   60.64   968.2   59.26 1044.27   59.44 1102.81   58.02
 1251.03   58.22 1269.58   57.34 1275.16   53.33 1284.37   51.69 1290.77   52.12
 1300.66    57.6 1321.38   58.04 1580.22   57.63 1741.58   58.92 1791.24   61.95
  1839.8   62.08 1875.81   63.78 2066.41   65.58 2299.07   65.71 2487.66   64.39
BR U #Mann= 3
       0     .12 1251.03    .055 1321.38     .12
BR D #Sta/Elev= 30
       0   72.83  211.12   72.23  320.72   70.11  468.57   65.56  507.55    62.6
  618.96   60.47  777.39   59.33  804.43   60.52  892.43   60.83  960.57   58.27
 1251.43   57.99 1264.35   57.59 1276.87   51.84 1283.87   51.15 1290.72   51.72
 1298.38   57.43 1321.71   57.91 1395.51   59.18 1470.01   57.89 1701.44    58.2
  1724.9   58.91 1740.61   60.85 1865.14    58.7 1882.94   60.66 2075.65   63.46
 2100.69   62.52 2120.05   63.82 2190.05   63.52 2345.31   65.68 2523.81   64.79
BR D #Mann= 3
       0     .12 1251.43    .055 1321.71     .12
BR D Banks=1251.43,
BC Design=,, 0 ,, 0 ,,,,,,

Type RM Length L Ch R = 1 ,7950    ,149,148.91,141.99
XS GIS Cut Line= 6
     2101449.197      227023.601     2101270.548      227123.076
     2100253.468      227592.029      2099896.17      227786.919
     2099728.036      227926.372     2099378.858      228381.114
#Sta/Elev= 30
       0   72.83  211.12   72.23  320.72   70.11  468.57   65.56  507.55    62.6
  618.96   60.47  777.39   59.33  804.43   60.52  892.43   60.83  987.09   58.07
    1251   58.13 1260.26   51.56 1283.87   51.15 1300.58   52.68 1317.46      58
 1395.51   59.18 1470.01   57.89 1701.44    58.2  1724.9   58.91 1740.61   60.85
 1784.64   60.51 1796.04   59.08 1865.14    58.7 1882.94   60.66 2075.65   63.46
 2100.69   62.52 2120.05   63.82 2190.05   63.52 2345.31   65.68 2523.81   64.79
#Mann= 3 , 0 , 0
       0     .12       0    1251     .06       0 1317.46     .12       0
#XS Ineff= 2 , 0
       0  1225.7      65 1344.71       0   64.95
Bank Sta=1251,1317.46
Exp/Cntr=.5,.3

Type RM Length L Ch R = 1 ,7801    ,614,648.61,477.08
XS GIS Cut Line= 6
     2101386.028      226898.662     2101207.379      226998.137
     2100190.299       227467.09     2099833.001       227661.98
     2099611.371      227848.981     2099262.194      228303.724
#Sta/Elev= 30
       0   71.11   23.75   71.41   41.75   70.03   61.03   70.82   75.53   68.73
  165.79   68.83  192.29   66.48  237.76   65.22  443.47   63.57  497.88   61.38
  593.27   61.52  721.43    57.4  851.38   59.16  862.18   58.25   918.9   58.94
 1012.82    57.7 1225.13   57.95 1237.02    52.2 1248.49   57.98 1619.09   57.96
 1686.17   61.25 1873.55   63.81 1922.47   62.14 1935.44    63.9 2000.33   64.51
 2182.76   62.69 2187.46   63.93 2200.72   64.07 2456.85   65.42 2595.62   64.39
#Mann= 3 , 0 , 0
       0     .12       0 1225.13     .06       0 1248.49     .12       0
#XS Ineff= 2 , 0
       0    1060   65.05    1480       0   64.95
Bank Sta=1225.13,1248.49
Exp/Cntr=.3,.1

Type RM Length L Ch R = 1 ,7152    ,648,655.23,609.63
XS GIS Cut Line= 2
     2101636.123      225941.032     2099161.378      227630.998
#Sta/Elev= 30
       0    77.9  171.62   77.37   592.7   70.29  719.52   72.15  899.65   71.39
  976.84    66.8  987.25   65.67 1001.79   62.31  1020.7   60.22 1076.25   57.92
 1708.13   57.85 1718.21    53.5 1729.11   57.87 1965.48    57.5 1989.76   58.55
 2034.77   58.14 2101.41   59.46 2119.77   58.77 2146.82   60.12 2169.64   58.42
 2203.38   61.65 2279.54   61.44 2348.81   63.05 2381.46    65.4 2547.68   66.95
  2623.4   65.98  2820.5   67.14  2898.5   65.53 2912.87    64.4 2996.72   64.12
#Mann= 3 , 0 , 0
       0     .12       0 1708.13     .06       0 1729.11     .12       0
#XS Ineff= 2 , 0
         1493.24   65.54  2027.3           65.87
Bank Sta=1708.13,1729.11
Exp/Cntr=.3,.1

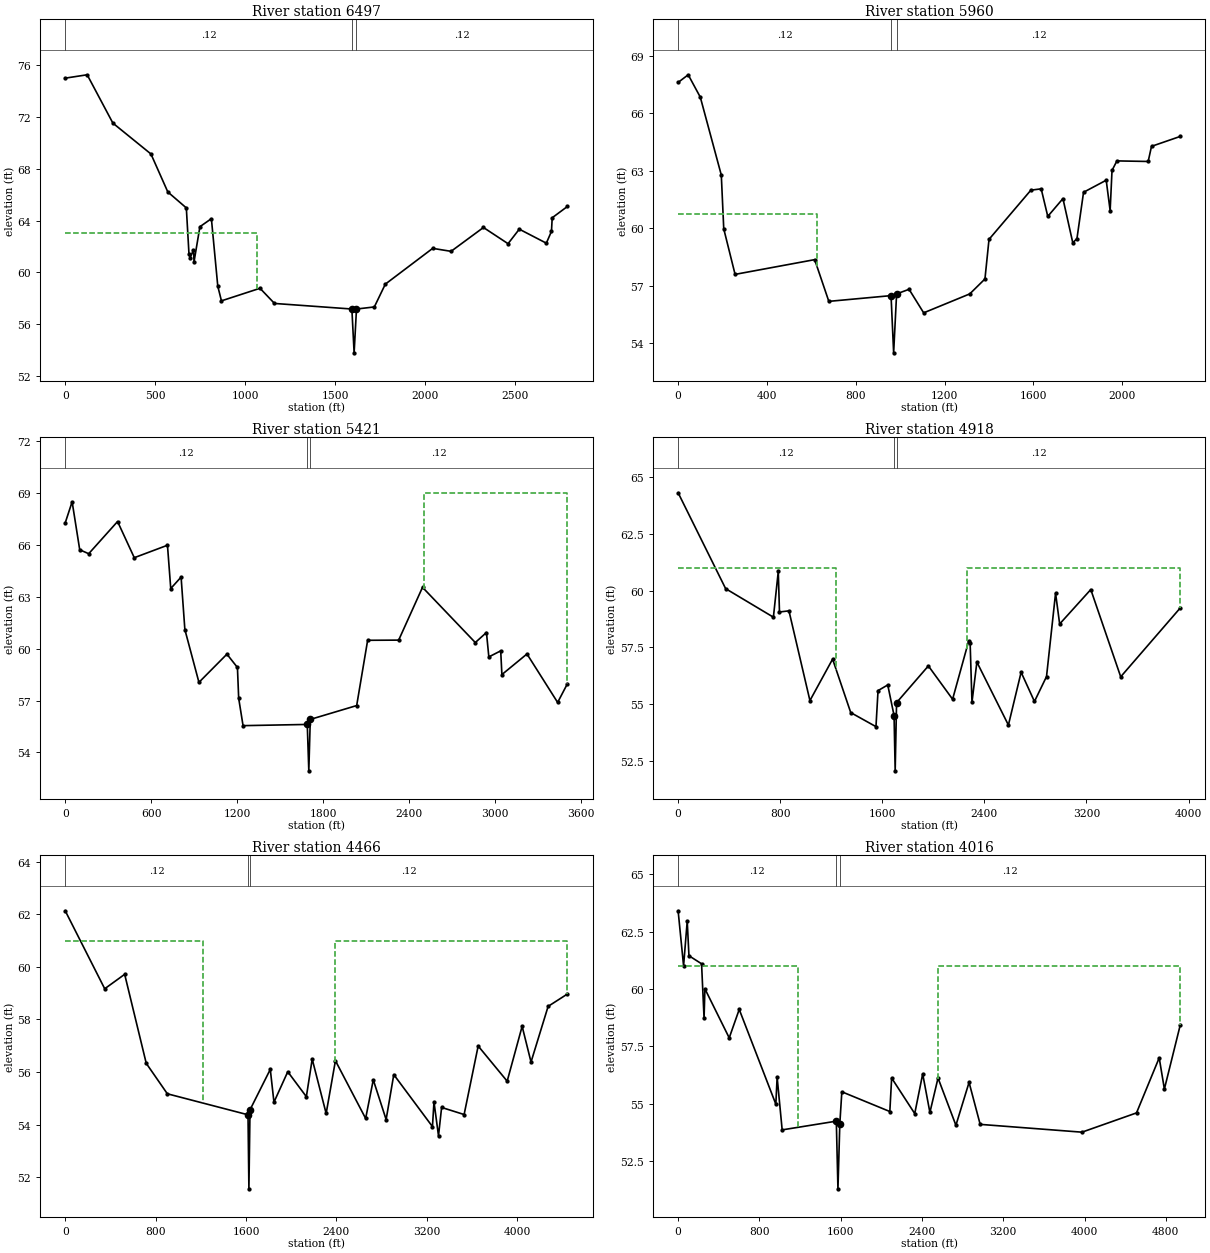
Type RM Length L Ch R = 1 ,6497    ,477,536.89,495.74
XS GIS Cut Line= 3
 2101106.4313714   225277.737973     2099075.676      227162.395
 2099061.0163714   227175.999973
#Sta/Elev= 30
       0   74.99  122.07   75.25  264.99   71.52  476.37   69.14  570.15   66.21
  673.02   64.98  687.68   61.44  693.65   61.12  712.65   61.74  715.91   60.83
  748.49   63.53  812.27   64.15  847.79   58.94  868.09   57.81 1082.37   58.78
  1162.9   57.61 1592.89   57.18 1605.38    53.8 1618.51   57.18 1717.69   57.34
 1778.82    59.1 2041.98   61.86 2144.06   61.63 2324.05   63.47 2460.68   62.22
 2523.17   63.34 2673.52   62.26 2701.99   63.17 2706.09   64.22 2790.54   65.09
#Mann= 3 , 0 , 0
       0     .12       0 1592.89     .06       0 1618.51     .12       0
#XS Ineff= 2 , 0
         1064.85   63.04
Bank Sta=1592.89,1618.51
Exp/Cntr=.3,.1

Type RM Length L Ch R = 1 ,5960    ,426.59,539.43,605.99
XS GIS Cut Line= 3
 2100444.3192721   225305.191676 2100382.9345465  225356.4938733
 2098709.1622721   226755.346676
#Sta/Elev= 30
       0   67.62   45.41   68.02   99.93   66.85  194.46   62.78  205.49   59.97
   256.5   57.59  614.94   58.36  678.66   56.18  958.82   56.48  970.51   53.49
  983.81   56.57 1039.95   56.81 1105.72   55.58 1313.31   56.57 1381.66   57.35
 1399.96   59.42 1588.43   61.99 1634.89   62.06 1664.56   60.62 1732.85   61.55
 1777.24   59.24 1795.96   59.46 1825.64   61.88 1927.73   62.51 1945.38   60.92
 1953.85   63.02 1975.88   63.52 2116.65   63.49 2131.65   64.28 2261.35    64.8
#Mann= 3 , 0 , 0
       0     .12       0  958.82     .06       0  983.81     .12       0
#XS Ineff= 2 , 0
          625.71   60.77
Bank Sta=958.82,983.81
Exp/Cntr=.3,.1

Type RM Length L Ch R = 1 ,5421    ,412.75,502.28,483.24
XS GIS Cut Line= 2
     2100947.111      225077.493     2097589.748      226076.019
#Sta/Elev= 30
       0   67.26   48.28   68.48  101.16   65.71  163.81   65.48  365.18   67.34
  481.72   65.25  713.19   65.97  736.09   63.47  808.26   64.13  834.56    61.1
  932.76   58.05 1127.97   59.68 1201.21   58.91 1209.93   57.13 1240.43   55.55
  1688.3   55.62 1699.06   52.94 1709.32   55.91 2032.89   56.71 2109.38   60.48
  2325.8   60.49 2492.07   63.54 2860.31   60.35 2938.07   60.93  2954.7   59.52
  3037.5   59.87 3045.81    58.5  3220.7   59.69 3434.59   56.89  3502.7   57.97
#Mann= 3 , 0 , 0
       0     .12       0  1688.3     .06       0 1709.32     .12       0
#XS Ineff= 2 , 0
       0                    2500       0      69
Bank Sta=1688.3,1709.32
Exp/Cntr=.3,.1

Type RM Length L Ch R = 1 ,4918    ,437.65,451.75,407.54
XS GIS Cut Line= 3
     2101004.997      224860.422     2098602.745      225207.736
      2097401.62      226119.433
#Sta/Elev= 30
       0   64.32  372.32   60.09  746.65   58.83  784.86   60.85  794.25   59.06
  868.49   59.11 1032.88   55.15 1210.53   56.98 1352.67   54.62  1550.4      54
 1566.59   55.59 1642.69   55.84 1692.12   54.49 1700.91   52.05  1711.8   55.06
 1961.02   56.68 2150.85   55.21 2276.01   57.76  2288.4   57.67 2302.67   55.08
 2341.16   56.85 2588.16   54.07 2687.77    56.4 2792.26   55.11 2886.84   56.21
  2957.7   59.89 2989.71   58.53 3233.67   60.05 3468.21    56.2 3935.17   59.24
#Mann= 3 , 0 , 0
       0     .12       0 1692.12     .06       0  1711.8     .12       0
#XS Ineff= 2 , 0
       0    1240      61    2260       0      61
Bank Sta=1692.12,1711.8
Exp/Cntr=.3,.1

Type RM Length L Ch R = 1 ,4466    ,434.63,450.06,399.79
XS GIS Cut Line= 3
     2101149.711      224672.294     2098559.331      224759.122
     2097256.906      226076.019
#Sta/Elev= 30
       0   62.14  349.56   59.17  526.18   59.72  717.08   56.33  903.72   55.17
 1617.62   54.37 1625.55   51.55 1635.39   54.56 1814.79    56.1 1847.21   54.85
  1969.4   56.01 2133.97   55.06 2185.66   56.49 2309.09   54.42 2391.24   56.43
 2658.53   54.23 2726.12    55.7 2839.85   54.19 2907.58    55.9 3249.75   53.92
 3263.34   54.86 3303.31   53.57 3330.87   54.65 3529.95   54.38 3654.35   56.99
 3910.97   55.65 4043.43   57.74  4122.1   56.38 4273.48    58.5    4444   58.97
#Mann= 3 , 0 , 0
       0     .12       0 1617.62     .06       0 1635.39     .12       0
#XS Ineff= 2 , 0
       0    1220      61    2390       0      61
Bank Sta=1617.62,1635.39
Exp/Cntr=.3,.1

Type RM Length L Ch R = 1 ,4016    ,440.73,520.27,378.3
XS GIS Cut Line= 3
     2101294.425      224484.166     2098458.031       224324.98
     2097213.491      226018.134
#Sta/Elev= 30
       0   63.41    53.7   61.01   89.61   62.96  106.61   61.45  230.76    61.1
  255.36   58.72  263.58   60.01  502.94   57.87  601.45   59.11   961.8   54.98
  974.42   56.16 1023.93   53.86  1556.8   54.24 1572.94   51.29 1591.39   54.13
 1611.25   55.52 2083.51   54.66  2101.4   56.12 2328.68   54.57 2406.95    56.3
 2477.83   54.62 2557.84   56.12 2733.87   54.06 2863.33   55.93 2972.65    54.1
 3974.34   53.76 4511.27    54.6 4734.55      57 4785.52   55.64 4942.21   58.44
#Mann= 3 , 0 , 0
       0     .12       0  1556.8     .06       0 1591.39     .12       0
#XS Ineff= 2 , 0
       0    1180      61    2560       0      61
Bank Sta=1556.8,1591.39
Exp/Cntr=.3,.1

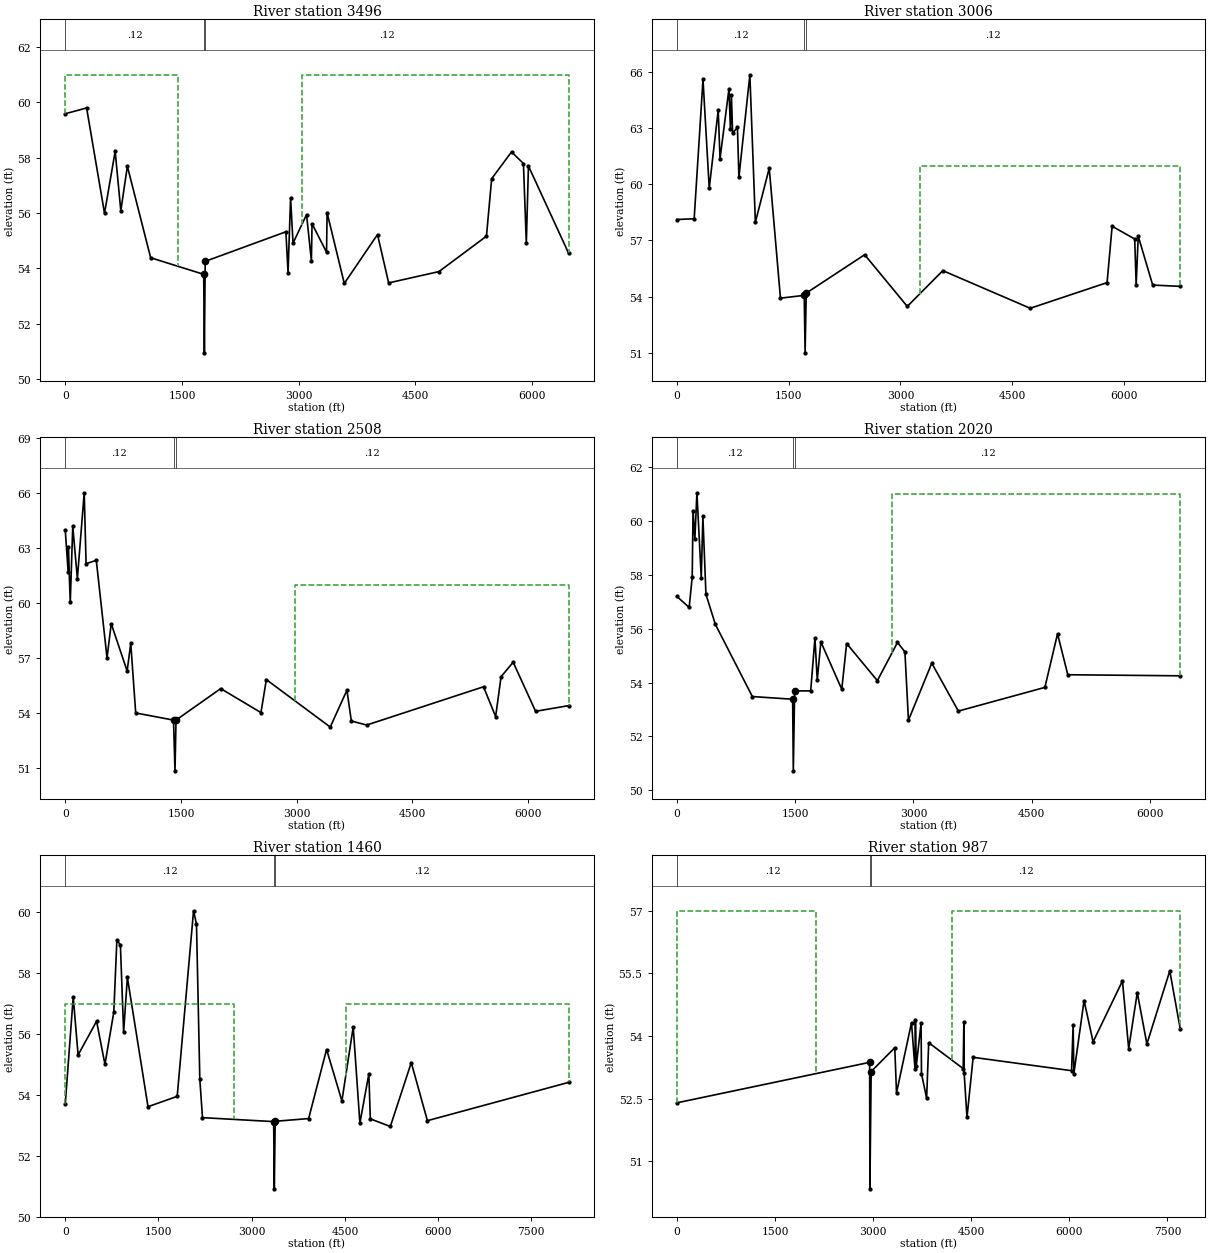
Type RM Length L Ch R = 1 ,3496    ,541.36,489.9,391.37
XS GIS Cut Line= 3
     2101771.981      223919.781     2098400.146       224107.91
     2096735.935      226712.761
#Sta/Elev= 30
       0   59.59  274.17    59.8  504.16   55.99  641.16   58.23  713.69   56.08
  797.83   57.69 1097.25   54.38 1778.75   53.78 1787.43   50.94 1798.15   54.25
 2834.94   55.32 2862.39   53.84 2895.12   56.54 2926.51   54.91 3100.56   55.94
 3162.37   54.27 3171.03   55.61 3357.17   54.58 3364.07   56.01  3585.1   53.45
 4012.14   55.22 4155.24   53.47  4801.7   53.88 5411.96   55.16 5478.84   57.24
 5734.04   58.21 5886.97   57.79 5924.29   54.91 5951.44    57.7 6468.17   54.54
#Mann= 3 , 0 , 0
       0     .12       0 1778.75     .06       0 1798.15     .12       0
#XS Ineff= 2 , 0
       0    1450      61    3040       0      61
Bank Sta=1778.75,1798.15
Exp/Cntr=.3,.1

Type RM Length L Ch R = 1 ,3006    ,549.52,498.23,374.95
XS GIS Cut Line= 3
     2101757.509      223138.326     2098356.732      223963.196
     2096634.636      226727.232
#Sta/Elev= 30
       0   58.12  232.11   58.16  350.73    65.6  434.51   59.79  554.68   63.96
  579.38   61.37  699.33    65.1  718.65   62.94  732.08   64.76  748.18   62.73
  812.79   63.04  832.87   60.38  979.78   65.85 1053.77   57.98 1239.79   60.86
 1390.31   53.92 1709.27   54.07 1721.02      51 1736.29   54.19 2520.38   56.24
 3092.64   53.48 3569.32   55.39 4742.52   53.38 5773.96   54.75 5841.86   57.76
 6144.73   57.08 6164.18   54.63 6192.24   57.23 6386.14   54.62    6756   54.55
#Mann= 3 , 0 , 0
       0     .12       0 1709.27     .06       0 1736.29     .12       0
#XS Ineff= 2 , 0
       0                    3260       0      61
Bank Sta=1709.27,1736.29
Exp/Cntr=.3,.1

Type RM Length L Ch R = 1 ,2508    ,538.56,488.45,351.14
XS GIS Cut Line= 3
     2101178.654      222530.528     2098313.317      223861.896
     2096547.807      226727.232
#Sta/Elev= 30
       0   63.96   37.82   61.66   39.24   63.05   64.79   60.04   96.92   64.17
     157   61.33   245.5   66.01  269.68   62.14  402.19   62.32  541.19      57
  595.83   58.86  801.83   56.28  848.91   57.79  912.91   53.99  1402.9    53.6
 1422.28   50.83 1435.53    53.6 2015.03   55.32 2536.52   54.01 2606.43   55.81
 3434.77   53.22 3650.89   55.23 3708.23   53.55 3907.37   53.33 5421.62   55.42
 5578.77   53.79 5648.94   55.97 5805.82   56.76  6096.4   54.08 6525.13   54.39
#Mann= 3 , 0 , 0
       0     .12       0  1402.9     .06       0 1435.53     .12       0
#XS Ineff= 2 , 0
       0                    2980       0      61
Bank Sta=1402.9,1435.53
Exp/Cntr=.3,.1

Type RM Length L Ch R = 1 ,2020    ,763.2,559.64,468.42
XS GIS Cut Line= 3
     2100643.212      222081.914      2098240.96       223804.01
      2096475.45      226741.703
#Sta/Elev= 30
       0    57.2  155.92   56.79  194.45   57.91  205.24   60.39  228.04   59.32
  254.26   61.05  309.25    57.9  329.98   60.17  368.67   57.28   488.2   56.16
  957.31   53.48 1468.12   53.38 1476.51   50.72 1493.66   53.69 1697.09   53.69
 1750.77   55.65 1780.15   54.09 1825.86   55.51 2091.08   53.75 2152.67   55.45
 2542.31   54.07 2797.74   55.49  2891.7   55.14 2936.67    52.6 3232.24   54.72
 3569.39   52.94 4666.68   53.82 4827.01   55.81 4957.29   54.29 6383.14   54.25
#Mann= 3 , 0 , 0
       0     .12       0 1468.12     .06       0 1493.66     .12       0
#XS Ineff= 2 , 0
       0                    2730       0      61
Bank Sta=1468.12,1493.66
Exp/Cntr=.3,.1

Type RM Length L Ch R = 1 ,1460    ,544.34,473.03,417.91
XS GIS Cut Line= 4
     2101323.367      220345.347     2099745.985      221575.415
     2098197.546      223717.182     2096446.507      226698.289
#Sta/Elev= 30
       0    53.7  127.85   57.22  206.51   55.31  503.74   56.42  638.58      55
  781.08   56.72  830.54    59.1  887.18   58.92  939.04   56.07  999.63   57.86
  1331.4   53.61 1801.16   53.95 2064.27   60.05 2111.67   59.61 2165.12   54.51
 2208.19   53.25 3353.61   53.12 3363.63   50.91 3377.92   53.13 3916.29   53.22
 4204.96   55.49 4451.55    53.8 4633.51   56.23 4741.01   53.07 4885.44   54.69
  4908.7   53.21 5231.12   52.96  5567.8   55.06 5827.33   53.15 8100.52   54.41
#Mann= 3 , 0 , 0
       0     .12       0 3353.61     .06       0 3377.92     .12       0
#XS Ineff= 2 , 0
       0    2710      57    4510       0      57
Bank Sta=3353.61,3377.92
Exp/Cntr=.3,.1

Type RM Length L Ch R = 1 ,987     ,500,491.91,469.33
XS GIS Cut Line= 2
     2099861.757      219809.905     2096403.093      226683.818
#Sta/Elev= 30
       0    52.4 2947.19   53.37 2950.98   50.34 2970.27   53.15 3331.02   53.72
 3357.64   52.64 3586.92   54.32 3639.93   53.22 3646.58   54.38 3659.47   53.28
 3733.41   54.31 3739.31    53.1 3818.15   52.51 3849.69   53.84 4377.03   53.22
 4387.02   54.33 4391.38   53.12 4434.87   52.05 4529.19   53.49 6033.61   53.17
 6057.69   54.27 6068.87    53.1 6224.79   54.85 6362.64   53.86 6811.66   55.32
 6906.95    53.7 7038.16   55.04 7185.07   53.81 7535.04   55.56    7695   54.17
#Mann= 3 , 0 , 0
       0     .12       0 2947.19     .06       0 2970.27     .12       0
#XS Ineff= 2 , 0
       0    2130      57    4200       0      57
Bank Sta=2947.19,2970.27
Exp/Cntr=.3,.1

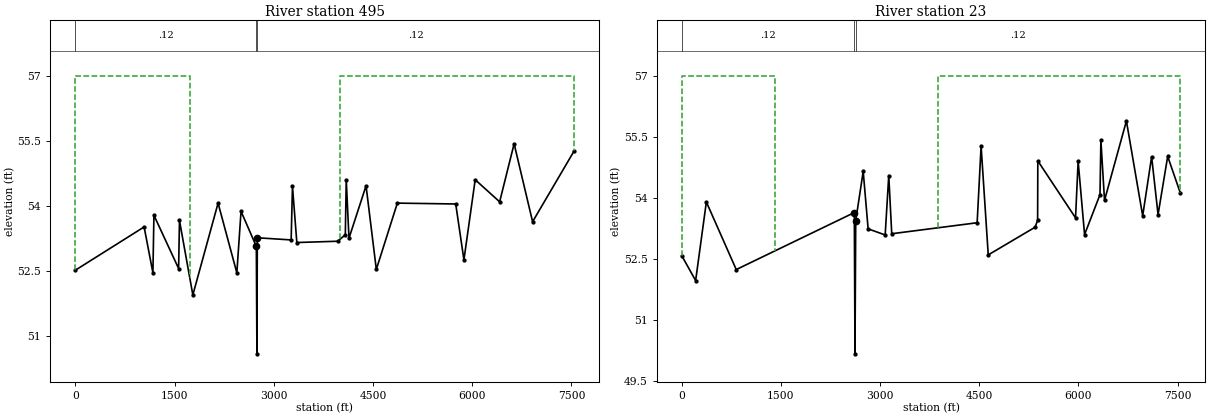
Type RM Length L Ch R = 1 ,495     ,461.5,472.35,465.55
XS GIS Cut Line= 2
     2099210.544      219766.491     2096113.665      226640.404
#Sta/Elev= 30
       0   52.51 1040.48   53.51 1173.46   52.45 1188.69   53.78 1562.04   52.55
 1574.88   53.66 1777.04   51.94 2158.61   54.06 2442.27   52.45 2505.58   53.87
 2736.77   53.06 2745.77   50.58 2751.85   53.26 3263.24   53.21  3283.1   54.45
 3349.04   53.15 3967.81   53.18 4082.13   53.33 4095.97    54.6 4137.54   53.25
 4395.57   54.46 4550.75   52.53 4868.63   54.06 5750.89   54.04 5875.12   52.75
 6045.43    54.6 6415.04   54.09 6633.84   55.43 6913.14   53.63 7539.32   55.26
#Mann= 3 , 0 , 0
       0     .12       0 2736.77     .06       0 2751.85     .12       0
#XS Ineff= 2 , 0
       0    1730      57    4000       0      57
Bank Sta=2736.77,2751.85
Exp/Cntr=.3,.1

Type RM Length L Ch R = 1 ,23      ,256.2,22.65,492.11
XS GIS Cut Line= 2
     2098732.988      219737.548     2095592.695      226596.989
#Sta/Elev= 30
       0   52.58  210.09   51.97   372.1    53.9  824.18   52.24 2610.26   53.64
 2620.54   50.17 2631.55   53.44  2744.7   54.65 2819.19   53.24 3077.05   53.09
 3131.31   54.55  3176.4   53.12 4468.22   53.39 4528.14   55.27 4636.24    52.6
 5344.41   53.28 5383.09   53.45 5386.12   54.91 5956.66   53.51 5995.88    54.9
 6093.33    53.1  6326.6   54.08 6339.96   55.42 6395.04   53.94 6726.12   55.89
 6972.41   53.56 7107.56   55.01 7205.04   53.59 7350.63   55.02  7544.1   54.11
#Mann= 3 , 0 , 0
       0     .12       0 2610.26     .06       0 2631.55     .12       0
#XS Ineff= 2 , 0
       0    1410      57    3870       0      57
Bank Sta=2610.26,2631.55
Exp/Cntr=.3,.1

Chan Stop Cuts=-1