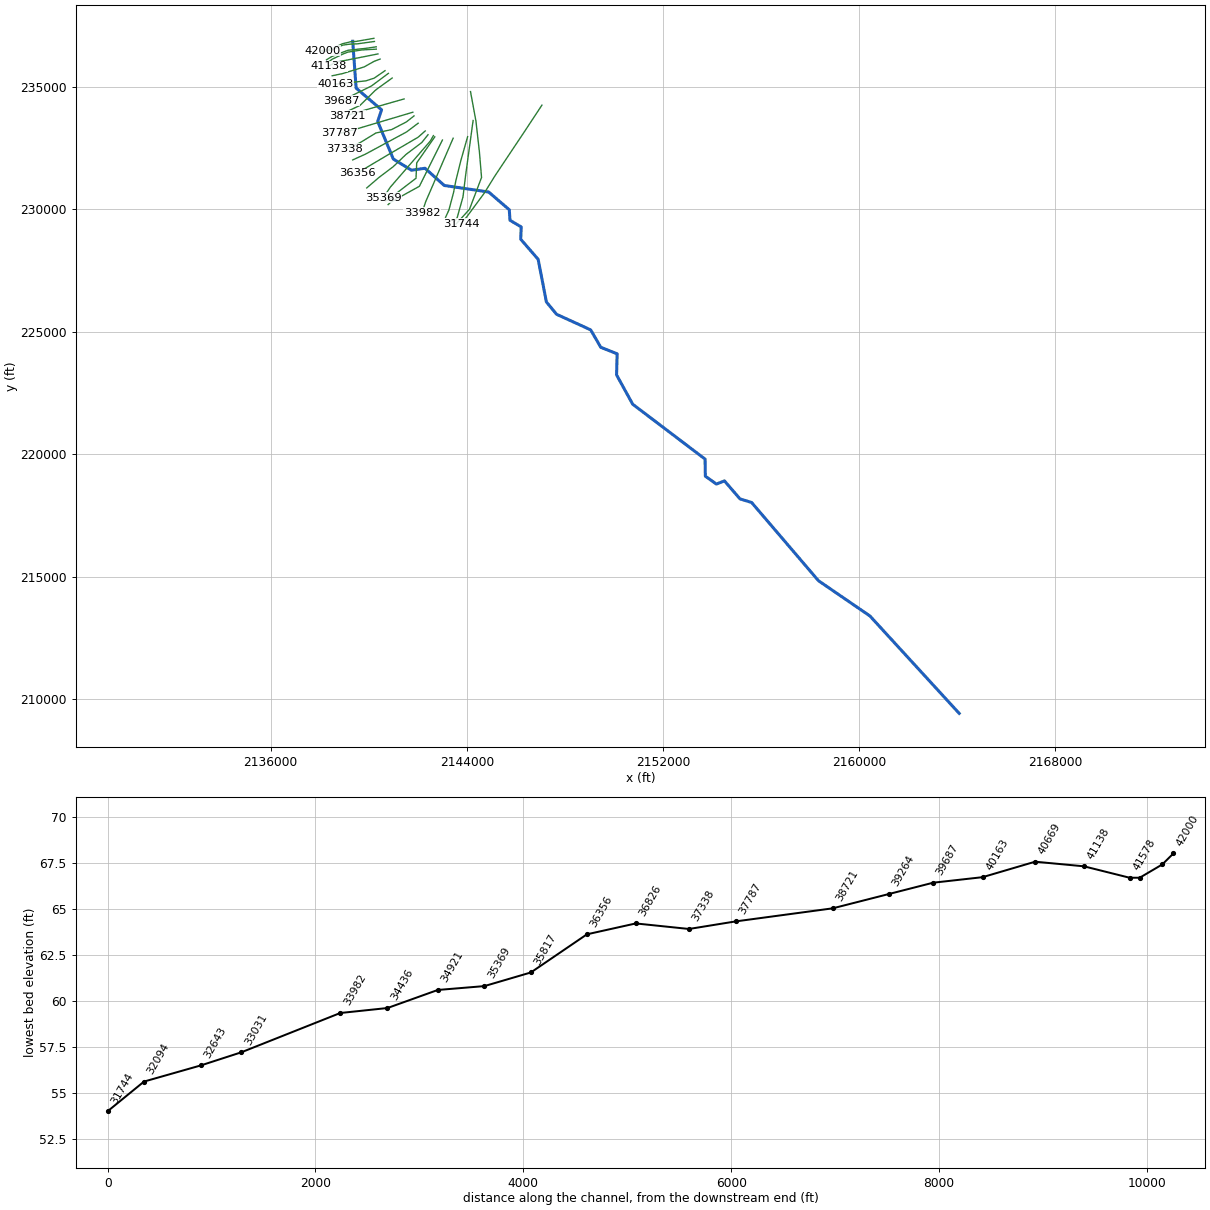
--- slapswamp.prj (project) ---

Proj Title=Slap Swamp
Current Plan=p01
Default Exp/Contr=.3,.1
English Units
Geom File=g01
Flow File=f01
Plan File=p01
Y Axis Title=Elevation
X Axis Title(PF)=Main Channel Distance
X Axis Title(XS)=Station
BEGIN DESCRIPTION:
Approximate Study for Slap Swamp
END DESCRIPTION:
DSS Export Rating Curves= 0
DSS Export Rating Curve Sorted= 0
DSS Export Volume Flow Curves= 0
DXF OffsetX= 0
DXF OffsetY= 0
DXF ScaleX= 1
DXF ScaleY= 10

--- slapswamp.p01 (plan) ---

Plan Title=100 Yr.  Flood Event
Version=Version 3.0.1  Mar 2001
Short Identifier=Slap Swamp
Geom File=g01
Flow File=f01
Subcritical Flow
K Sum by GR= 0
Std Step Tol= 0.003
Critical Tol= 0.003
Num of Std Step Trials= 20
Max Error Tol= 0.1
Flow Tol Ratio= 0.001
Split Flow NTrial= 30
Split Flow Tol= 0.02
Split Flow Ratio= 0.02
Log Output Level= 0
Friction Slope Method= 1
Unsteady Friction Slope Method= 2
Parabolic Critical Depth
Global Vel Dist= 0 , 0 , 0
Global Log Level= 0
CheckData=True
Encroach Param=-1 ,0,0, 2
Encroach River=Slap Swamp
Encroach Reach=Slap Swamp
Encroach Node=42000
       4      .7
Encroach Node=41892
       4      .7
Encroach Node=41675
       1  941.53 1016.53
Encroach Node=41634
       1  941.53 1016.53
Encroach Node=41578
       1     942    1016
Encroach Node=41138
       1     921    1139
Encroach Node=40669
       4      .7
Encroach Node=40163
       4      .7
Encroach Node=39687
       4      .7
Encroach Node=39264
       4      .7
Encroach Node=38721
       4      .7
Encroach Node=37787
       4      .7
Encroach Node=37338
       4      .7
Encroach Node=36826
       4      .7
Encroach Node=36356
       4      .7
Encroach Node=35817
       4      .7
Encroach Node=35369
       4      .7
Encroach Node=34921
       4      .7
Encroach Node=34436
       4      .7
Encroach Node=33982
       4      .7
Encroach Node=33031
       4      .7
Encroach Node=32643
       4      .7
Encroach Node=32094
       4      .7
Encroach Node=31744
       4      .7
Encroach Node=31540
       1 2039.54 2114.54
Encroach Node=31498
       1 2039.54 2114.54
Encroach Node=31471
       1 2039.54 2114.54
Encroach Node=30977
       1    1580    1925
Encroach Node=30439
       4      .7
Encroach Node=29953
       4      .7
Encroach Node=29388
       4      .7
Encroach Node=28211
       1    2200    3150
Encroach Node=26973
       1    2750    3660
Encroach Node=25622
       4      .7
Encroach Node=24278
       1    3699    4469
Encroach Node=23130
       4      .7
Encroach Node=22679
       4      .7
Encroach Node=22184
       4      .7
Encroach Node=21673
       4      .7
Encroach Node=21181
       4      .7
Encroach Node=20657
       4      .7
Encroach Node=20244
       4      .7
Encroach Node=19802
       4      .7
Encroach Node=19299
       4      .7
Encroach Node=18780
       4      .7
Encroach Node=17824
       4      .7
Encroach Node=17204
       4      .7
Encroach Node=16244
       4      .7
Encroach Node=15385
       4      .7
Encroach Node=14534
       4      .7
Encroach Node=14336
       1  3734.5 4851.45
Encroach Node=14292
       1  3734.5 4851.45
Encroach Node=14248
       1  3734.5 4851.45
Encroach Node=13383
       4      .7
Encroach Node=13068
       4      .7
Encroach Node=12404
       4      .7
Encroach Node=11913
       4      .7
Encroach Node=11444
       4      .7
Encroach Node=10946
       4      .7
Encroach Node=10468
       4      .7
Encroach Node=9967
       4      .7
Encroach Node=9461
       4      .7
Encroach Node=9004
       4      .7
Encroach Node=8556
       4      .7
Encroach Node=8035
       4      .7
Encroach Node=6922
       1    4284    6147
Computation Interval=1HOUR
Output Interval=1HOUR
Run HTab= 0
Run UNet= 0
Run PostProcess= 0
UNET Theta= 1
UNET ZTol= 0.02
UNET ZSATol= 0.1
UNET MxIter= 20
UNET MaxInSteps= 20
UNET DtIC= 0
UNET DtMin= 0
UNET MaxCRTS= 20
UNET WFStab= 2
UNET SFStab= 1
UNET WFX= 1
UNET SFX= 1
UNET Convert EG Bridges=-1
UNET Use Existing IB Tables=-1
Instantaneous Interval=1HOUR
Write IC File= 0
Write Velocity= 0
Write Detailed= 0

--- slapswamp.f01 (steady flow) ---

Flow Title=1% Chance Event
Version=September 1998 Version 2.2
Number of Profiles= 2
Profile Names=100yr,100yrFW
River Rch & RM=Slap Swamp,Slap Swamp      ,42000
     901     901
River Rch & RM=Slap Swamp,Slap Swamp      ,31540
    1497    1497
River Rch & RM=Slap Swamp,Slap Swamp      ,26973
    1760    1760
River Rch & RM=Slap Swamp,Slap Swamp      ,23130
    1960    1960
River Rch & RM=Slap Swamp,Slap Swamp      ,17204
    2170    2170
River Rch & RM=Slap Swamp,Slap Swamp      ,14534
    2280    2280
River Rch & RM=Slap Swamp,Slap Swamp      ,6922
    2325    2325
Boundary for River Rch & Prof#=Slap Swamp,Slap Swamp      , 1
Up Type= 0
Dn Type= 3
Dn Slope=.0071
Boundary for River Rch & Prof#=Slap Swamp,Slap Swamp      , 2
Up Type= 0
Dn Type= 3
Dn Slope=.0071
DSS Import GetInterval= 0
DSS Import GetPeak= 0
DSS Import FillOption= 0

--- slapswamp.g01 (geometry) ---

Geom Title=Existing
Version=Version 3.0.1  Mar 2001

River Reach=Slap Swamp      ,Slap Swamp
Reach XY= 30
      2139348.87       236852.53      2139489.17       234940.81
      2140525.91       234055.03      2140367.45       233581.21
      2141005.06        232048.2      2141745.33       231590.81
      2142297.39       231670.66      2143083.65       230968.05
      2144892.56       230701.18      2145734.39       229977.11
      2145761.62       229548.92       2146218.8       229275.98
      2146201.04       228773.72      2146909.91       227955.69
      2147247.72        226213.2      2147661.74       225712.73
      2149052.68       225076.55        2149464.       224365.23
      2150131.69       224100.22      2150107.84       223238.72
      2150766.25       222042.07      2153716.75       219803.26
      2153728.13       219105.56      2154177.17       218785.31
      2154507.85       218914.11      2155141.38       218179.63
      2155614.79       218033.44      2158340.35       214841.43
      2160437.01       213404.04      2164078.06       209428.55

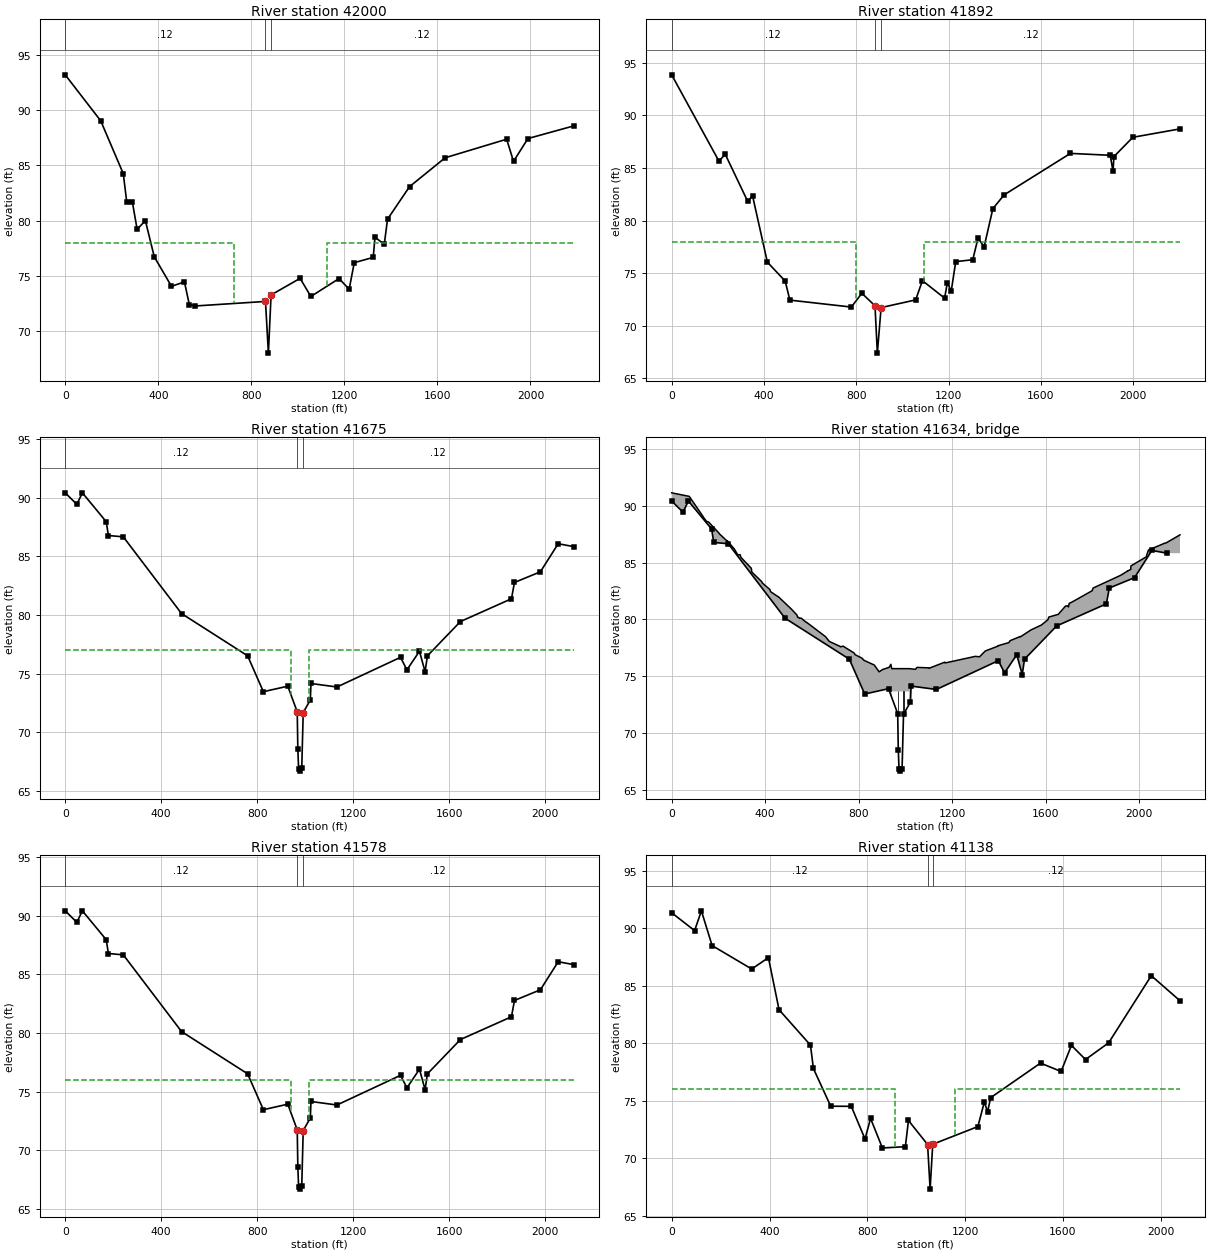
Type RM Length L Ch R = 1 ,42000   ,113.44,107.7,59.58
BEGIN DESCRIPTION:
42000
END DESCRIPTION:
XS GIS Cut Line= 6
     2140211.415       236971.92     2139471.322      236844.032
     2139305.522      236841.276     2138928.223      236750.633
     2138510.998      236554.351     2138101.439      236470.724
#Sta/Elev= 30
       0    93.2   152.6   89.04   249.6   84.25  264.44   81.71  288.51    81.7
  309.16   79.21  344.63      80  382.69   76.73  456.79   74.05  512.51   74.45
  533.47    72.4  559.63   72.27  860.93   72.68   873.4      68  884.96   73.27
 1009.72   74.77 1055.96   73.13 1176.95   74.75 1220.66   73.79  1242.5   76.19
 1324.07   76.67 1331.63    78.5 1371.49   77.85 1385.59   80.13 1480.01   83.07
 1633.23   85.69 1897.71   87.37 1927.04   85.36 1989.05   87.43  2185.1   88.57
#Mann= 3 , 0 , 0
       0     .12       0  860.93     .06       0  884.96     .12       0
#XS Ineff= 2 , 0
       0     727      78    1125       0      78
Permanent Ineff=
       F       F
Bank Sta=860.93,884.96
XS Rating Curve= 0
Exp/Cntr=.3,.1

Type RM Length L Ch R = 1 ,41892   ,208.77,217.06,259.12
BEGIN DESCRIPTION:
41892
END DESCRIPTION:
XS GIS Cut Line= 6
     2140235.965      236844.261     2139533.005      236746.628
     2139259.535      236737.419     2138949.185      236696.918
     2138510.998      236505.948     2138093.219      236410.607
#Sta/Elev= 30
       0   93.86  204.66   85.66   232.3    86.3  329.66   81.82  350.51   82.36
  414.68   76.05  491.98   74.25  512.15   72.44  778.56   71.78  824.22   73.09
  881.18    71.9  891.34    67.4  907.62   71.73 1057.39   72.46 1086.67   74.29
  1182.7   72.63 1195.04   74.11 1211.35   73.27 1231.02    76.1 1304.85   76.28
 1327.75   78.34 1354.07   77.51 1392.04   81.14 1440.99   82.45 1728.11   86.39
 1900.59   86.21 1912.47   84.71 1916.83   86.09 1998.53   87.92 2202.96   88.72
#Mann= 3 , 0 , 0
       0     .12       0  881.18     .06       0  907.62     .12       0
#XS Ineff= 2 , 0
       0     800      78    1094       0      78
Permanent Ineff=
       F       F
Bank Sta=881.18,907.62
XS Rating Curve= 0
Exp/Cntr=.5,.3

Type RM Length L Ch R = 1 ,41675   ,81.43,97.11,105.04
BEGIN DESCRIPTION:
41675
END DESCRIPTION:
XS GIS Cut Line= 6
 2140307.0104911  236625.3453781     2139891.943      236565.141
     2139160.644      236484.987     2138831.919      236365.205
     2138495.089      236227.411 2138282.4816905  236097.9112696
#Sta/Elev= 30
       0    90.4   48.43   89.42   71.57    90.4  170.91   87.94  179.99   86.76
  242.07   86.65  484.74   80.11  760.02   76.51  825.78   73.45  927.56   73.92
  966.84   71.73  969.37   68.54  972.55   66.89  978.32   66.68  985.63   66.91
  991.77   71.67 1021.48   72.75 1024.05   74.15 1132.35   73.85 1397.25   76.38
 1423.93   75.31 1476.22    76.9 1499.45   75.16  1509.5   76.51 1646.91   79.43
 1859.46   81.37 1872.09   82.76 1980.11   83.67 2054.24   86.06 2118.19   85.82
#Mann= 3 , 0 , 0
       0     .12       0  966.84     .06       0  991.77     .12       0
#XS Ineff= 2 , 0
       0  941.53      77 1016.53       0      77
Permanent Ineff=
       F       F
Bank Sta=966.84,991.77
XS Rating Curve= 0
Exp/Cntr=.5,.3

Type RM Length L Ch R = 3 ,41634   ,,,
BEGIN DESCRIPTION:
Bridge is sized based on drainage area; 75', 3-25' spans
END DESCRIPTION:
Bridge Culvert--1,0,-1,-1, 0
Deck Dist Width WeirC Skew NumUp NumDn MinLoCord MaxHiCord MaxSubmerge Is_Ogee
28,26,2.6,0, 93, 93, , , .95, 0, 0,0,,
       0   75.07  135.72  135.92  149.59  157.96  203.74  204.21  237.25  237.88
  268.37   283.3  292.51  296.35  340.47  341.15  342.66   386.1   387.1  420.17
  423.24  455.52  456.24  510.47  535.46  539.23  543.92   545.9  553.67  576.03
  577.06  658.06  674.27  721.84  722.43  732.83  780.81  781.99  785.17   814.1
  823.45  866.59  887.42   901.9  930.65  937.56  941.53  941.53 1016.53 1016.53
 1042.59 1049.63  1099.3 1100.79 1168.25 1169.73 1298.97 1316.94 1341.46 1392.28
 1397.41 1397.49 1397.63 1442.62 1447.02 1447.18 1490.51  1491.5 1536.96 1581.51
 1609.52 1613.33 1653.79 1684.96 1695.84 1697.29 1700.43 1710.88  1798.4 1802.96
 1920.98 1950.74 1951.08 1951.43 1964.05 1964.34 2030.34 2032.89 2039.72 2107.21
 2107.32 2114.91  2174.5
   91.12   90.81      89   88.97   88.61   88.56   87.55   87.52   86.88   86.91
   86.18   85.65    85.7   85.45    84.5   84.42   84.17    83.3   83.21   82.63
   82.44   81.99      82   80.94    80.4   80.19   80.18    80.1   80.12   79.74
   79.75   78.49   78.07   77.62   77.59   77.66   77.05      77    76.9    76.6
    76.4      76    75.4    75.6    75.8   76.06   75.68   75.68   75.68   75.68
   75.62   75.79   75.75   75.71   76.25   76.18   76.76   76.72   77.23   77.63
    77.7   77.69    77.7   77.97   78.12   78.13    78.5   78.47   79.08   79.51
   79.98   80.21   80.45   81.18   81.19    81.1   81.41   81.51   82.52   82.76
   83.88   84.26   84.25   84.26    84.4    84.7    85.5    85.7    86.1   86.68
   86.69   86.72   87.43
                                                                                
                                                                                
                                                                                
                                                                                
                                                           73.68   73.68
                                                                                
                                                                                
                                                                                
                                                                                
                        
       0   75.07  135.72  135.92  149.59  157.96  203.74  204.21  237.25  237.88
  268.37   283.3  292.51  296.35  340.47  341.15  342.66   386.1   387.1  420.17
  423.24  455.52  456.24  510.47  535.46  539.23  543.92   545.9  553.67  576.03
  577.06  658.06  674.27  721.84  722.43  732.83  780.81  781.99  785.17   814.1
  823.45  866.59  887.42   901.9  930.65  937.56  941.53  941.53 1016.53 1016.53
 1042.59 1049.63  1099.3 1100.79 1168.25 1169.73 1298.97 1316.94 1341.46 1392.28
 1397.41 1397.49 1397.63 1442.62 1447.02 1447.18 1490.51  1491.5 1536.96 1581.51
 1609.52 1613.33 1653.79 1684.96 1695.84 1697.29 1700.43 1710.88  1798.4 1802.96
 1920.98 1950.74 1951.08 1951.43 1964.05 1964.34 2030.34 2032.89 2039.72 2107.21
 2107.32 2114.91  2174.5
   91.12   90.81      89   88.97   88.61   88.56   87.55   87.52   86.88   86.91
   86.18   85.65    85.7   85.45    84.5   84.42   84.17    83.3   83.21   82.63
   82.44   81.99      82   80.94    80.4   80.19   80.18    80.1   80.12   79.74
   79.75   78.49   78.07   77.62   77.59   77.66   77.05      77    76.9    76.6
    76.4      76    75.4    75.6    75.8   76.06   75.68   75.68   75.68   75.68
   75.62   75.79   75.75   75.71   76.25   76.18   76.76   76.72   77.23   77.63
    77.7   77.69    77.7   77.97   78.12   78.13    78.5   78.47   79.08   79.51
   79.98   80.21   80.45   81.18   81.19    81.1   81.41   81.51   82.52   82.76
   83.88   84.26   84.25   84.26    84.4    84.7    85.5    85.7    86.1   86.68
   86.69   86.72   87.43
                                                                                
                                                                                
                                                                                
                                                                                
                                                           73.68   73.68
                                                                                
                                                                                
                                                                                
                                                                                
                        
Pier Skew, UpSta & Num, DnSta & Num=  ,966.53, 2 ,966.53, 2 , 0 , 0 , 0 ,,
       1       1
      69    73.7
       1       1
      69    73.7
Pier Skew, UpSta & Num, DnSta & Num=  ,991.53, 2 ,991.53, 2 , 0 , 0 , 0 ,,
       1       1
      69    73.7
       1       1
      69    73.7
BR Coef=-1 , 0 , 0 ,, 0 ,,,.8,0,,0,
WSPro=,,,, 1 ,,,, 0 ,,,, 0 ,,,,-1 ,-1 ,-1 , 0 , 0 , 0 , 0 , 0
BC Design=,, 0 ,, 0 ,,,,,,

Type RM Length L Ch R = 1 ,41578   ,259.47,439.73,450
BEGIN DESCRIPTION:
41578
END DESCRIPTION:
XS GIS Cut Line= 6
     2140311.833      236530.438     2139718.124      236497.595
     2139146.234      236407.534     2138957.105      236333.683
     2138512.201      236120.237     2138311.259      235975.197
#Sta/Elev= 30
       0    90.4   48.43   89.42   71.57    90.4  170.91   87.94  179.99   86.76
  242.07   86.65  484.74   80.11  760.02   76.51  825.78   73.45  927.56   73.92
  966.84   71.73  969.37   68.54  972.55   66.89  978.32   66.68  985.63   66.91
  991.77   71.67 1021.48   72.75 1024.05   74.15 1132.35   73.85 1397.25   76.38
 1423.93   75.31 1476.22    76.9 1499.45   75.16  1509.5   76.51 1646.91   79.43
 1859.46   81.37 1872.09   82.76 1980.11   83.67 2054.24   86.06 2118.19   85.82
#Mann= 3 , 0 , 0
       0     .12       0  966.84     .06       0  991.77     .12       0
#XS Ineff= 2 , 0
       0  941.53      76 1016.53       0      76
Permanent Ineff=
       F       F
Bank Sta=966.84,991.77
XS Rating Curve= 0
Exp/Cntr=.5,.3

Type RM Length L Ch R = 1 ,41138   ,364.02,469.43,498.95
BEGIN DESCRIPTION:
41138
END DESCRIPTION:
XS GIS Cut Line= 3
     2140378.045      236335.188     2138635.054      235990.739
     2138375.089      235837.718
#Sta/Elev= 30
       0   91.33   93.81   89.78  121.44    91.5  165.32   88.48  327.26   86.44
  395.55   87.43     439    82.9  567.56   79.82  579.41   77.79   650.3   74.51
  734.41    74.5  790.49   71.66  813.19   73.45  861.55   70.88  955.43   70.99
  968.13   73.27 1046.33   71.18 1056.71    67.3 1067.36    71.2 1251.97   72.74
 1278.52   74.89 1291.55      74 1304.01   75.25 1508.01   78.26 1592.26   77.53
  1634.4    79.8    1692   78.57 1786.51   80.02 1960.97   85.86 2078.36   83.68
#Mann= 3 , 0 , 0
       0     .12       0 1046.33     .06       0 1067.36     .12       0
#XS Ineff= 2 , 0
       0     915      76    1160       0      76
Permanent Ineff=
       F       F
Bank Sta=1046.33,1067.36
XS Rating Curve= 0
Exp/Cntr=.3,.1

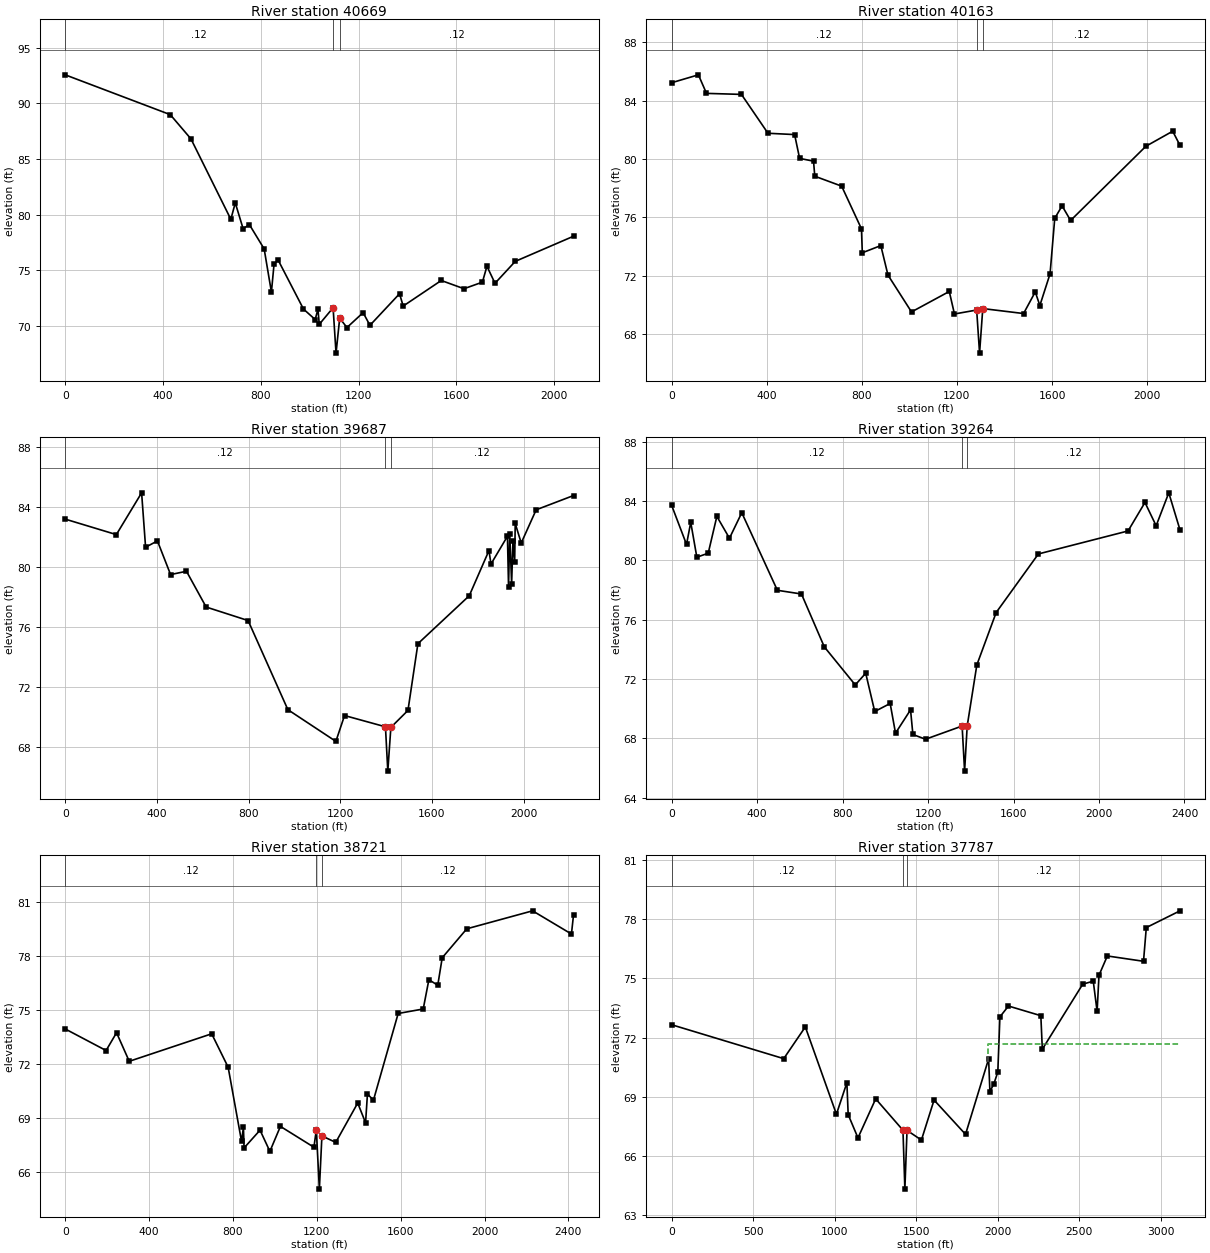
Type RM Length L Ch R = 1 ,40669   ,603.1,505.95,425.96
BEGIN DESCRIPTION:
40669
END DESCRIPTION:
XS GIS Cut Line= 5
     2140465.683      236125.275     2140223.198      236033.667
     2139815.692      235805.598     2138931.922       235532.25
     2138512.568      235444.921
#Sta/Elev= 30
       0   92.57  429.83   88.99  514.49   86.81  677.64   79.58  695.76   81.06
  727.78   78.74  753.63    79.1  813.95   76.92   843.6   73.04  854.46   75.56
  871.29   75.91  974.86   71.51 1022.68   70.57 1033.98    71.5 1039.42   70.14
 1095.96   71.63 1107.98   67.55    1123   70.69 1152.69   69.85 1218.74   71.19
 1246.74   70.05 1367.84   72.89 1382.68   71.78 1538.48   74.08 1631.44   73.34
 1706.83   73.93 1725.32   75.36 1758.38   73.83 1841.26    75.8 2079.63   78.06
#Mann= 3 , 0 , 0
       0     .12       0 1095.96     .06       0    1123     .12       0
Bank Sta=1095.96,1123
XS Rating Curve= 0
Exp/Cntr=.3,.1

Type RM Length L Ch R = 1 ,40163   ,193.52,475.7,550.43
BEGIN DESCRIPTION:
40163
END DESCRIPTION:
XS GIS Cut Line= 5
     2140668.301      235652.986     2140225.015      235347.867
     2139887.802      235237.101     2139153.284      235156.606
     2138650.047      235101.224
#Sta/Elev= 30
       0   85.22  112.39   85.76  146.46   84.49  293.45   84.42  405.08   81.76
  517.12   81.67  538.15   80.04  596.74   79.85  601.95   78.82  715.02   78.14
  798.27   75.22  801.94   73.58  879.77   74.07  909.89   72.05 1008.86   69.53
 1167.73   70.93 1189.49   69.39 1282.96   69.66 1295.13   66.71 1308.62   69.76
 1480.25   69.42 1529.39    70.9 1548.75   69.97 1591.69   72.14 1611.38   75.94
 1642.29   76.79 1678.08   75.79 1994.77   80.87 2107.55    81.9 2138.27   80.93
#Mann= 3 , 0 , 0
       0     .12       0 1282.96     .06       0 1308.62     .12       0
Bank Sta=1282.96,1308.62
XS Rating Curve= 0
Exp/Cntr=.3,.1

Type RM Length L Ch R = 1 ,39687   ,237.33,423.39,506.99
BEGIN DESCRIPTION:
39687
END DESCRIPTION:
XS GIS Cut Line= 3
     2140805.639      235542.962     2140108.786      235024.891
     2138898.118      234428.392
#Sta/Elev= 30
       0   83.18  223.17   82.15  333.38   84.93   350.7   81.31   402.4   81.73
  459.75   79.49  529.11   79.71  614.92   77.33  798.01   76.43  971.55    70.5
    1181   68.39 1218.81   70.11 1397.32   69.36 1407.57   66.41 1420.96   69.32
 1495.52   70.45 1538.92   74.89 1762.93   78.08 1849.03   81.09 1857.74   80.19
 1929.63   82.04 1934.36   78.68 1939.63   82.21 1947.89   78.89 1953.58    81.7
 1961.08   80.34 1963.56   82.89 1989.73   81.59 2054.88    83.8 2217.97   84.75
#Mann= 3 , 0 , 0
       0     .12       0 1397.32     .06       0 1420.96     .12       0
Bank Sta=1397.32,1420.96
XS Rating Curve= 0
Exp/Cntr=.3,.1

Type RM Length L Ch R = 1 ,39264   ,752.93,542.67,204.6
BEGIN DESCRIPTION:
39264
END DESCRIPTION:
XS GIS Cut Line= 5
     2140958.669      235352.216     2140360.711      234920.151
     2140263.446       234843.01      2139649.67       234237.62
     2139058.192      233955.905
#Sta/Elev= 30
       0   83.71   69.47   81.08   89.27   82.57  117.81   80.22  171.03   80.49
  211.45   82.97  270.47    81.5  328.08   83.22  494.69   77.99   607.5   77.74
  714.19   74.18  859.25   71.61  908.13    72.4  950.41   69.82 1022.62   70.36
 1047.62   68.36 1117.97   69.93 1128.97   68.27 1188.06   67.95 1359.38   68.84
 1370.93    65.8 1383.12   68.84  1428.3   72.96 1518.68   76.49  1716.3   80.44
 2136.03   81.99 2215.09   83.91 2267.48   82.34 2326.64   84.56 2379.11   82.06
#Mann= 3 , 0 , 0
       0     .12       0 1359.38     .06       0 1383.12     .12       0
Bank Sta=1359.38,1383.12
XS Rating Curve= 0
Exp/Cntr=.3,.1

Type RM Length L Ch R = 1 ,38721   ,652.43,934.57,950
BEGIN DESCRIPTION:
38721
END DESCRIPTION:
XS GIS Cut Line= 3
      2141441.88      234498.358     2139379.696      233910.539
      2139116.21        233815.6
#Sta/Elev= 30
       0   73.93  194.93   72.73  244.89   73.72  305.43   72.13  698.61   73.66
  777.18    71.8  840.97   67.68  850.06   68.46  853.01   67.31   929.2    68.3
  976.19   67.12 1026.41   68.51 1186.24   67.35 1197.65   68.32 1212.19   65.02
 1224.32   67.98 1290.22   67.62 1395.09   69.81 1432.52   68.71 1441.49   70.31
 1470.16   69.97 1588.02   74.79 1707.51   75.04 1734.49   76.67 1776.84   76.36
 1798.09   77.89 1915.25    79.5 2229.13    80.5 2414.41   79.21 2424.39   80.28
#Mann= 3 , 0 , 0
       0     .12       0 1197.65     .06       0 1224.32     .12       0
Bank Sta=1197.65,1224.32
XS Rating Curve= 0
Exp/Cntr=.3,.1

Type RM Length L Ch R = 1 ,37787   ,363.31,448.28,478.99
BEGIN DESCRIPTION:
37787
END DESCRIPTION:
XS GIS Cut Line= 4
     2141801.238      233957.564     2141609.002      233900.165
     2139444.042      233256.109     2138806.148      233090.564
#Sta/Elev= 30
       0   72.65  687.45   70.93  819.86   72.54 1010.65   68.11 1074.86   69.71
 1082.78   68.09 1142.81   66.91  1251.5   68.89 1418.86    67.3 1430.58   64.31
 1443.81   67.29 1532.07    66.8 1609.66   68.83 1802.77   67.09 1944.34   70.92
 1952.26   69.26 1976.48   69.65 2000.69   70.25 2013.54   73.05 2066.05    73.6
 2264.62   73.11 2273.85   71.41 2521.84   74.71 2586.21   74.86 2609.88   73.33
 2621.42   75.16 2672.62   76.14 2894.49   75.87 2911.65   77.58 3118.38   78.43
#Mann= 3 , 0 , 0
       0     .12       0 1418.86     .06       0 1443.81     .12       0
#XS Ineff= 2 , 0
                         1939.14           71.68
Permanent Ineff=
       F       F
Bank Sta=1418.86,1443.81
XS Rating Curve= 0
Exp/Cntr=.3,.1

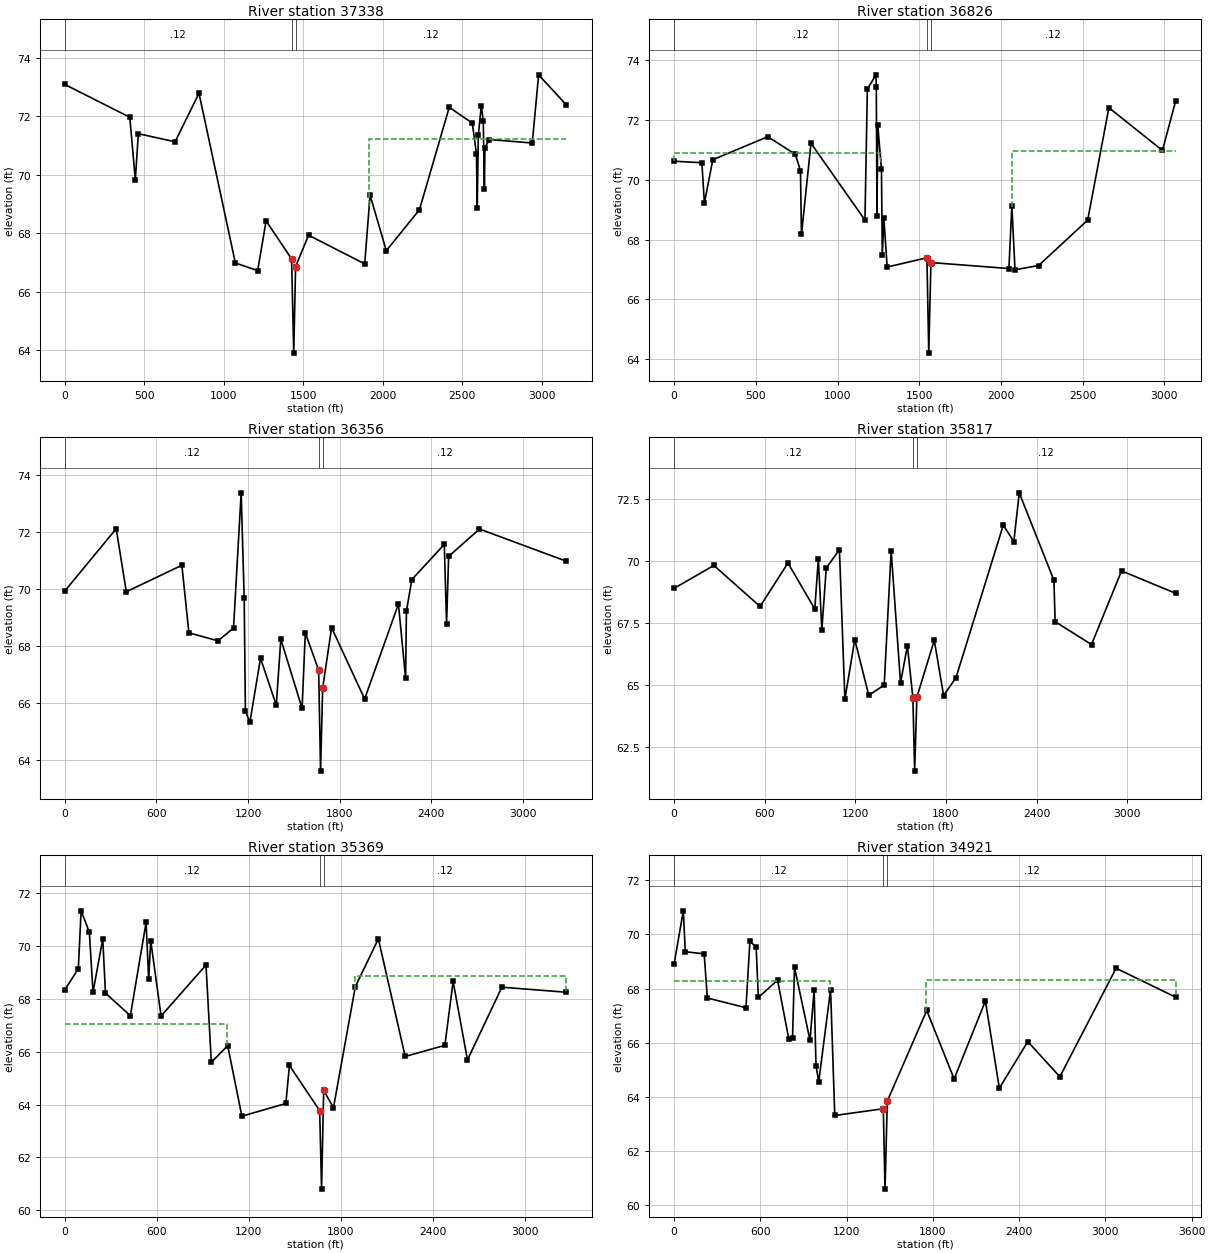
Type RM Length L Ch R = 1 ,37338   ,363.77,512.49,540.28
BEGIN DESCRIPTION:
37338
END DESCRIPTION:
XS GIS Cut Line= 6
     2141849.871      233806.635     2141536.275      233560.119
     2140934.239        233248.2     2140293.631      233109.011
     2139619.806      232695.973     2139025.833      232476.789
#Sta/Elev= 30
       0   73.08  408.54   71.96  443.25   69.82   462.3    71.4  693.29   71.12
  843.96   72.78 1072.83   66.98 1213.16   66.72 1266.22   68.42 1426.49   67.12
 1440.15    63.9 1451.74   66.86 1533.67   67.93 1886.61   66.95 1920.46    69.3
 2022.54    67.4 2231.18    68.8 2418.65    72.3 2563.81   71.76 2589.91   70.71
 2594.62   68.86  2601.7   71.35 2620.31   72.36 2632.72   71.83 2639.76   69.51
 2643.24   70.92 2670.78    71.2 2940.94   71.08 2980.99   73.41 3155.95   72.38
#Mann= 3 , 0 , 0
       0     .12       0 1426.49     .06       0 1451.74     .12       0
#XS Ineff= 2 , 0
       0                 1915.24       0   71.23
Permanent Ineff=
       F       F
Bank Sta=1426.49,1451.74
XS Rating Curve= 0
Exp/Cntr=.3,.1

Type RM Length L Ch R = 1 ,36826   ,430.92,470,473.05
BEGIN DESCRIPTION:
36826
END DESCRIPTION:
XS GIS Cut Line= 4
     2142019.246       233509.81     2141542.169      233150.765
     2139866.725      232245.702     2139349.491      232010.588
#Sta/Elev= 30
       0   70.62  169.82   70.57  185.05   69.22  236.65   70.67  573.34   71.44
  742.07   70.85  773.18    70.3  779.16   68.17  837.54   71.22 1167.78   68.65
 1182.52   73.03    1235   73.51 1237.32   73.09  1241.3   68.79  1246.1   71.83
 1268.79   70.35 1273.92   67.48 1283.36   68.71 1303.76   67.08 1547.04   67.39
 1558.27    64.2  1571.6   67.23 2048.76   67.03 2066.89   69.12 2086.19   66.99
 2230.41   67.13 2530.89   68.65 2660.57   72.41 2988.31   70.98 3069.53   72.64
#Mann= 3 , 0 , 0
       0     .12       0 1547.04     .06       0  1571.6     .12       0
#XS Ineff= 2 , 0
       0 1266.21   70.91 2066.55       0   70.95
Permanent Ineff=
       F       F
Bank Sta=1547.04,1571.6
XS Rating Curve= 0
Exp/Cntr=.3,.1

Type RM Length L Ch R = 1 ,36356   ,288.08,539.44,547.93
BEGIN DESCRIPTION:
36356
END DESCRIPTION:
XS GIS Cut Line= 5
     2142307.687      233194.537     2142014.623      232935.584
     2141003.325      232344.268     2140814.372      232234.934
     2139520.749      231465.354
#Sta/Elev= 30
       0   69.93  336.29   72.11   402.6    69.9  766.52   70.83  812.57   68.46
 1003.41   68.18 1105.06   68.63 1155.06   73.37 1174.85   69.67 1182.85   65.72
 1212.19   65.32 1281.75   67.57 1385.18   65.92  1414.8   68.24 1554.19   65.81
 1575.26   68.46 1662.77   67.15  1675.2   63.61 1689.06   66.52 1747.52   68.64
 1964.01   66.14 2185.48   69.47  2232.3   66.87  2237.8   69.22  2273.5   70.33
 2485.81   71.56 2500.91   68.78 2514.35   71.14 2716.52    72.1  3286.1   70.97
#Mann= 3 , 0 , 0
       0     .12       0 1662.77     .06       0 1689.06     .12       0
Bank Sta=1662.77,1689.06
XS Rating Curve= 0
Exp/Cntr=.3,.1

Type RM Length L Ch R = 1 ,35817   ,273.79,447.18,524.87
BEGIN DESCRIPTION:
35817
END DESCRIPTION:
XS GIS Cut Line= 6
  2142419.538315  233038.6153747     2142167.346      232722.242
     2141519.505      232231.949     2141008.026      231740.594
      2140416.24      231292.591 2139921.0680296  230868.0825213
#Sta/Elev= 30
       0   68.89   263.2   69.81  568.98   68.16  753.52   69.91  931.14   68.06
  954.92   70.08  977.77   67.22 1007.29   69.71 1094.29   70.44 1130.59   64.43
 1196.02   66.83 1288.54   64.59 1390.77      65 1436.86   70.39 1498.99   65.09
 1544.44   66.58 1580.69   64.48 1592.44   61.54 1607.25   64.52 1722.35    66.8
 1784.21   64.58 1866.19    65.3  2179.1   71.43 2249.14   70.77 2284.93   72.73
 2514.56   69.21 2522.51   67.55 2763.43   66.63 2962.26   69.59 3320.77   68.69
#Mann= 3 , 0 , 0
       0     .12       0 1580.69     .06       0 1607.25     .12       0
Bank Sta=1580.69,1607.25
XS Rating Curve= 0
Exp/Cntr=.3,.1

Type RM Length L Ch R = 1 ,35369   ,129.18,448.53,475.82
BEGIN DESCRIPTION:
35369
END DESCRIPTION:
XS GIS Cut Line= 4
     2142639.729      233003.361     2142519.981      232789.971
     2140885.927      230903.502      2140588.78      230461.056
#Sta/Elev= 30
       0   68.35   87.59   69.13  106.14   71.33  159.74   70.52  183.67   68.25
  247.37   70.27  264.73   68.22  427.45   67.36  530.03   70.89  546.99   68.74
  560.23    70.2  627.99   67.35  921.02   69.28  955.83    65.6 1062.69   66.23
  1155.2   63.56  1442.3   64.04 1465.52   65.48 1662.91   63.77 1675.37    60.8
 1689.09   64.54 1752.99   63.88 1895.65   68.46 2046.02   70.27 2221.01   65.82
 2480.17   66.24 2533.89   68.66 2627.53   65.69 2852.32   68.44 3273.44   68.25
#Mann= 3 , 0 , 0
       0     .12       0 1662.91     .06       0 1689.09     .12       0
#XS Ineff= 2 , 0
         1055.18   67.05 1891.35           68.86
Permanent Ineff=
       F       F
Bank Sta=1662.91,1689.09
XS Rating Curve= 0
Exp/Cntr=.3,.1

Type RM Length L Ch R = 1 ,34921   ,490,484.48,345.46
BEGIN DESCRIPTION:
34921
END DESCRIPTION:
XS GIS Cut Line= 6
     2142696.747      232953.052     2141958.875      231889.845
     2141931.236      231263.858     2141026.101      230568.778
     2140879.773      230402.586     2140684.859      230345.558
#Sta/Elev= 30
       0   68.91   63.89   70.87   77.52   69.36  208.92   69.28  231.08   67.65
  499.53   67.29   527.3   69.75  570.56   69.52   585.8   67.67  719.47   68.31
  797.83   66.13   823.4   66.16  837.38   68.78  945.05   66.09  973.85   67.93
  986.98   65.15 1005.76   64.55 1088.19   67.96  1117.4   63.31 1454.93   63.56
 1467.01   60.59 1482.84   63.84 1757.22   67.19 1947.64   64.66 2165.33   67.54
 2262.27   64.32 2460.16   66.04 2683.19   64.74 3074.32   68.75 3489.03   67.68
#Mann= 3 , 0 , 0
       0     .12       0 1454.93     .06       0 1482.84     .12       0
#XS Ineff= 2 , 0
         1087.03   68.29 1751.99           68.31
Permanent Ineff=
       F       F
Bank Sta=1454.93,1482.84
XS Rating Curve= 0
Exp/Cntr=.3,.1

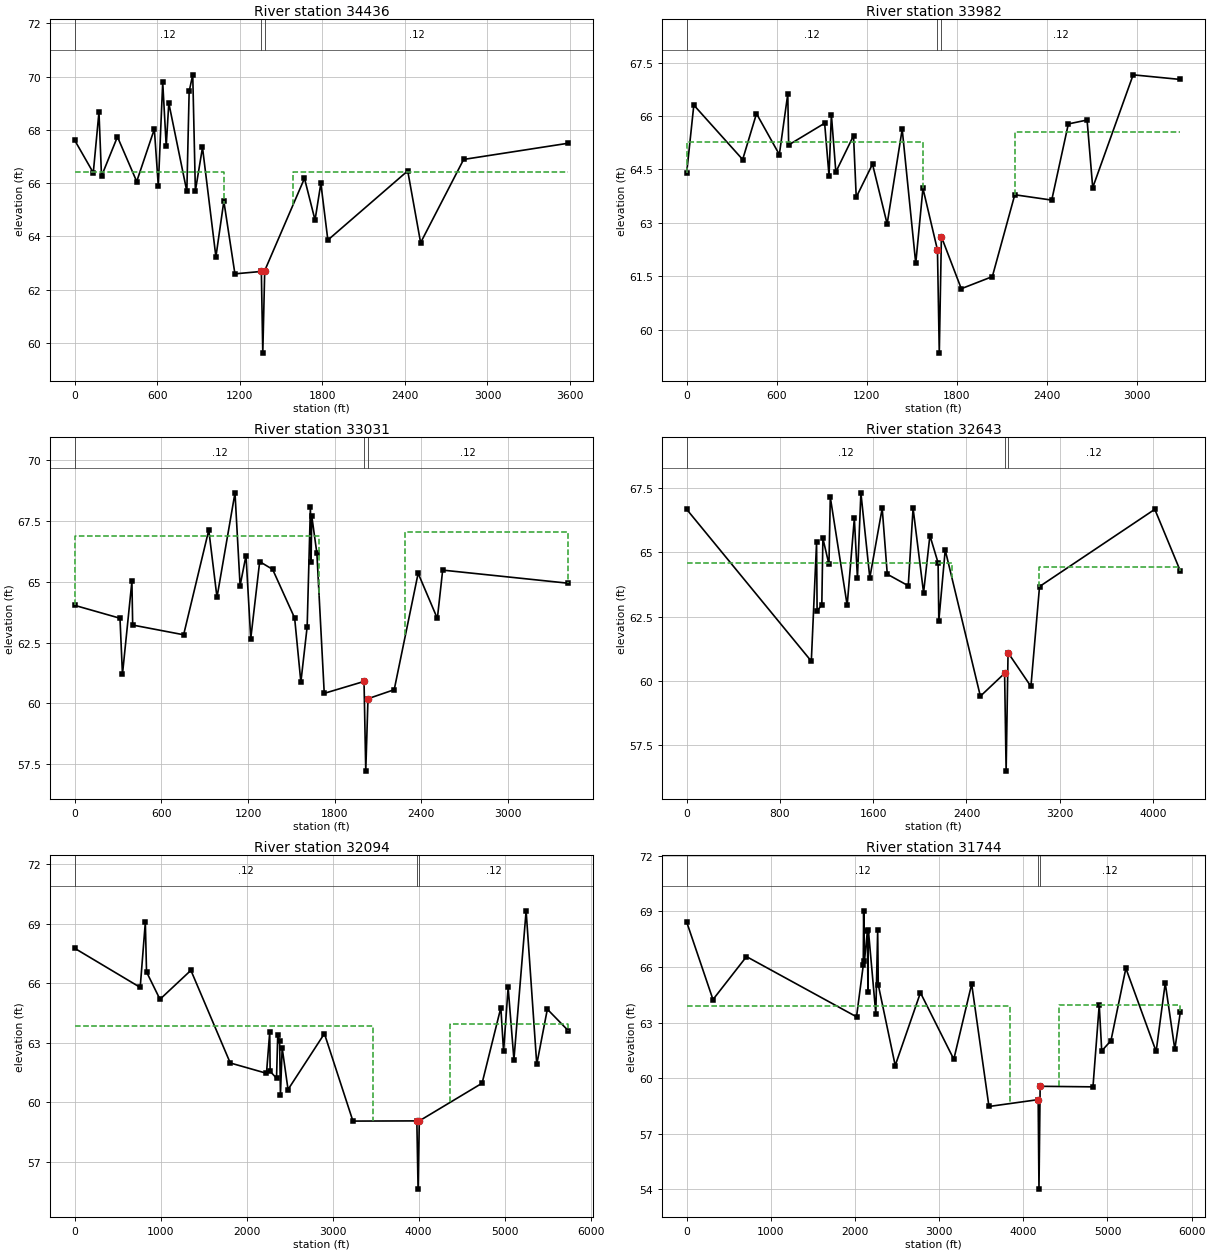
Type RM Length L Ch R = 1 ,34436   ,414.93,454.14,623.55
BEGIN DESCRIPTION:
34436
END DESCRIPTION:
XS GIS Cut Line= 6
      2143006.87       232821.55      2142109.36      231018.221
     2142067.964      230935.046     2140904.822      230291.439
     2140810.927      230203.312     2140793.807      230187.243
#Sta/Elev= 30
       0   67.61  134.87   66.39  176.23   68.67  194.68   66.26  310.49   67.74
  450.58   66.06  578.75   68.03  607.53    65.9  639.66   69.79  665.06   67.39
  683.84   69.01     815   65.69  831.81   69.45  857.91   70.07  877.03   65.71
  928.77   67.34 1026.29   63.23 1083.97   65.32 1164.48   62.59 1356.57   62.68
 1367.06   59.61 1381.12   62.71 1670.15   66.18 1746.81   64.61  1789.2   65.99
 1840.08   63.86 2420.68   66.46 2514.38   63.76 2827.16   66.89 3588.82    67.5
#Mann= 3 , 0 , 0
       0     .12       0 1356.57     .06       0 1381.12     .12       0
#XS Ineff= 2 , 0
          1087.6    66.4 1588.17            66.4
Permanent Ineff=
       F       F
Bank Sta=1356.57,1381.12
XS Rating Curve= 0
Exp/Cntr=.3,.1

Type RM Length L Ch R = 1 ,33982   ,688.74,951,971
BEGIN DESCRIPTION:
33982
END DESCRIPTION:
XS GIS Cut Line= 3
     2143445.258      232897.389     2142322.523      230299.538
     2142180.675      229865.161
#Sta/Elev= 30
       0    64.4   47.65   66.31  372.92   64.78  464.95   66.07  617.03   64.92
  673.25   66.62  679.14   65.19  918.69    65.8  947.81   64.33  963.55   66.04
   993.3   64.43 1111.02   65.45 1129.06   63.72  1237.4   64.65 1334.83   62.97
 1435.04   65.63 1525.26   61.86 1573.16   63.97 1669.81   62.24    1682   59.34
 1696.11   62.61 1828.41   61.15  2035.2   61.49 2184.66   63.79 2430.67   63.64
 2541.31   65.78 2665.98   65.89 2703.57   63.99 2972.75   67.16 3287.03   67.03
#Mann= 3 , 0 , 0
       0     .12       0 1669.81     .06       0 1696.11     .12       0
#XS Ineff= 2 , 0
       0 1572.81   65.27 2186.01       0   65.55
Permanent Ineff=
       F       F
Bank Sta=1669.81,1696.11
XS Rating Curve= 0
Exp/Cntr=.3,.1

Type RM Length L Ch R = 1 ,33031   ,305.19,388.33,411.73
BEGIN DESCRIPTION:
33031
END DESCRIPTION:
XS GIS Cut Line= 6
     2144034.917      232960.362     2143752.077      231960.566
     2143554.145      231157.717     2143459.773      230674.033
     2143270.942      229964.153     2143135.933      229668.456
#Sta/Elev= 30
       0   64.03  313.38    63.5  330.49   61.19  395.94   65.02  401.26   63.22
  754.04   62.82  928.14   67.13  985.03   64.36 1109.73   68.66    1145   64.84
 1185.94   66.08 1218.79   62.66 1280.67   65.83 1370.31   65.51 1522.65   63.51
 1565.85   60.87 1609.33   63.15    1632   68.09 1636.52   65.83 1640.98   67.72
 1676.74   66.17 1727.67   60.41 2003.17    60.9 2015.13   57.21 2030.51   60.19
 2212.11   60.56 2377.81   65.35 2510.84   63.49 2547.65   65.48 3418.38   64.94
#Mann= 3 , 0 , 0
       0     .12       0 2003.17     .06       0 2030.51     .12       0
#XS Ineff= 2 , 0
         1692.26   66.89 2289.53           67.05
Permanent Ineff=
       F       F
Bank Sta=2003.17,2030.51
XS Rating Curve= 0
Exp/Cntr=.3,.1

Type RM Length L Ch R = 1 ,32643   ,600,549,540
BEGIN DESCRIPTION:
32643
END DESCRIPTION:
XS GIS Cut Line= 5
     2144258.187       233618.72     2143949.452      231356.565
     2143847.156      230508.012     2143606.726      229648.398
     2143485.879      229483.607
#Sta/Elev= 30
       0   66.67 1069.37   60.77 1114.36   65.39 1118.93   62.73 1159.24   62.95
 1168.57   65.54 1220.63   64.53 1232.19   67.14 1376.97   62.94 1438.31   66.32
 1464.85      64 1494.55   67.31 1571.06   64.01 1677.28   66.71 1720.86   64.15
 1900.76    63.7 1942.18   66.71 2032.14   63.43 2086.53   65.65 2156.74   64.59
 2162.98   62.34 2217.83   65.09 2519.46   59.41  2727.2    60.3 2740.34    56.5
 2756.84    61.1    2953   59.79 3026.84   63.67 4015.53   66.67 4234.78   64.27
#Mann= 3 , 0 , 0
       0     .12       0  2727.2     .06       0 2756.84     .12       0
#XS Ineff= 2 , 0
         2275.31    64.6 3026.17           64.42
Permanent Ineff=
       F       F
Bank Sta=2727.2,2756.84
XS Rating Curve= 0
Exp/Cntr=.3,.1

Type RM Length L Ch R = 1 ,32094   ,807.53,350.11,109.14
XS GIS Cut Line= 6
     2144152.699      234799.683     2144373.874      233593.752
     2144516.534      232332.892     2144603.157      231295.782
     2144110.953      229996.141     2143561.056      229393.242
#Sta/Elev= 30
       0   67.76  761.45   65.79  821.15   69.08  835.04   66.57  991.37   65.19
 1350.99   66.65  1808.7   61.98  2230.1   61.46 2268.02   63.55 2272.58   61.56
 2346.83   61.21 2361.01   63.39 2382.55   63.09  2392.4   60.37 2412.35   62.74
 2480.72   60.64 2903.78   63.46 3235.39   59.05 3978.61   59.06 3992.96   55.62
 4007.32   59.06 4737.49   60.96 4955.51   64.77 4987.15   62.56 5040.34   65.79
 5107.64   62.15 5249.45   69.65 5373.24   61.91 5496.25   64.69 5741.46    63.6
#Mann= 3 , 0 , 0
       0     .12       0 3978.61     .06       0 4007.32     .12       0
#XS Ineff= 2 , 0
         3467.58   63.83  4368.6           63.92
Permanent Ineff=
       F       F
Bank Sta=3978.61,4007.32
XS Rating Curve= 0
Exp/Cntr=.3,.1

Type RM Length L Ch R = 1 ,31744   ,210,204,195
XS GIS Cut Line= 6
     2147064.837      234246.745     2146345.811       233155.05
      2145157.39      231373.059     2144698.955       230635.09
     2144005.712      229695.857     2143759.722      229405.142
#Sta/Elev= 30
       0   68.43  312.71   64.24  710.97   66.56  2018.4   63.31 2098.13   66.08
 2103.11   69.03 2112.17   66.31 2147.14   67.93 2154.28   64.66 2158.94   68.01
 2247.45   63.48 2269.68   67.97 2276.83   65.04 2478.12   60.68 2777.76   64.61
 3174.25   61.02 3386.59   65.08 3591.96   58.47 4176.66   58.84 4186.17   54.01
 4200.12   59.56 4827.78   59.53 4902.28   63.96  4931.7   61.47 5041.38   62.02
 5218.69   65.93 5578.31   61.44 5686.47   65.13  5800.2   61.56 5866.09   63.57
#Mann= 3 , 0 , 0
       0     .12       0 4176.66     .06       0 4200.12     .12       0
#XS Ineff= 2 , 0
         3836.18   63.92 4430.03           63.95
Permanent Ineff=
       F       F
Bank Sta=4176.66,4200.12
XS Rating Curve= 0
Exp/Cntr=.3,.1