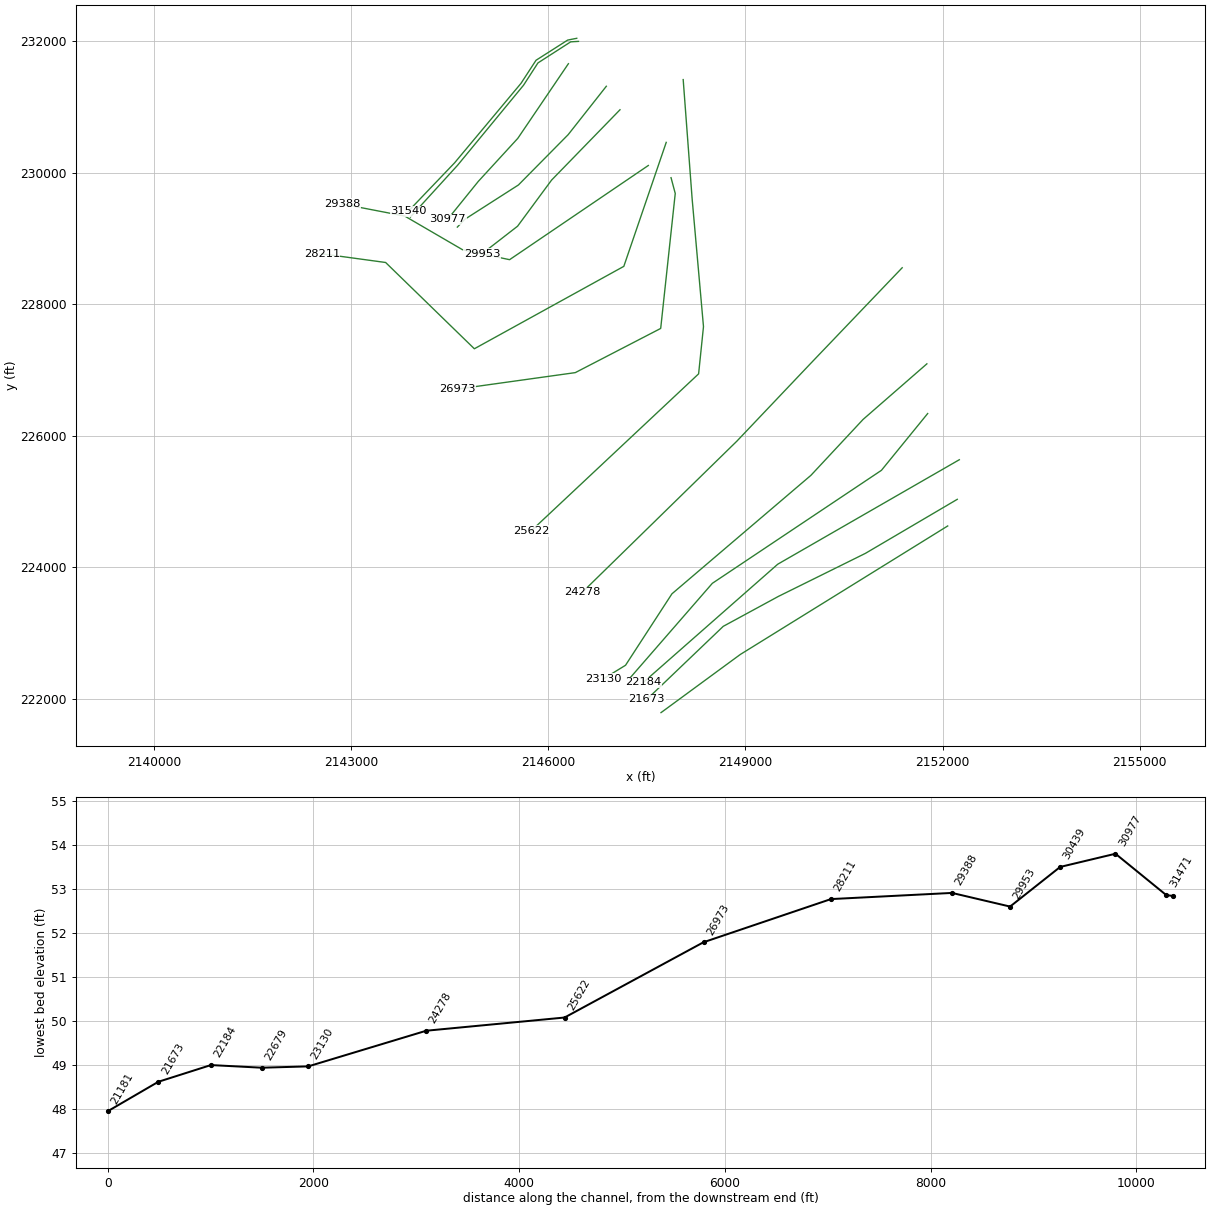
HEC-RAS study slapswamp.prj: Slap Swamp

--- slapswamp.g01 (geometry) --- (continued)

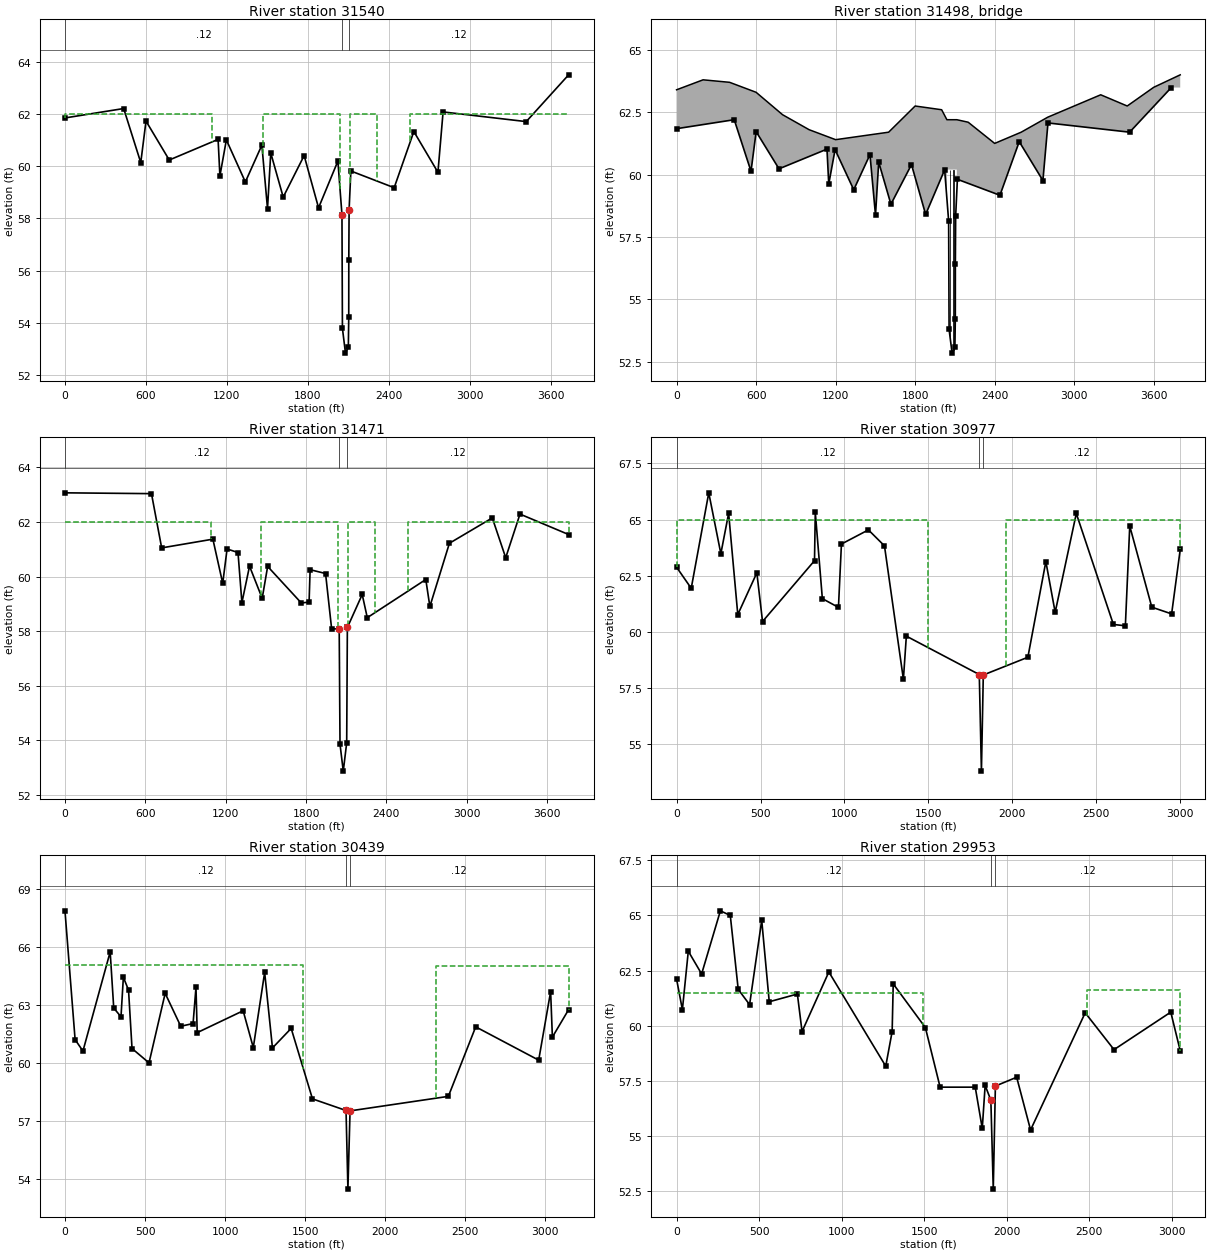
Type RM Length L Ch R = 1 ,31540   ,78.96,69.38,67
BEGIN DESCRIPTION:
31540
END DESCRIPTION:
XS GIS Cut Line= 6
     2146432.426      232045.206     2146294.599      232018.313
     2145812.763      231711.282      2145584.17       231360.55
     2144572.355       230150.32     2143869.871      229416.976
#Sta/Elev= 30
       0   61.84  435.08    62.2  561.65   60.13  600.48   61.72  772.87   60.23
 1134.73   61.02 1148.18   59.62    1196      61 1336.67   59.39 1459.18    60.8
 1500.94   58.37 1525.01    60.5 1617.25   58.81 1772.44    60.4 1879.27    58.4
 2022.55   60.19 2052.72   58.14 2056.12   53.79 2078.79   52.84 2099.96   53.07
 2102.98   54.22 2103.36   56.42 2105.62   58.33 2118.77   59.81  2439.7   59.17
  2585.4   61.32 2763.95   59.76 2802.16   62.07 3418.37    61.7 3732.62   63.49
#Mann= 3 , 0 , 0
       0     .12       0 2052.72     .06       0 2105.62     .12       0
#XS Ineff= 4 ,-1
       0    1090      62    1465 2039.54      62 2114.54    2315      62
    2560    4000      62
Permanent Ineff=
       F       F       F       F
Bank Sta=2052.72,2105.62
XS Rating Curve= 0
Exp/Cntr=.5,.3

Type RM Length L Ch R = 3 ,31498   ,,,
BEGIN DESCRIPTION:
Bridge is sized based on drainage area; 60', 3-20' spans
END DESCRIPTION:
Bridge Culvert--1,0,-1,-1, 0
Deck Dist Width WeirC Skew NumUp NumDn MinLoCord MaxHiCord MaxSubmerge Is_Ogee
29,26,2.6,0, 22, 22, , , .95, 0, 0,0,,
       0     200     400     600     800    1000    1200    1600    1800    2000
 2039.54 2039.54 2114.54 2114.54    2200    2400    2600    2800    3200    3400
    3600    3800
    63.4    63.8    63.7    63.3    62.4    61.8    61.4    61.7   62.75    62.6
    62.2    62.2    62.2    62.2    62.1   61.25    61.7    62.3    63.2   62.75
    63.5      64
                                                                                
            60.2    60.2
                
       0     200     400     600     800    1000    1200    1600    1800    2000
 2039.54 2039.54 2114.54 2114.54    2200    2400    2600    2800    3200    3400
    3600    3800
    63.4    63.8    63.7    63.3    62.4    61.8    61.4    61.7   62.75    62.6
    62.2    62.2    62.2    62.2    62.1   61.25    61.7    62.3    63.2   62.75
    63.5      64
                                                                                
            60.2    60.2
                
Pier Skew, UpSta & Num, DnSta & Num=  ,2064.54, 2 ,2064.54, 2 , 0 , 0 , 0 ,,
       1       1
      52    60.5
       1       1
      52    60.5
Pier Skew, UpSta & Num, DnSta & Num=  ,2089.54, 2 ,2089.54, 2 , 0 , 0 , 0 ,,
       1       1
      52    60.5
       1       1
      52    60.5
BR Coef=-1 , 0 , 0 ,, 0 ,,,.8,0,,0,
WSPro=,,,, 1 ,,,, 0 ,,,, 0 ,,,,-1 ,-1 ,-1 , 0 , 0 , 0 , 0 , 0
BC Design=,, 0 ,, 0 ,,,,,,

Type RM Length L Ch R = 1 ,31471   ,500,494.13,419.99
BEGIN DESCRIPTION:
31471
END DESCRIPTION:
XS GIS Cut Line= 6
     2146458.579      231998.288     2146340.541      231991.419
     2145841.897      231670.942     2145622.269      231331.416
     2144620.498      230116.741      2143900.98      229328.026
#Sta/Elev= 30
       0   63.07  645.81   63.04  721.92   61.05 1104.32   61.37 1177.72   59.75
 1210.27   61.01 1291.82   60.88 1320.95   59.04 1377.91   60.38 1472.43    59.2
 1513.21   60.37 1764.28   59.03 1822.53   59.06 1830.27   60.25 1945.56   60.11
 1990.92   58.08 2047.45   58.08 2053.45   53.85 2077.76   52.86 2103.34    53.9
 2108.39   58.13 2219.25   59.34 2257.08   58.49 2693.97   59.89 2724.33    58.9
 2870.25   61.22 3190.42   62.15 3290.56   60.69 3397.15   62.29 3760.44   61.54
#Mann= 3 , 0 , 0
       0     .12       0 2047.45     .06       0 2108.39     .12       0
#XS Ineff= 4 ,-1
       0    1090      62    1465 2039.54      62 2114.54    2315      62
    2560    4000      62
Permanent Ineff=
       F       F       F       F
Bank Sta=2047.45,2108.39
XS Rating Curve= 0
Exp/Cntr=.5,.3

Type RM Length L Ch R = 1 ,30977   ,580.47,537.75,279.02
BEGIN DESCRIPTION:
30977
END DESCRIPTION:
XS GIS Cut Line= 4
     2146305.083      231658.876     2145535.877      230524.782
     2144933.841      229869.082     2144469.098      229294.793
#Sta/Elev= 30
       0   62.88    87.3   61.94  191.73   66.19  263.69   63.48   310.1   65.28
  364.57   60.77  478.05   62.63  511.94   60.46   821.4   63.17  826.08   65.32
  868.13   61.48     964   61.09  981.74   63.91 1142.34   64.54 1238.02   63.83
 1350.73   57.89 1368.31   59.81 1802.61    58.1  1815.4    53.8 1826.56   58.08
 2091.97   58.87 2199.13   63.13 2254.51   60.87 2380.38   65.27 2601.28   60.33
 2672.52   60.27 2698.65   64.71 2829.97    61.1    2948    60.8 2999.28   63.67
#Mann= 3 , 0 , 0
       0     .12       0 1802.61     .06       0 1826.56     .12       0
#XS Ineff= 2 , 0
       0    1498      65    1962       0      65
Permanent Ineff=
       F       F
Bank Sta=1802.61,1826.56
XS Rating Curve= 0
Exp/Cntr=.3,.1

Type RM Length L Ch R = 1 ,30439   ,303.11,486.57,567.41
BEGIN DESCRIPTION:
30439
END DESCRIPTION:
XS GIS Cut Line= 5
     2146882.249      231315.952     2146301.795      230580.322
     2145545.082      229815.466     2144727.149      229291.976
     2144615.448      229174.781
#Sta/Elev= 30
       0   67.87   63.28   61.22  112.28   60.63  282.28   65.75  304.57   62.85
  349.91    62.4  364.71   64.44     397   63.78  418.81   60.76  524.92   60.02
   625.8   63.61  723.12   61.91  800.12   62.05  818.27   63.92  825.91   61.58
 1112.88   62.71 1176.26   60.81 1247.25   64.69 1296.02   60.79 1412.82    61.8
 1545.92   58.16 1755.55   57.56 1767.29    53.5 1780.63   57.54 2394.69   58.29
 2565.49   61.88 2958.89   60.16 3033.48    63.7 3044.45   61.35    3146   62.77
#Mann= 3 , 0 , 0
       0     .12       0 1755.55     .06       0 1780.63     .12       0
#XS Ineff= 2 , 0
       0 1489.19   65.09    2320       0      65
Permanent Ineff=
       F       F
Bank Sta=1755.55,1780.63
XS Rating Curve= 0
Exp/Cntr=.3,.1

Type RM Length L Ch R = 1 ,29953   ,759.23,564.75,348
BEGIN DESCRIPTION:
29953
END DESCRIPTION:
XS GIS Cut Line= 5
 2147090.3122373  230958.6593711     2146049.618      229889.834
     2145531.958      229188.441     2145028.592      228798.364
 2144989.0700442  228767.7369693
#Sta/Elev= 30
       0   62.12   35.21   60.73   71.06   63.38  151.77   62.35  265.38   65.21
  325.39      65  373.38   61.65  442.32   60.96  515.72   64.78  561.27   61.09
  731.63   61.44  759.96   59.74  922.21   62.44 1266.85   58.17 1305.61   59.74
 1312.15    61.9 1506.87   59.92 1596.14   57.22 1808.87   57.22 1851.36   55.35
 1868.83    57.3 1903.41   56.63 1918.02    52.6 1930.87   57.27  2059.8   57.67
 2143.93   55.28 2474.76   60.59 2649.34   58.92 2993.04   60.62 3050.34   58.87
#Mann= 3 , 0 , 0
       0     .12       0 1903.41     .06       0 1930.87     .12       0
#XS Ineff= 2 , 0
         1493.17   61.49 2488.62           61.62
Permanent Ineff=
       F       F
Bank Sta=1903.41,1930.87
XS Rating Curve= 0
Exp/Cntr=.3,.1

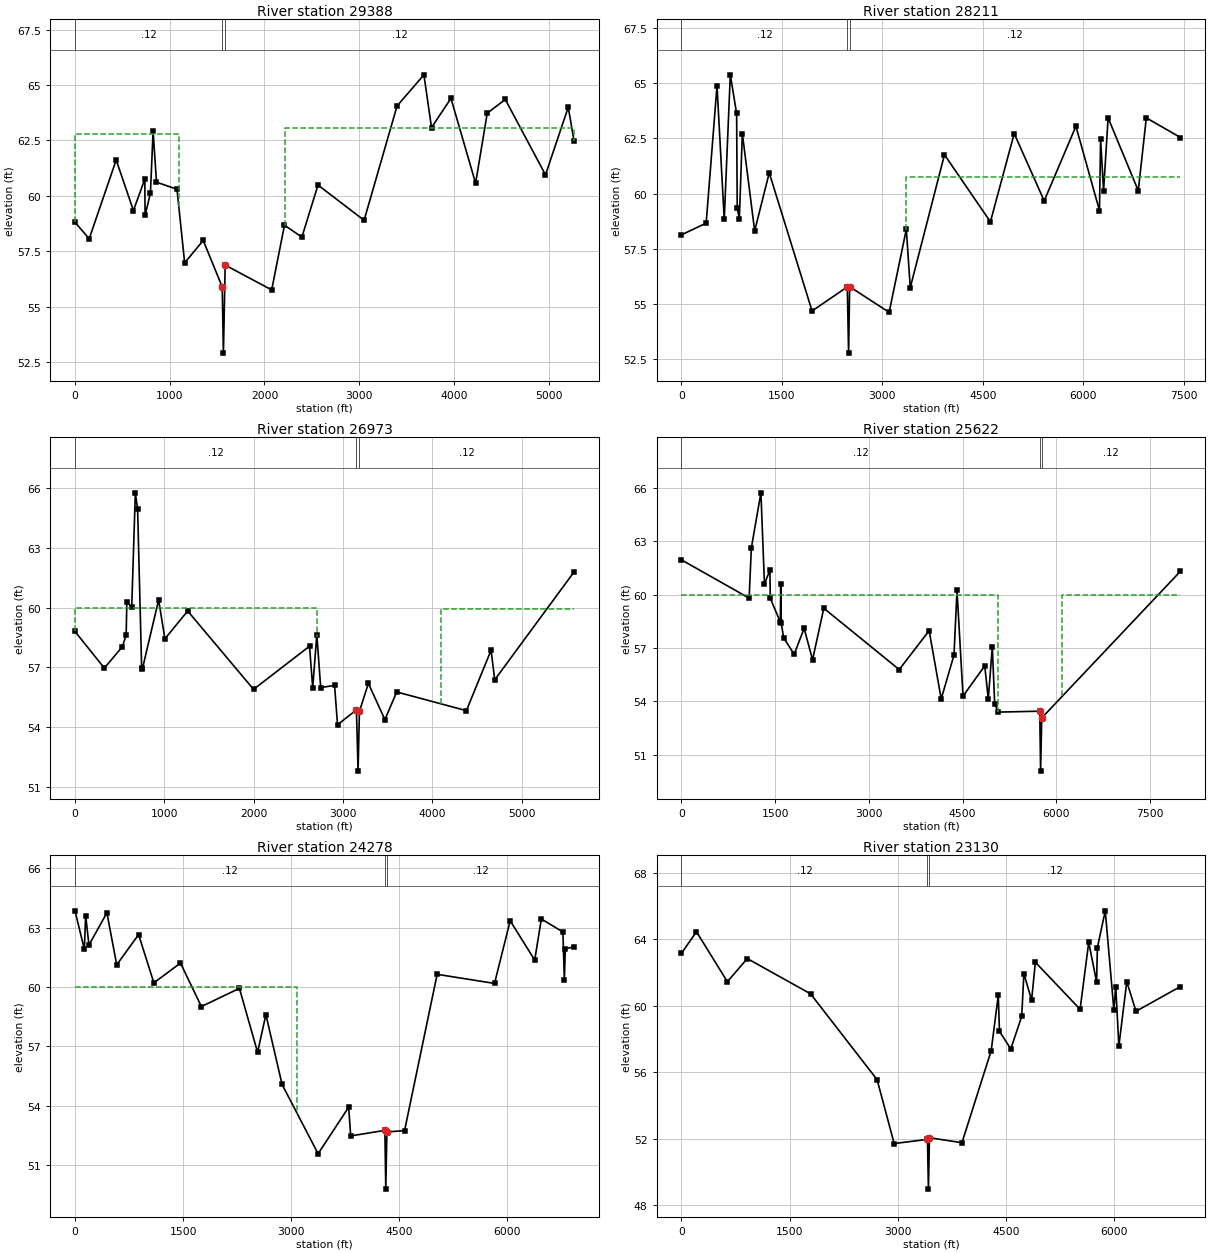
Type RM Length L Ch R = 1 ,29388   ,645.78,1176.53,1180
BEGIN DESCRIPTION:
29388
END DESCRIPTION:
XS GIS Cut Line= 5
     2147521.376      230111.469     2145410.185      228679.304
     2144693.111       228831.41     2143815.462       229342.14
     2142864.717      229525.816
#Sta/Elev= 30
       0   58.81  150.09   58.07  434.97   61.62  617.01   59.34  737.43   60.76
  739.82   59.12  796.47   60.13  824.57   62.92  860.36   60.62 1076.95    60.3
  1157.7   56.98  1353.7   57.99 1554.03    55.9 1566.95   52.91 1585.64   56.88
 2076.48   55.76 2211.55   58.68 2395.24   58.14 2565.32   60.49 3051.96    58.9
 3400.43   64.06 3683.65   65.46 3763.69   63.08 3969.02    64.4 4229.18   60.57
 4351.89   63.73 4542.32   64.35 4966.99   60.95 5207.27      64 5267.91   62.49
#Mann= 3 , 0 , 0
       0     .12       0 1554.03     .06       0 1585.64     .12       0
#XS Ineff= 2 , 0
       0 1098.98   62.79 2218.43       0   63.05
Permanent Ineff=
       F       F
Bank Sta=1554.03,1585.64
XS Rating Curve= 0
Exp/Cntr=.3,.1

Type RM Length L Ch R = 1 ,28211   ,671.34,1238.52,1250
BEGIN DESCRIPTION:
28211
END DESCRIPTION:
XS GIS Cut Line= 6
 2147793.6931048  230462.7214706     2147148.545      228577.899
     2144874.191      227324.832     2143524.038       228636.63
 2143222.9726636  228677.7260357 2142552.4311034  228769.2563388
#Sta/Elev= 30
       0   58.13     369   58.66  530.84   64.88  638.91   58.83  729.47   65.38
  823.63   63.63  832.91   59.33  864.57   58.87   909.1   62.72 1093.23   58.31
 1310.89   60.94 1950.52   54.68 2476.61   55.77 2495.95   52.77  2511.7   55.78
 3101.35   54.62 3358.06   58.38 3416.87   55.74  3927.8   61.76 4613.81   58.72
 4969.17   62.72 5416.84   59.67 5890.81   63.05  6242.5   59.23 6259.22   62.46
 6303.67   60.13 6371.48   63.43 6821.84   60.13 6942.06   63.43 7451.98   62.54
#Mann= 3 , 0 , 0
       0     .12       0 2476.61     .06       0  2511.7     .12       0
#XS Ineff= 2 , 0
                         3357.06           60.75
Permanent Ineff=
       F       F
Bank Sta=2476.61,2511.7
XS Rating Curve= 0
Exp/Cntr=.3,.1

Type RM Length L Ch R = 1 ,26973   ,805.11,1350.51,1360
BEGIN DESCRIPTION:
26973
END DESCRIPTION:
XS GIS Cut Line= 6
 2147867.0192422  229926.1106855     2147931.019      229686.112
     2147709.564      227633.968     2146410.365      226962.223
     2144823.276      226740.769  2144615.290967  226711.7478692
#Sta/Elev= 30
       0   58.81  328.64   56.97  531.65   58.05  573.07   58.64  580.42   60.28
  635.37   60.05  675.79   65.78  701.22   64.95  746.34   56.98  755.33   56.94
   936.4    60.4 1006.64   58.44 1261.92   59.84 1999.43    55.9 2626.11   58.07
  2661.9   55.98 2707.72   58.65 2751.26   55.99 2906.54    56.1 2939.54   54.12
 3151.35   54.87 3169.68   51.79 3184.87   54.79    3285    56.2 3470.17   54.38
 3602.23   55.77  4382.6   54.83 4659.07   57.87 4699.89   56.38  5587.5    61.8
#Mann= 3 , 0 , 0
       0     .12       0 3151.35     .06       0 3184.87     .12       0
#XS Ineff= 2 , 0
       0  2709.9   60.01 4102.39       0   59.95
Permanent Ineff=
       F       F
Bank Sta=3151.35,3184.87
XS Rating Curve= 0
Exp/Cntr=.3,.1

Type RM Length L Ch R = 1 ,25622   ,1935.51,1344.74,1185.65
BEGIN DESCRIPTION:
25622.31
END DESCRIPTION:
XS GIS Cut Line= 6
     2148051.894      231417.383      2148187.88      229606.184
     2148360.734      227660.905     2148286.526      226943.561
     2145955.175      224758.836     2145736.271      224553.699
#Sta/Elev= 30
       0   61.96 1082.92   59.81 1118.33   62.63 1271.58   65.73 1328.06   60.62
 1415.39   61.37 1421.37    59.8  1582.8   58.46 1588.21   60.59 1597.61    58.4
 1634.91   57.58 1803.67   56.65 1962.97   58.11 2097.92   56.34 2277.85   59.24
 3484.53   55.79 3963.65   57.98 4156.57   54.14 4361.07    56.6 4409.39   60.24
 4505.79    54.3 4853.51      56  4910.1   54.13 4974.13   57.07 5012.76   53.86
 5069.58    53.4 5733.54   53.45 5747.15   50.08 5765.49   53.07 7985.44   61.32
#Mann= 3 , 0 , 0
       0     .12       0 5733.54     .06       0 5765.49     .12       0
#XS Ineff= 2 , 0
       0    5068      60    6094       0      60
Permanent Ineff=
       F       F
Bank Sta=5733.54,5765.49
XS Rating Curve= 0
Exp/Cntr=.3,.1

Type RM Length L Ch R = 1 ,24278   ,1191.32,1147.38,1045.55
BEGIN DESCRIPTION:
24277.57
END DESCRIPTION:
XS GIS Cut Line= 6
     2151384.082      228556.497     2150000.973      227111.681
     2148869.301      225920.892     2146705.161      223806.694
     2146526.333      223631.993     2146519.179      223625.005
#Sta/Elev= 30
       0   63.85  129.76   61.91   148.4   63.61  193.55   62.12  442.99   63.75
  579.53   61.12  883.11   62.65  1095.1   60.21 1464.87   61.21 1754.78   59.01
 2282.77   59.93 2535.08    56.7 2650.52    58.6 2875.25   55.07 3375.34   51.57
 3799.73   53.92 3828.07   52.47 4302.49   52.75 4315.05   49.78 4330.21   52.67
 4575.92   52.74 5028.19   60.64  5824.7   60.18 6042.43   63.35 6382.82   61.36
 6474.88   63.44 6774.51   62.78 6794.15   60.35 6807.76   61.93 6928.33   62.03
#Mann= 3 , 0 , 0
       0     .12       0 4302.49     .06       0 4330.21     .12       0
#XS Ineff= 2 , 0
         3087.92   59.98
Permanent Ineff=
       F       F
Bank Sta=4302.49,4330.21
XS Rating Curve= 0
Exp/Cntr=.3,.1

Type RM Length L Ch R = 1 ,23130   ,593.92,451.26,323.48
BEGIN DESCRIPTION:
23130
END DESCRIPTION:
XS GIS Cut Line= 6
 2151760.0649253  227095.8353379     2150789.641      226250.967
     2149995.897       225400.84      2147880.78      223599.177
     2147174.598      222512.927 2146832.7975314   222303.570127
#Sta/Elev= 30
       0   63.15  208.54   64.44  637.18   61.44  913.45   62.83 1791.63   60.71
 2714.88   55.55 2951.85   51.71 3413.84   51.96 3427.05   48.97 3441.54   52.06
 3892.33   51.76 4298.11   57.29 4396.15   60.62 4413.24   58.45 4570.19    57.4
 4721.57   59.35 4751.97   61.93 4859.03   60.33  4911.1   62.61 5531.85   59.78
 5651.54   63.81 5760.68   61.42 5771.76   63.49 5880.91    65.7 6000.76   59.74
 6026.59   61.15 6069.69   57.57 6179.79   61.44 6307.52   59.66 6924.62   61.15
#Mann= 3 , 0 , 0
       0     .12       0 3413.84     .06       0 3441.54     .12       0
Bank Sta=3413.84,3441.54
XS Rating Curve= 0
Exp/Cntr=.3,.1

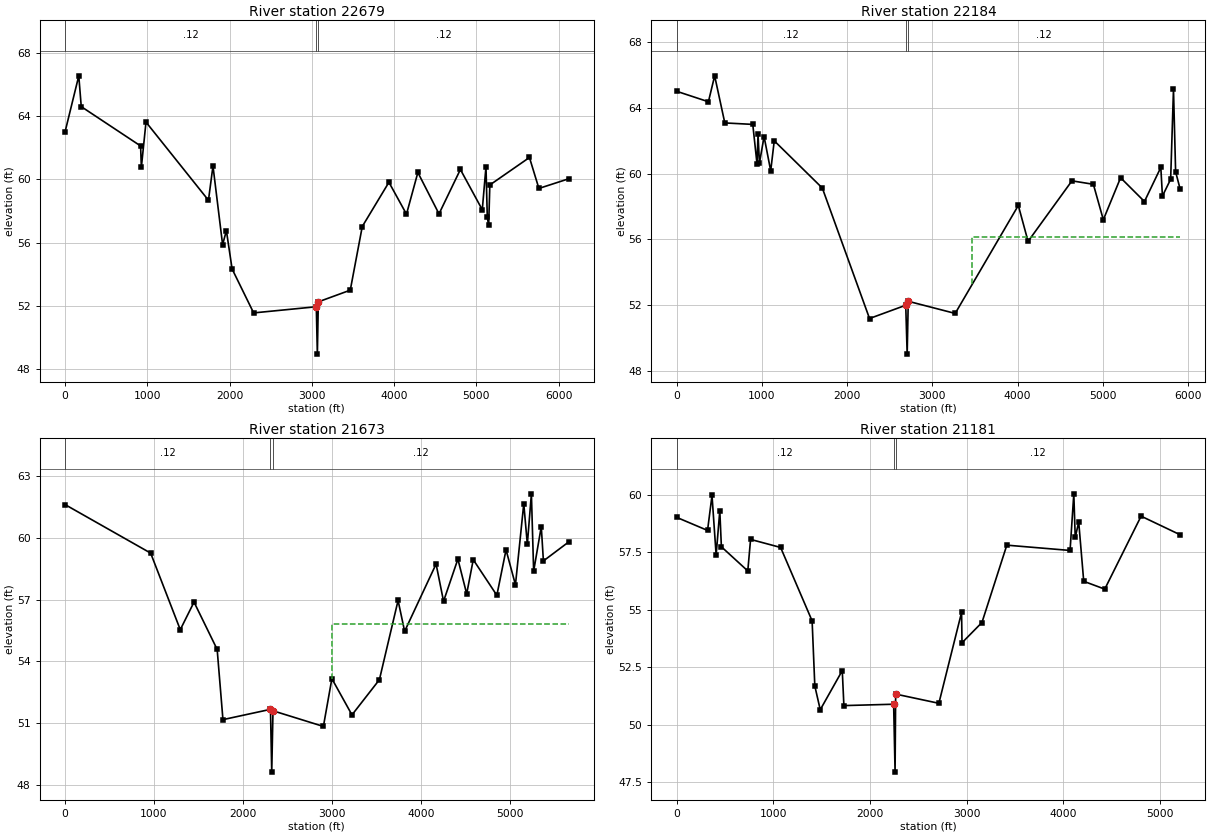
Type RM Length L Ch R = 1 ,22679   ,500,494.38,396.24
BEGIN DESCRIPTION:
22679
END DESCRIPTION:
XS GIS Cut Line= 4
     2151772.046       226340.06     2151068.458      225476.698
     2148495.503      223758.827     2147239.385      222315.848
#Sta/Elev= 30
       0   62.99  167.76   66.56  197.79   64.61  919.06   62.12  928.09   60.76
  984.56   63.63 1743.63   58.68 1798.55   60.85 1915.54   55.87 1961.46   56.76
 2031.08   54.33 2292.61   51.55 3054.18   51.94 3066.94   48.94 3078.66   52.25
 3467.01   52.99 3612.72   57.02 3936.64   59.82 4150.08    57.8  4288.3   60.44
 4545.18   57.82  4805.1   60.63 5071.15   58.08 5116.14   60.81  5132.1    57.6
 5148.93   57.12 5162.95   59.65 5644.36   61.39 5759.05   59.43  6120.6   60.04
#Mann= 3 , 0 , 0
       0     .12       0 3054.18     .06       0 3078.66     .12       0
Bank Sta=3054.18,3078.66
XS Rating Curve= 0
Exp/Cntr=.3,.1

Type RM Length L Ch R = 1 ,22184   ,526.66,511.35,292.3
BEGIN DESCRIPTION:
22184
END DESCRIPTION:
XS GIS Cut Line= 3
     2152253.477      225637.814      2149490.64      224049.355
     2147447.008      222253.561
#Sta/Elev= 30
       0   65.02   373.6   64.38  446.63   65.96  565.72   63.09   893.9      63
  943.82   60.58  955.42    62.4   971.9   60.64 1026.46   62.26 1104.17   60.17
 1145.71      62 1709.66   59.12 2263.23   51.17 2687.89   51.98 2704.69      49
 2717.43   52.22 3267.94   51.48 4008.36   58.06 4122.79   55.87 4637.26   59.56
 4888.58   59.35 5005.44   57.19 5207.89   59.75 5487.72    58.3 5679.83   60.38
 5698.62   58.63 5795.11   59.66 5828.29   65.14 5853.33   60.11 5907.45   59.04
#Mann= 3 , 0 , 0
       0     .12       0 2687.89     .06       0 2717.43     .12       0
#XS Ineff= 2 , 0
       0                 3467.58       0   56.12
Permanent Ineff=
       F       F
Bank Sta=2687.89,2717.43
XS Rating Curve= 0
Exp/Cntr=.3,.1

Type RM Length L Ch R = 1 ,21673   ,299.54,492.49,500
BEGIN DESCRIPTION:
21673
END DESCRIPTION:
XS GIS Cut Line= 5
     2152222.333      225035.707     2150823.527      224213.641
     2149500.214      223559.573     2148661.602      223104.815
     2147498.914      221994.033
#Sta/Elev= 30
       0   61.62  962.91   59.26 1295.81   55.54 1450.37   56.88 1710.46   54.58
 1775.42   51.17 2309.53   51.67 2323.71   48.62 2337.83    51.6 2904.32   50.84
 2999.66   53.16 3225.52    51.4 3533.78   53.11 3743.69   56.96 3817.34   55.46
 4170.81   58.73 4254.71   56.92  4415.9   58.97 4514.71   57.28 4588.53   58.94
 4853.81   57.21 4956.96   59.42 5062.82   57.72 5156.31   61.66 5196.28   59.69
 5242.03   62.14 5267.26   58.38 5353.02   60.55 5376.96   58.88  5660.6    59.8
#Mann= 3 , 0 , 0
       0     .12       0 2309.53     .06       0 2337.83     .12       0
#XS Ineff= 2 , 0
       0                 3003.41       0   55.83
Permanent Ineff=
       F       F
Bank Sta=2309.53,2337.83
XS Rating Curve= 0
Exp/Cntr=.3,.1

Type RM Length L Ch R = 1 ,21181   ,530,523.58,402.45
BEGIN DESCRIPTION:
21181
END DESCRIPTION:
XS GIS Cut Line= 3
     2152076.997      224630.843     2148920.614      222676.838
     2147714.491      221792.747
#Sta/Elev= 30
       0   59.02  320.24   58.45  366.43   59.97  409.18   57.38  447.03   59.31
  463.38   57.74  736.38   56.69  765.23   58.06 1075.77   57.71 1401.54   54.52
  1429.5   51.69 1485.59   50.66  1713.3   52.36 1730.08   50.84 2244.53    50.9
 2259.29   47.95 2265.35   51.34 2712.04   50.94 2946.93   54.89 2951.25   53.57
 3157.52   54.45 3414.68   57.81 4068.65   57.58 4107.39   60.04 4121.92   58.15
 4158.17   58.81 4209.83   56.24 4427.21    55.9 4803.08   59.07 5207.71   58.26
#Mann= 3 , 0 , 0
       0     .12       0 2244.53     .06       0 2265.35     .12       0
Bank Sta=2244.53,2265.35
XS Rating Curve= 0
Exp/Cntr=.3,.1