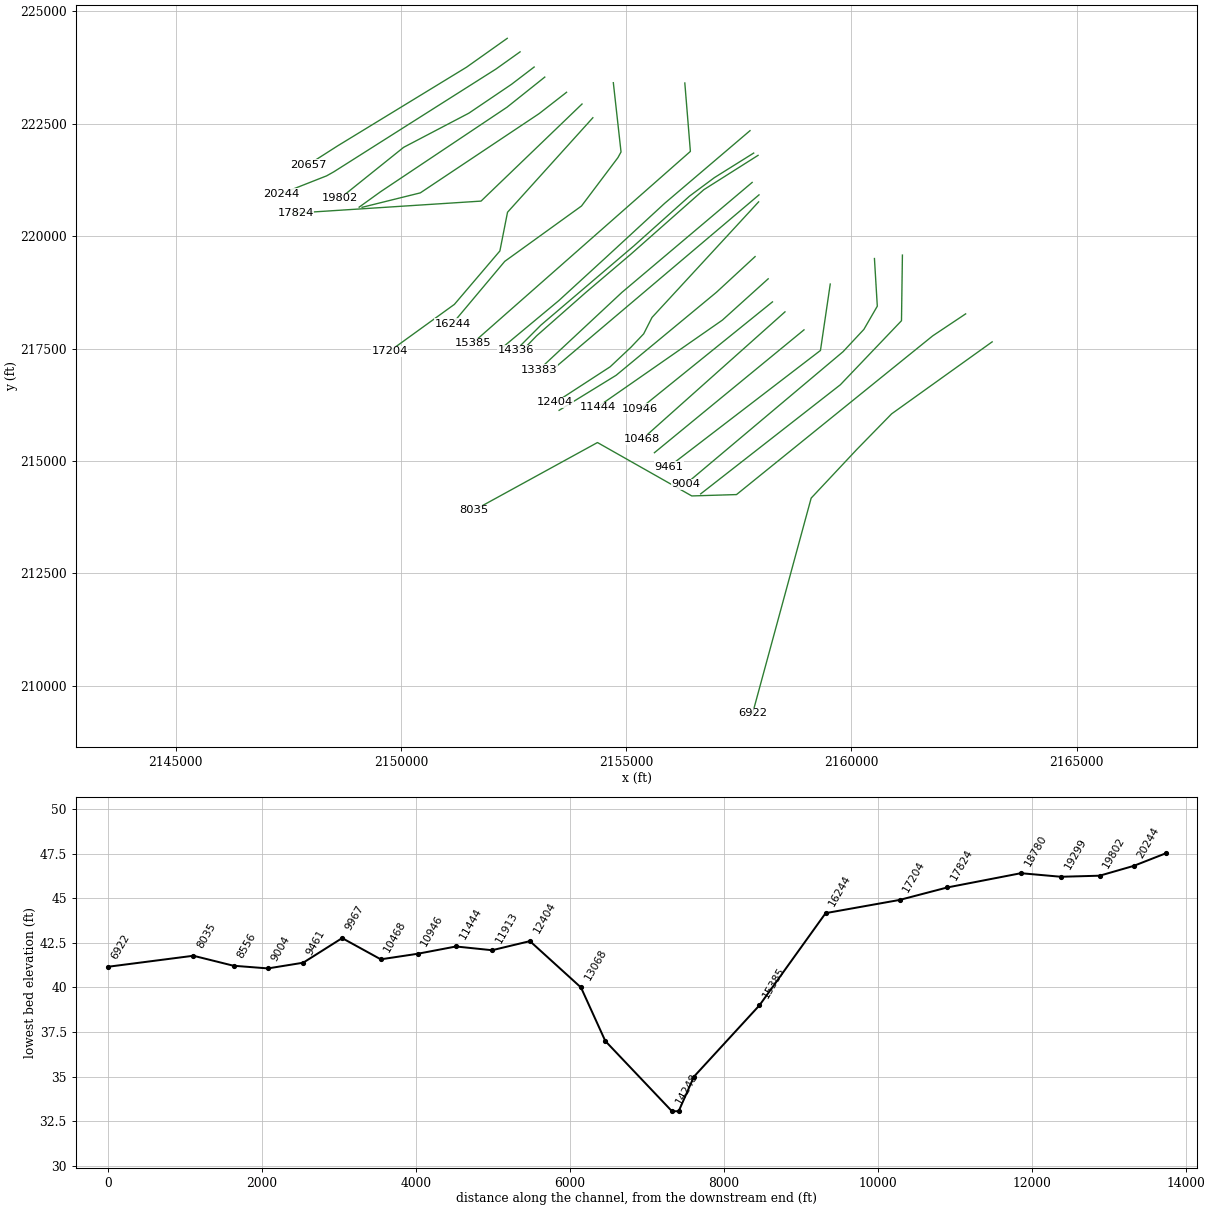
HEC-RAS study slapswamp.prj: Slap Swamp

--- slapswamp.g01 (geometry) --- (continued)

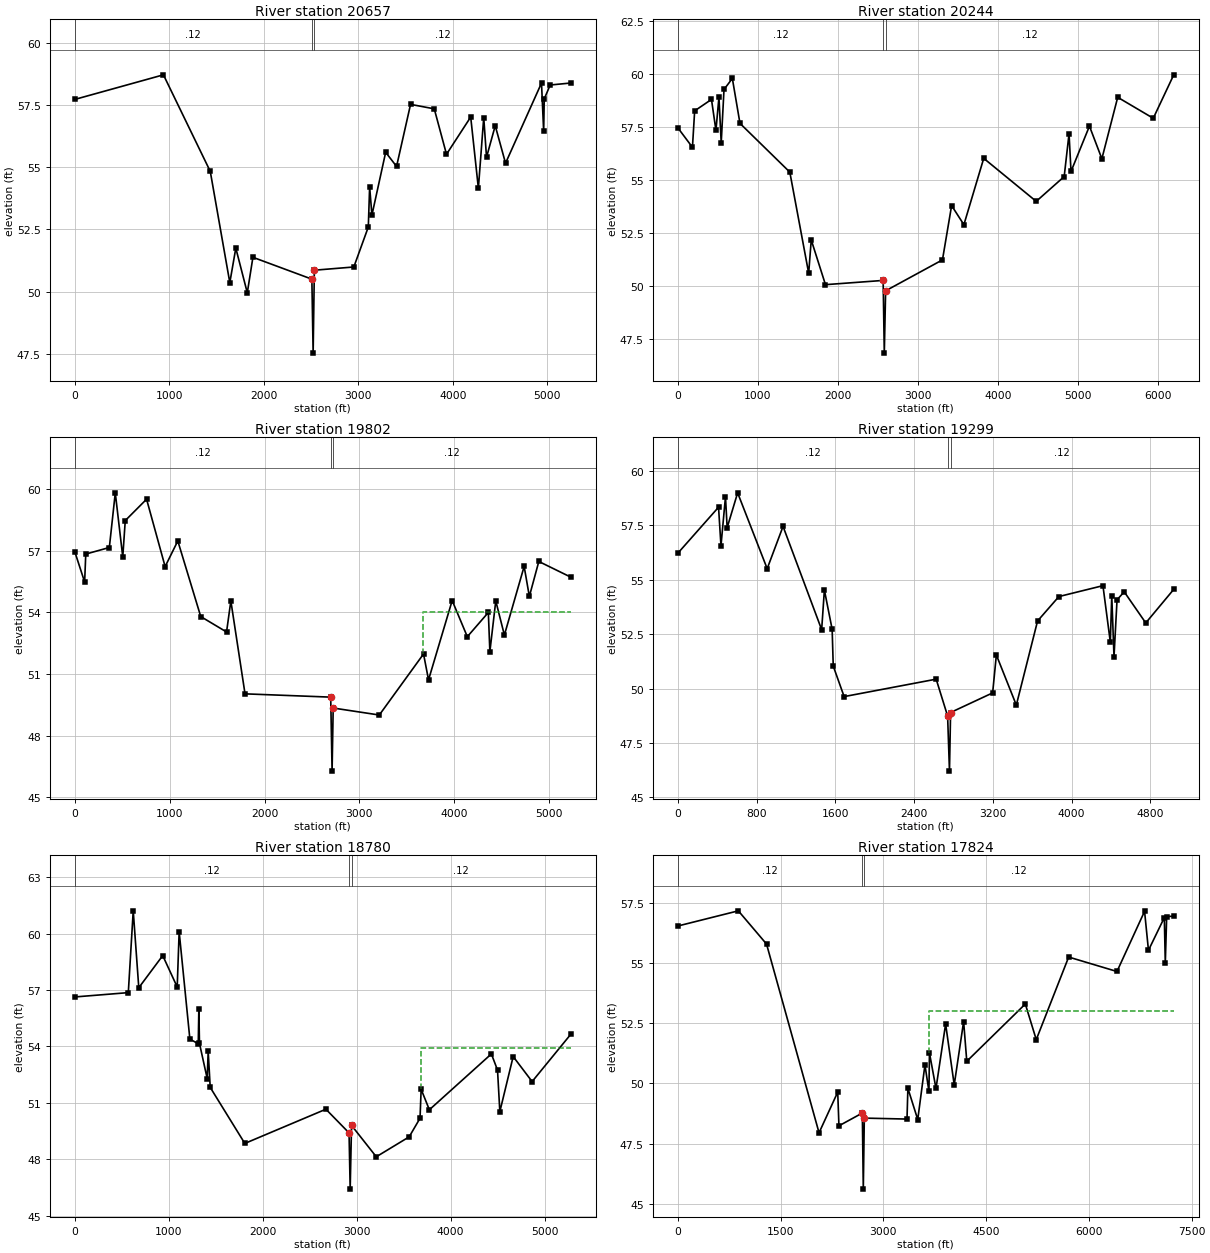
Type RM Length L Ch R = 1 ,20657   ,397.97,413.41,421.3
BEGIN DESCRIPTION:
20657
END DESCRIPTION:
XS GIS Cut Line= 4
     2152357.896      224399.625     2151452.274      223756.538
     2148594.816      222009.729     2147931.473      221585.065
#Sta/Elev= 30
       0   57.74  937.53   58.73 1433.17   54.84 1640.02   50.36 1703.49   51.75
 1824.96   49.95 1884.43   51.38 2508.28    50.5  2521.8   47.52 2534.52   50.86
 2952.42   50.99 3105.58    52.6 3119.63   54.22 3143.79   53.08 3289.29   55.61
 3404.56   55.04 3552.58   57.54 3803.53   57.36 3932.96   55.53 4189.16   57.03
 4270.34   54.16 4327.05   57.01 4356.55   55.41 4448.72   56.68 4557.86   55.17
 4938.42    58.4 4961.25   56.45 4967.19   57.76  5030.5   58.32 5247.44    58.4
#Mann= 3 , 0 , 0
       0     .12       0 2508.28     .06       0 2534.52     .12       0
Bank Sta=2508.28,2534.52
XS Rating Curve= 0
Exp/Cntr=.3,.1

Type RM Length L Ch R = 1 ,20244   ,486.36,441.64,375.2
BEGIN DESCRIPTION:
20244
END DESCRIPTION:
XS GIS Cut Line= 5
     2152643.072      224098.951     2152108.233      223717.237
     2148507.292      221431.198     2148347.638      221341.304
     2147335.186      220942.191
#Sta/Elev= 30
       0   57.45  182.24   56.53  209.86   58.25  420.01   58.79  475.61   57.33
  513.24   58.89  541.52   56.74  576.45   59.26  680.69   59.78  775.88   57.66
 1398.49   55.36 1634.12   50.59 1666.17   52.16 1843.82   50.05 2564.27   50.25
 2578.55   46.82 2595.24   49.76 3305.19   51.22 3419.41   53.78 3572.85   52.88
 3820.64   56.01 4476.32   53.98 4825.55   55.15  4886.2   57.17 4910.93   55.39
 5141.04   57.53 5296.29   55.99 5494.15   58.89 5938.27    57.9 6193.88   59.95
#Mann= 3 , 0 , 0
       0     .12       0 2564.27     .06       0 2595.24     .12       0
Bank Sta=2564.27,2595.24
XS Rating Curve= 0
Exp/Cntr=.3,.1

Type RM Length L Ch R = 1 ,19802   ,362.08,503.51,533.08
BEGIN DESCRIPTION:
19802
END DESCRIPTION:
XS GIS Cut Line= 6
 2152955.3688177  223761.5775167 2152947.4255221  223755.5026459
     2152450.492      223375.458     2151505.469      222735.067
     2150057.892      221975.631 2148642.4259791  220838.0786926
#Sta/Elev= 30
       0   56.94  103.29   55.47  115.23   56.83  363.75   57.15  426.34   59.81
   505.3   56.69  531.63   58.46  756.39    59.5  951.96   56.22 1085.58   57.47
 1327.41   53.79 1599.47   53.04 1644.83   54.55 1794.23   50.03 2697.53   49.87
 2712.07   46.27 2723.67   49.34 3209.89      49 3676.23   51.97 3728.85   50.71
 3978.16   54.57 4137.77   52.81 4359.46   53.99 4375.48   52.08 4437.68   54.55
  4528.6   52.89  4736.9   56.23 4791.74   54.77 4891.52   56.47 5227.78   55.71
#Mann= 3 , 0 , 0
       0     .12       0 2697.53     .06       0 2723.67     .12       0
#XS Ineff= 2 , 0
       0                 3672.35       0   53.99
Permanent Ineff=
       F       F
Bank Sta=2697.53,2723.67
XS Rating Curve= 0
Exp/Cntr=.3,.1

Type RM Length L Ch R = 1 ,19299   ,580,519,480
BEGIN DESCRIPTION:
19299
END DESCRIPTION:
XS GIS Cut Line= 6
 2153191.4708747  223537.7286781     2152351.035      222866.283
     2149543.999      220987.062     2149102.386       220668.47
 2149078.0564553  220650.9179843 2149069.9466071  220645.0673124
#Sta/Elev= 30
       0   56.21  413.41   58.32  438.06   56.55  483.94    58.8  500.84   57.38
  607.34   58.98  907.57    55.5 1068.85   57.44 1461.12    52.7 1488.75   54.52
 1567.65   52.72 1578.84   51.03 1689.34   49.63 2624.57   50.43 2740.82   48.74
 2759.73   46.21 2771.05    48.9 3198.34    49.8 3236.11   51.54 3438.96   49.24
 3654.79    53.1 3871.35   54.22 4319.06   54.72 4394.09   52.13 4408.56   54.26
 4431.41   51.46  4462.3   54.07 4534.94   54.44 4753.96   53.01 5038.27   54.55
#Mann= 3 , 0 , 0
       0     .12       0 2740.82     .06       0 2771.05     .12       0
Bank Sta=2740.82,2771.05
XS Rating Curve= 0
Exp/Cntr=.3,.1

Type RM Length L Ch R = 1 ,18780   ,1000,956.25,437.36
BEGIN DESCRIPTION:
18780
END DESCRIPTION:
XS GIS Cut Line= 4
     2153675.284      223200.027     2153066.789      222725.645
     2150428.291      220962.806     2149134.675      220641.509
#Sta/Elev= 30
       0   56.63  569.12   56.86  621.45   61.21  680.65   57.12  935.49   58.83
 1089.58   57.16 1110.29    60.1  1224.3   54.39 1313.52   54.14 1319.81   55.97
 1326.57   54.16 1408.77   52.29 1419.27   53.74 1440.87   51.82 1809.15   48.84
 2672.11   50.66 2918.56    49.4 2930.53   46.41 2944.95    49.8  3208.3   48.13
 3558.34   49.19 3673.95   50.18 3685.81   51.72  3773.3   50.63 4433.36    53.6
 4498.77   52.74 4523.35   50.53 4665.36   53.46  4866.9   52.13 5277.69   54.64
#Mann= 3 , 0 , 0
       0     .12       0 2918.56     .06       0 2944.95     .12       0
#XS Ineff= 2 , 0
       0                 3686.01       0   53.91
Permanent Ineff=
       F       F
Bank Sta=2918.56,2944.95
XS Rating Curve= 0
Exp/Cntr=.3,.1

Type RM Length L Ch R = 1 ,17824   ,476.11,619.8,1724.4
BEGIN DESCRIPTION:
17824
END DESCRIPTION:
XS GIS Cut Line= 3
     2154018.271      222938.717     2151775.944      220779.439
     2147659.198      220512.776
#Sta/Elev= 30
       0   56.54  882.73   57.17 1294.46   55.79 2060.97   47.95 2333.62   49.64
 2351.35   48.24 2692.66   48.77 2706.99   45.61 2721.61   48.56 3344.88   48.52
 3357.66    49.8 3501.73    48.5 3606.77   50.77  3665.2   49.67 3672.51   51.27
 3767.83   49.79  3908.6   52.47 4034.17   49.94 4171.45   52.57 4217.33   50.92
 5072.04    53.3 5231.63   51.82 5704.64   55.25  6409.7   54.65 6812.69   57.15
  6869.5   55.53    7101   56.89 7115.23   54.99  7135.4   56.93 7238.33   56.95
#Mann= 3 , 0 , 0
       0     .12       0 2692.66     .06       0 2721.61     .12       0
#XS Ineff= 2 , 0
       0                 3673.15       0   52.99
Permanent Ineff=
       F       F
Bank Sta=2692.66,2721.61
XS Rating Curve= 0
Exp/Cntr=.3,.1

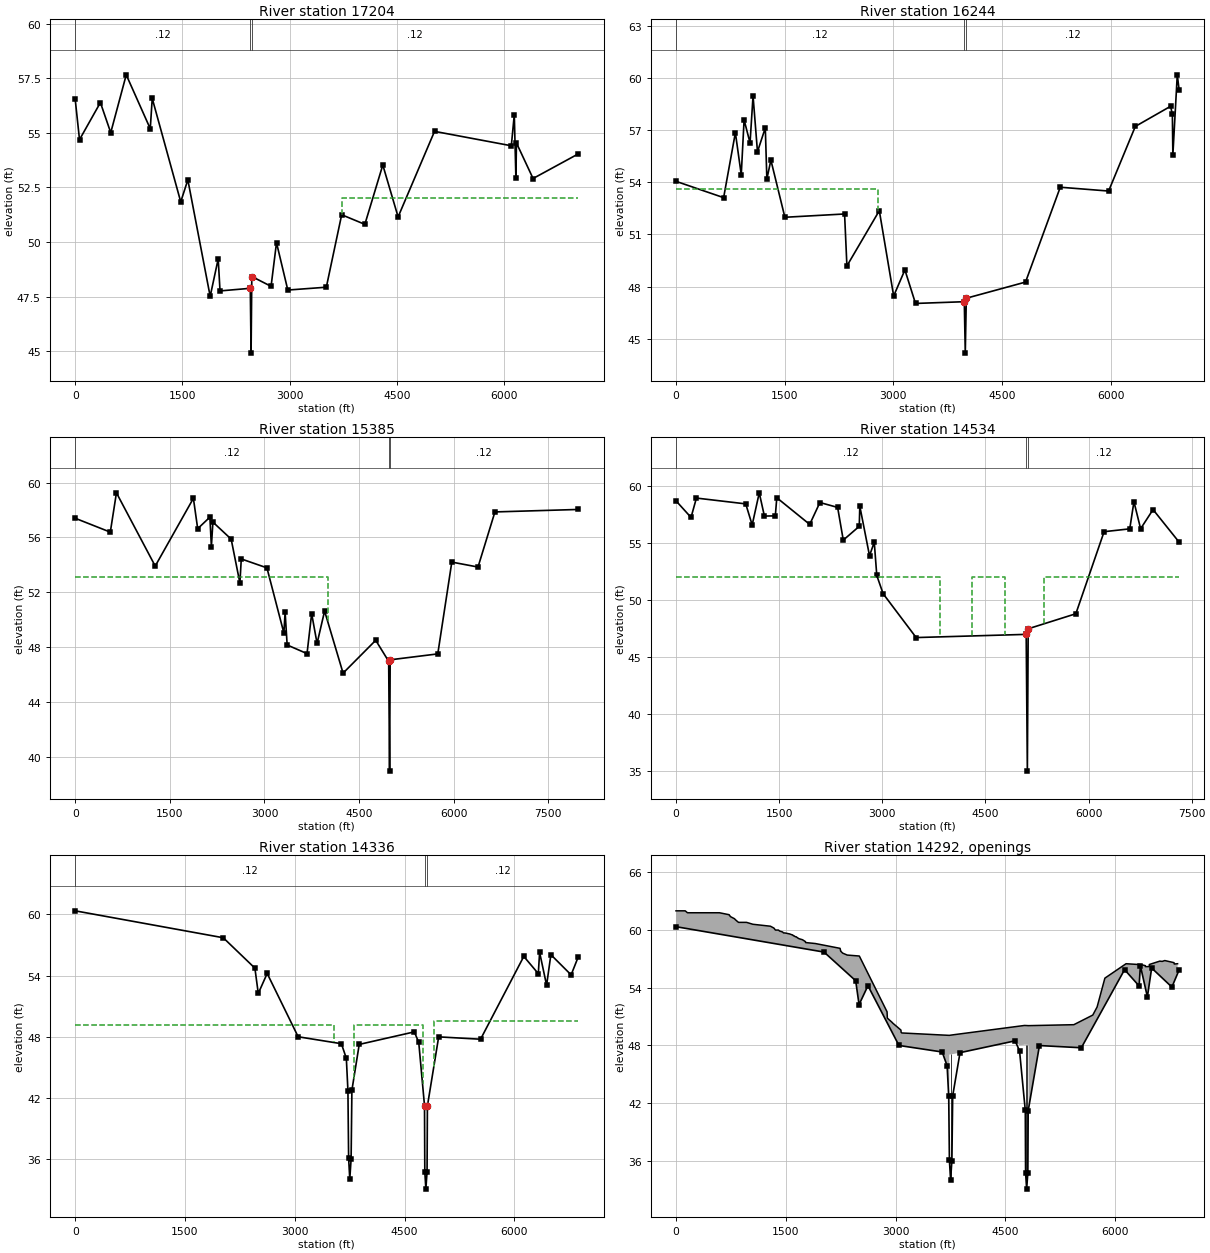
Type RM Length L Ch R = 1 ,17204   ,1095.03,959.74,233.66
BEGIN DESCRIPTION:
17204
END DESCRIPTION:
XS GIS Cut Line= 5
     2154259.135      222633.564     2152364.084      220531.513
     2152194.556      219671.061     2151184.498      218482.758
     2149748.631      217442.993
#Sta/Elev= 30
       0   56.54   60.36   54.69   352.5   56.39  497.18   55.01  714.02   57.66
 1050.26   55.19 1077.76   56.58 1476.47   51.84 1575.97   52.85 1888.44   47.51
 2000.71   49.23 2026.17   47.76 2449.76   47.88 2460.72   44.91 2470.88   48.42
 2740.39   47.97 2816.39   49.97 2974.54    47.8 3513.43   47.93 3728.08   51.25
 4052.41   50.81 4303.49   53.53  4517.6   51.15 5027.22   55.07 6101.65   54.41
 6143.16   55.84 6165.64   52.92 6173.28   54.54  6405.9   52.91 7039.54   54.04
#Mann= 3 , 0 , 0
       0     .12       0 2449.76     .06       0 2470.88     .12       0
#XS Ineff= 2 , 0
       0                 3731.51       0   52.02
Permanent Ineff=
       F       F
Bank Sta=2449.76,2470.88
XS Rating Curve= 0
Exp/Cntr=.3,.1

Type RM Length L Ch R = 1 ,16244   ,900,859,820
BEGIN DESCRIPTION:
16244
END DESCRIPTION:
XS GIS Cut Line= 6
     2154713.613      223412.882     2154884.732      221872.811
     2154815.758      221746.688     2154007.048      220670.688
     2152302.272       219438.88     2151144.888      218056.949
#Sta/Elev= 30
       0   54.06  657.69   53.12  819.79   56.86  900.83   54.44  940.12    57.6
 1022.22   56.27 1063.68   58.98  1124.8   55.76 1232.86   57.14 1254.39   54.19
 1310.08   55.28 1503.07   51.99 2327.15   52.18  2359.4   49.19 2806.57   52.37
 3004.68   47.46 3159.74   48.96 3306.16   47.03 3979.66   47.13 3993.19   44.17
 4007.44   47.33 4824.97   48.26 5304.32   53.72 5971.63    53.5 6340.47   57.22
 6827.27   58.38 6851.68   57.92 6858.59   55.58 6919.42   60.19  6945.3   59.31
#Mann= 3 , 0 , 0
       0     .12       0 3979.66     .06       0 4007.44     .12       0
#XS Ineff= 2 , 0
         2795.22   53.62
Permanent Ineff=
       F       F
Bank Sta=3979.66,4007.44
XS Rating Curve= 0
Exp/Cntr=.3,.1

Type RM Length L Ch R = 1 ,15385   ,512.62,850.57,860
BEGIN DESCRIPTION:
15385
END DESCRIPTION:
XS GIS Cut Line= 3
     2156300.985      223406.316     2156424.665      221885.053
      2151588.78      217618.095
#Sta/Elev= 30
       0    57.4  556.47   56.39  653.63   59.25 1268.38   53.92 1873.51   58.85
 1941.68   56.64 2134.99   57.48 2158.63   55.34 2182.62   57.12  2472.2   55.88
 2610.63   52.69 2632.52   54.44 3039.17   53.79 3307.63   49.05 3327.33   50.57
 3359.61   48.18 3674.63   47.55 3748.07   50.46 3833.86   48.29 3952.97   50.65
 4246.02   46.13 4763.44   48.52 4968.75   46.99 4983.35      39 4992.68    47.1
 5747.19   47.53 5969.48   54.21 6384.86   53.85 6652.92   57.86 7975.52   58.04
#Mann= 3 , 0 , 0
       0     .12       0 4968.75     .06       0 4992.68     .12       0
#XS Ineff= 2 , 0
       0 4004.55   53.14               0
Permanent Ineff=
       F       F
Bank Sta=4968.75,4992.68
XS Rating Curve= 0
Exp/Cntr=.3,.1

Type RM Length L Ch R = 1 ,14534   ,235.53,198.46,169.49
BEGIN DESCRIPTION:
14534
END DESCRIPTION:
XS GIS Cut Line= 5
      2157748.37      222345.717     2155854.114      220730.712
     2154573.352      219548.547     2153505.238      218568.448
     2152248.217      217520.553
#Sta/Elev= 30
       0   58.72  218.91   57.26  297.01   58.96  1014.5   58.45 1108.22    56.6
 1211.11   59.42 1286.04   57.38 1444.78    57.4 1466.23   58.99 1944.92   56.65
 2093.18   58.57 2351.06   58.14 2433.24   55.27 2665.52   56.48 2673.65   58.25
  2814.9    53.9 2883.92   55.09 2920.63   52.17 3012.46   50.57 3493.35   46.72
 5093.59      47 5110.62      35 5122.86   47.49 5815.91   48.81 6226.82   56.01
 6599.87   56.26 6660.83   58.64 6757.97   56.27 6938.79   57.95 7318.37   55.09
#Mann= 3 , 0 , 0
       0     .12       0 5093.59     .06       0 5122.86     .12       0
#XS Ineff= 3 ,-1
       0    3835      52    4300    4791      52 5359.09 7509.08      52
Permanent Ineff=
       F       F       F
Bank Sta=5093.59,5122.86
XS Rating Curve= 0
Exp/Cntr=.5,.3

Type RM Length L Ch R = 1 ,14336   ,80,87.11,114.57
BEGIN DESCRIPTION:
14336
END DESCRIPTION:
XS GIS Cut Line= 6
     2157830.243      221848.131     2156958.578      221302.128
     2156405.646      220890.547     2155168.132      219781.912
     2153104.683      218020.566     2152553.137      217466.249
#Sta/Elev= 30
       0   60.35 2023.05   57.71 2455.44   54.73 2501.61   52.25  2623.2   54.21
 3046.64      48 3637.33   47.32 3704.89   45.89 3726.64   42.73 3736.15   36.07
    3752   34.05 3770.12   36.01    3781   42.76 3881.06   47.25  4633.9   48.48
 4694.37   47.45 4773.13   41.24 4777.15   34.77 4791.63   33.06 4807.99   34.77
 4812.68   41.21 4966.57   47.99  5539.1   47.76  6129.7   55.88 6328.09   54.19
 6345.88   56.28 6441.37   53.05 6499.81   56.05 6776.43   54.07 6875.39   55.86
#Mann= 3 , 0 , 0
       0     .12       0 4773.13     .06       0 4812.68     .12       0
#XS Ineff= 3 ,-1
       0    3530    49.2    3806 4746.61    49.2    4900 6962.97    49.5
Permanent Ineff=
       F       F       F
Bank Sta=4773.13,4812.68
XS Rating Curve= 0
Exp/Cntr=.5,.3

Type RM Length L Ch R = 4 ,14292   ,,,
BEGIN DESCRIPTION:
SR 1740, 0.3 and 0.5 MI. W. JCT. SR 1731
END DESCRIPTION:
Bridge Culvert--1,0,-1,-1, 0
Deck Dist Width WeirC Skew NumUp NumDn MinLoCord MaxHiCord MaxSubmerge Is_Ogee
31.35,25.3,2.6,0, 90, 90, , , .95, 0, 0,0,,
       0  114.92  125.87  156.88  593.93  594.09  724.58  726.04  743.53  743.87
  794.05  794.88  796.33  822.09  822.89  854.51  964.15 1052.11 1053.96  1290.6
 1339.59 1339.76 1357.98  1400.2 1415.36  1457.1 1469.23 1488.83 1551.54 1552.32
 1587.16 1593.27 1605.66 1613.47 1632.09 1643.53 1658.87 1659.86 1660.08 1681.23
 1682.31 1726.01 1726.87 1727.34 1768.81 1769.26 1771.54  1903.7 1903.96 2241.85
 2242.29 2250.68 2251.54  2277.7 2277.84 2340.05 2505.39 2884.36 2887.27 2888.38
 2957.44 2957.89 3073.72 3076.59 3085.79  3734.5  3734.5  3769.5  3769.5    4762
 4765.63 4765.63 4817.63 4817.63 5436.28 5695.23 5754.25 5860.55    6150  6360.2
 6412.44 6414.29 6466.53 6468.14  6611.2 6643.61 6679.27 6804.99 6808.71 6854.04
      62      62      62    61.8    61.8    61.8    61.6    61.6    61.4    61.4
    61.2    61.2    61.2      61      61    60.8    60.8    60.6    60.6    60.4
    60.2    60.2      60      60    59.9    59.8    59.7    59.7    59.6    59.6
    59.5    59.5    59.4    59.4    59.3    59.3    59.2    59.2    59.2    59.1
    59.1      59      59      59    58.8    58.8    58.7    58.6    58.6    58.1
    58.1    57.8    57.8    57.6    57.6    57.4    57.3    51.5      51   50.84
   50.37   50.35    49.6   49.36    49.3   49.05   49.05   49.09   49.09   50.08
   50.08   50.08   50.06   50.06   50.16   51.16      52      55    56.5    56.4
    56.3    56.2    56.2   56.42   56.77   56.74   56.83   56.61   56.47    56.5
                                                                                
                                                                                
                                                                                
                                                                                
                                                                                
                                                                                
                                                   47.05   47.09
           48.08   48.06
                                                                                
       0  114.92  125.87  156.88  593.93  594.09  724.58  726.04  743.53  743.87
  794.05  794.88  796.33  822.09  822.89  854.51  964.15 1052.11 1053.96  1290.6
 1339.59 1339.76 1357.98  1400.2 1415.36  1457.1 1469.23 1488.83 1551.54 1552.32
 1587.16 1593.27 1605.66 1613.47 1632.09 1643.53 1658.87 1659.86 1660.08 1681.23
 1682.31 1726.01 1726.87 1727.34 1768.81 1769.26 1771.54  1903.7 1903.96 2241.85
 2242.29 2250.68 2251.54  2277.7 2277.84 2340.05 2505.39 2884.36 2887.27 2888.38
 2957.44 2957.89 3073.72 3076.59 3085.79  3734.5  3734.5  3769.5  3769.5    4762
 4799.45 4799.45 4851.45 4851.45 5436.28 5695.23 5754.25 5860.55    6150  6360.2
 6412.44 6414.29 6466.53 6468.14  6611.2 6643.61 6679.27 6804.99 6808.71 6854.04
      62      62      62    61.8    61.8    61.8    61.6    61.6    61.4    61.4
    61.2    61.2    61.2      61      61    60.8    60.8    60.6    60.6    60.4
    60.2    60.2      60      60    59.9    59.8    59.7    59.7    59.6    59.6
    59.5    59.5    59.4    59.4    59.3    59.3    59.2    59.2    59.2    59.1
    59.1      59      59      59    58.8    58.8    58.7    58.6    58.6    58.1
    58.1    57.8    57.8    57.6    57.6    57.4    57.3    51.5      51   50.84
   50.37   50.35    49.6   49.36    49.3   49.05   49.05   49.09   49.09   50.08
   50.08   50.08   50.06   50.06   50.16   51.16      52      55    56.5    56.4
    56.3    56.2    56.2   56.42   56.77   56.74   56.83   56.61   56.47    56.5
                                                                                
                                                                                
                                                                                
                                                                                
                                                                                
                                                                                
                                                   47.05   47.09
           48.08   48.06
                                                                                
Pier Skew, UpSta & Num, DnSta & Num=  ,3752.17, 2 ,3752.17, 2 , 0 , 0 , 0 ,,
       1       1
      32   47.09
       1       1
      32   47.09
Pier Skew, UpSta & Num, DnSta & Num=  ,4783.13, 2 ,4816.95, 2 , 0 , 0 , 0 ,,
       1       1
      32   48.08
       1       1
      32   48.08
Pier Skew, UpSta & Num, DnSta & Num=  ,4800.13, 2 ,4833.95, 2 , 0 , 0 , 0 ,,
       1       1
      32   48.08
       1       1
      32   48.08
BR Coef= 1 , 0 , 0 ,, 0 ,,,.8,0,,0,
WSPro=,,,, 1 ,,,, 0 ,,,, 0 ,,,,-1 ,-1 ,-1 , 0 , 0 , 0 , 0 , 0
BC Mult= 3 ,0,4400,0,4400
BC Mult= 3 ,4100,7000,4100,7000
BC Design=,, 0 ,, 0 ,,,,,,

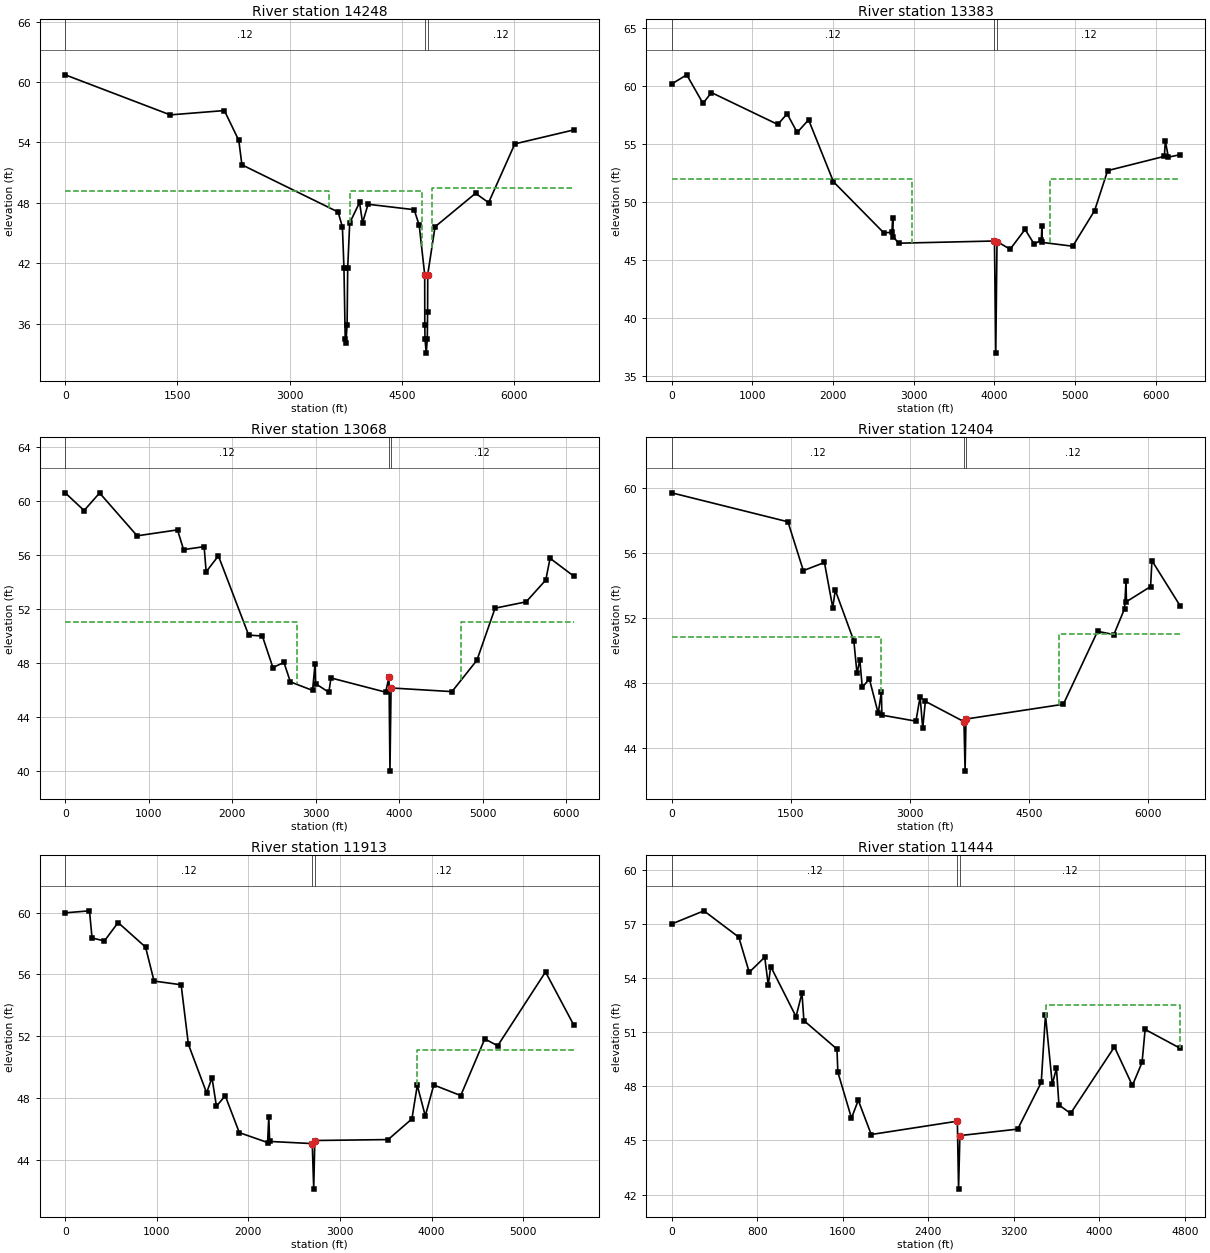
Type RM Length L Ch R = 1 ,14248   ,538.2,865.43,870
BEGIN DESCRIPTION:
14248
END DESCRIPTION:
XS GIS Cut Line= 6
     2157927.249      221796.857     2156722.993      221033.284
     2155101.613      219597.601     2154096.912      218742.566
     2153010.449      217783.596     2152708.346      217470.406
#Sta/Elev= 30
       0   60.71 1404.35   56.73 2127.64   57.16 2320.92   54.19 2362.19   51.77
 3648.24   47.08 3705.74   45.59 3726.52   41.56 3743.37   34.48    3752   34.05
 3768.65    35.9 3776.51   41.51 3803.47   45.99 3935.19   48.03 3975.07   46.02
 4049.29   47.85 4665.12   47.31 4732.63   45.76 4805.83   40.87 4807.32   35.86
 4810.29   34.44 4826.38   33.06 4840.55   34.43 4844.86   37.12 4846.71   40.87
 4944.17   45.61 5485.72   48.94 5660.34   48.01 6010.95   53.85 6795.74   55.23
#Mann= 3 , 0 , 0
       0     .12       0 4805.83     .06       0 4846.71     .12       0
#XS Ineff= 3 ,-1
       0    3530    49.2    3806    4765    49.2    4900 6931.11    49.5
Permanent Ineff=
       F       F       F
Bank Sta=4805.83,4846.71
XS Rating Curve= 0
Exp/Cntr=.5,.3

Type RM Length L Ch R = 1 ,13383   ,316.9,315.48,247.4
BEGIN DESCRIPTION:
13383
END DESCRIPTION:
XS GIS Cut Line= 4
     2157796.248      221194.923     2154902.147      218747.442
      2153133.53      217094.946     2153071.003      217032.419
#Sta/Elev= 30
       0   60.21  186.59      61  387.91   58.54  492.72   59.47 1314.93   56.72
 1430.76   57.64 1555.51   56.03 1696.78   57.12 2004.55   51.78    2629   47.37
 2728.89   47.42 2738.97   48.63 2745.16   47.03  2813.4   46.48 3999.97   46.67
  4016.2      37 4031.47   46.62  4194.5   45.96 4378.92   47.67 4491.73   46.41
 4580.71   46.74 4587.46   47.93 4589.34   46.55 4969.99   46.22 5240.92   49.29
 5402.38   52.74 6105.63   53.97 6117.64    55.3 6154.86    53.9 6299.17   54.11
#Mann= 3 , 0 , 0
       0     .12       0 3999.97     .06       0 4031.47     .12       0
#XS Ineff= 2 ,-1
       0    2984      52    4692    7000      52
Permanent Ineff=
       F       F
Bank Sta=3999.97,4031.47
XS Rating Curve= 0
Exp/Cntr=.3,.1

Type RM Length L Ch R = 1 ,13068   ,394.98,663.03,792.28
BEGIN DESCRIPTION:
13068
END DESCRIPTION:
XS GIS Cut Line= 2
     2157948.099      220918.018     2153303.246      216978.825
#Sta/Elev= 30
       0   60.58  226.21   59.27  411.93   60.57  861.81    57.4  1345.5   57.84
 1417.89   56.38 1664.24    56.6 1688.76   54.74 1835.41   55.92 2197.93   50.06
 2362.36   49.99 2488.36   47.66 2620.54   48.04 2697.84    46.6 2963.36   45.97
 2993.21   47.91 2999.67   46.47 3158.57   45.83 3184.25   46.89 3839.17   45.84
 3879.53   46.95 3890.97      40 3903.89   46.15 4634.06   45.88 4932.73    48.2
 5150.19   52.05 5522.86   52.52  5757.6   54.13 5809.18   55.74 6090.31   54.43
#Mann= 3 , 0 , 0
       0     .12       0 3879.53     .06       0 3903.89     .12       0
#XS Ineff= 2 , 0
       0    2774      51    4747       0      51
Permanent Ineff=
       F       F
Bank Sta=3879.53,3903.89
XS Rating Curve= 0
Exp/Cntr=.3,.1

Type RM Length L Ch R = 1 ,12404   ,665.98,491,239.23
BEGIN DESCRIPTION:
12404
END DESCRIPTION:
XS GIS Cut Line= 6
     2157939.513      220762.367     2155572.341      218191.939
     2155387.621      217827.404     2155102.357      217526.979
     2154643.377      217094.606     2153425.228      216301.266
#Sta/Elev= 30
       0    59.7  1464.2   57.92 1658.15   54.92 1923.93   55.42 2028.45   52.65
 2060.38   53.72 2294.21    50.6 2333.99    48.6 2369.25   49.44 2400.32   47.75
 2489.85   48.26 2601.09   46.15 2640.97   47.47 2647.32   46.04 3076.06   45.67
 3128.66   47.17 3161.57   45.23 3194.51   46.89 3680.92   45.64 3695.16    42.6
 3706.52    45.8 4932.53   46.71 5363.62   51.19 5568.51   50.99 5703.53   52.58
 5721.34   54.26 5726.95   53.01 6031.17   53.94 6048.26   55.53 6401.59   52.77
#Mann= 3 , 0 , 0
       0     .12       0 3680.92     .06       0 3706.52     .12       0
#XS Ineff= 2 , 0
       0 2641.11   50.84 4881.68       0   51.05
Permanent Ineff=
       F       F
Bank Sta=3680.92,3706.52
XS Rating Curve= 0
Exp/Cntr=.3,.1

Type RM Length L Ch R = 1 ,11913   ,560.2,469.2,359.88
BEGIN DESCRIPTION:
11913
END DESCRIPTION:
XS GIS Cut Line= 4
     2157861.302      219545.419     2157003.906      218752.354
     2154775.856      216905.417     2153509.695      216126.075
#Sta/Elev= 30
       0   59.99  265.03   60.12  293.03   58.36  427.94   58.17  577.53   59.36
  876.97   57.77  969.85   55.57 1265.42   55.33 1344.66   51.47  1543.3   48.33
  1602.4    49.3 1650.75   47.46 1746.82   48.14 1900.55   45.75  2209.2   45.11
 2222.25   46.77 2231.79   45.18 2696.69   45.04 2712.74   42.09 2724.44   45.24
 3524.68    45.3 3784.49   46.64 3843.15   48.81 3930.59   46.83 4023.16   48.84
  4317.4   48.15 4579.64   51.82 4720.85   51.38 5243.04   56.16 5548.75   52.75
#Mann= 3 , 0 , 0
       0     .12       0 2696.69     .06       0 2724.44     .12       0
#XS Ineff= 2 , 0
       0                    3843       0   51.09
Permanent Ineff=
       F       F
Bank Sta=2696.69,2724.44
XS Rating Curve= 0
Exp/Cntr=.3,.1

Type RM Length L Ch R = 1 ,11444   ,414.11,498.74,566.26
BEGIN DESCRIPTION:
11444
END DESCRIPTION:
XS GIS Cut Line= 3
     2158152.244      219051.131     2157135.433      218132.856
     2154359.853      216198.579
#Sta/Elev= 30
       0   57.01  301.41   57.74  627.43   56.28  725.11   54.33  870.16   55.17
  903.24   53.62  926.15   54.65 1162.84   51.87  1218.3   53.18  1236.4   51.65
 1545.47   50.07 1553.89   48.79 1681.47   46.24 1744.74   47.23 1865.85   45.33
 2671.28   46.07 2682.54    42.3 2695.05   45.27 3235.74   45.63 3455.75   48.22
 3495.13   51.97 3559.03   48.12 3597.83   49.01 3621.31   46.97 3730.02    46.5
 4140.02   50.19 4307.94   48.05 4398.42   49.33 4427.11   51.16 4753.17   50.12
#Mann= 3 , 0 , 0
       0     .12       0 2671.28     .06       0 2695.05     .12       0
#XS Ineff= 2 , 0
       0                 3498.29       0   52.53
Permanent Ineff=
       F       F
Bank Sta=2671.28,2695.05
XS Rating Curve= 0
Exp/Cntr=.3,.1

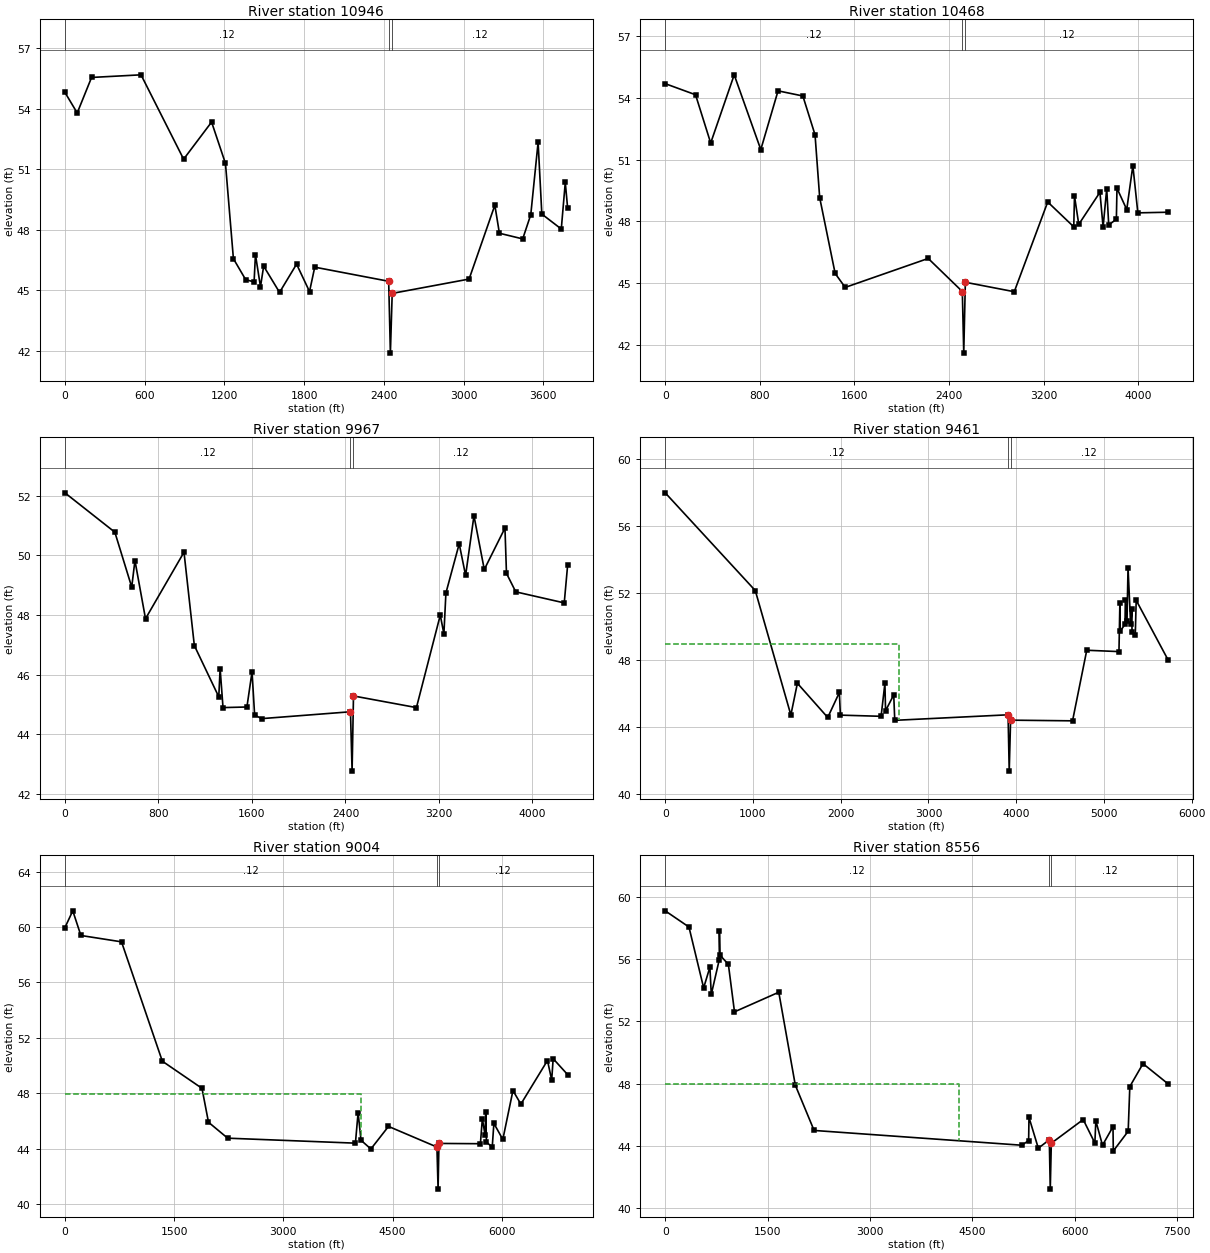
Type RM Length L Ch R = 1 ,10946   ,390.73,477.95,524.88
BEGIN DESCRIPTION:
10946
END DESCRIPTION:
XS GIS Cut Line= 2
     2158247.092      218538.184     2155305.902      216158.493
#Sta/Elev= 30
       0   54.81   92.52   53.79  200.43   55.55  572.68   55.68  893.28    51.5
 1103.74   53.34 1208.08   51.29 1267.93   46.57  1360.2   45.53 1423.56   45.42
 1433.81   46.77 1471.71   45.18  1495.6    46.2 1615.18    44.9 1743.36    46.3
 1840.82   44.94 1879.94   46.15 2436.46   45.45 2449.34   41.89 2462.94   44.85
 3041.68   45.56 3235.48   49.22 3269.74   47.83 3445.15   47.55 3505.85   48.75
 3561.01   52.34 3589.06   48.78 3735.47   48.04 3765.51   50.35 3783.32   49.07
#Mann= 3 , 0 , 0
       0     .12       0 2436.46     .06       0 2462.94     .12       0
Bank Sta=2436.46,2462.94
XS Rating Curve= 0
Exp/Cntr=.3,.1

Type RM Length L Ch R = 1 ,10468   ,564.53,500.97,434.27
BEGIN DESCRIPTION:
10468
END DESCRIPTION:
XS GIS Cut Line= 2
     2158524.895      218315.941     2155354.575      215484.025
#Sta/Elev= 30
       0    54.7  256.39   54.16  384.47   51.81  583.24   55.13   808.1   51.49
  954.07   54.35 1163.89    54.1 1266.82   52.21 1306.17   49.15 1436.85   45.46
 1521.88   44.78 2223.71   46.19 2512.32   44.58 2524.38   41.58 2537.82   45.03
  2951.5   44.57 3234.33   48.94 3454.58   47.73 3460.78   49.23 3496.83   47.85
 3675.93   49.41 3702.66   47.72 3733.27   49.58 3750.27   47.82  3814.9    48.1
 3820.01   49.61 3902.62   48.57 3954.34   50.71 3996.49   48.41 4250.96   48.44
#Mann= 3 , 0 , 0
       0     .12       0 2512.32     .06       0 2537.82     .12       0
Bank Sta=2512.32,2537.82
XS Rating Curve= 0
Exp/Cntr=.3,.1

Type RM Length L Ch R = 1 ,9967    ,585.39,505.9,471.13
BEGIN DESCRIPTION:
9967
END DESCRIPTION:
XS GIS Cut Line= 2
     2158947.157      217915.904     2155625.662      215183.707
#Sta/Elev= 30
       0    52.1  427.11   50.78  571.44   48.94  598.95   49.83  689.37   47.88
 1018.66   50.11 1107.16   46.98 1316.31   45.26 1327.71   46.21 1352.48    44.9
 1556.94   44.92 1600.79    46.1 1622.88   44.65 1682.98   44.53 2442.88   44.76
 2456.72   42.77 2468.68   45.29 3007.17    44.9 3211.22      48 3242.15   47.37
 3259.38   48.74 3373.17   50.39 3427.91   49.33 3499.35   51.33 3587.69   49.53
  3764.6   50.92 3777.52    49.4 3857.09   48.78 4271.76   48.41 4300.84   49.68
#Mann= 3 , 0 , 0
       0     .12       0 2442.88     .06       0 2468.68     .12       0
Bank Sta=2442.88,2468.68
XS Rating Curve= 0
Exp/Cntr=.3,.1

Type RM Length L Ch R = 1 ,9461    ,371.28,457.08,505.91
BEGIN DESCRIPTION:
9461
END DESCRIPTION:
XS GIS Cut Line= 3
     2159529.962      218934.685     2159312.882      217457.923
     2155953.185      214876.419
#Sta/Elev= 30
       0   57.99  1026.5   52.16 1431.86   44.74 1506.32   46.63 1852.37   44.59
 1984.69   46.08  1996.5   44.73 2460.44   44.66 2503.77   46.63 2511.26   44.99
 2604.52   45.94 2616.06   44.42 3907.57   44.75 3920.61   41.39 3936.22   44.43
 4642.35   44.39 4804.27    48.6 5171.39   48.52 5181.84   51.42 5186.36   49.74
 5240.48   50.15 5244.01    51.6 5263.08   50.32 5274.72   53.53 5304.53   50.14
 5319.43   51.08 5319.84    49.7 5357.22   49.49 5367.79   51.58 5729.58   48.04
#Mann= 3 , 0 , 0
       0     .12       0 3907.57     .06       0 3936.22     .12       0
#XS Ineff= 2 , 0
       0    2667      49               0
Permanent Ineff=
       F       F
Bank Sta=3907.57,3936.22
XS Rating Curve= 0
Exp/Cntr=.3,.1

Type RM Length L Ch R = 1 ,9004    ,525.84,447.5,405.79
BEGIN DESCRIPTION:
9004
END DESCRIPTION:
XS GIS Cut Line= 5
     2160511.427      219502.094      2160574.97      218442.682
     2160277.089      217926.563     2159814.739      217430.544
     2156320.154      214485.576
#Sta/Elev= 30
       0   59.96  107.92   61.17  219.24   59.39  777.31   58.93 1337.98   50.31
 1882.58   48.35 1971.98    45.9 2235.62   44.75 3990.21   44.39 4027.08    46.6
 4066.91    44.6 4202.56   43.97 4444.59    45.6 5109.94   44.11 5125.68   41.07
 5137.56   44.37 5707.05   44.35 5733.78   46.16 5771.73   44.95 5779.65   46.66
 5790.06   44.47 5869.45    44.1 5892.05   45.82 6014.98   44.66 6154.02   48.19
 6262.77   47.21 6628.31   50.36 6686.26   48.95  6706.4   50.49 6905.32   49.34
#Mann= 3 , 0 , 0
       0     .12       0 5109.94     .06       0 5137.56     .12       0
#XS Ineff= 2 , 0
       0 4061.03   47.97               0
Permanent Ineff=
       F       F
Bank Sta=5109.94,5137.56
XS Rating Curve= 0
Exp/Cntr=.3,.1

Type RM Length L Ch R = 1 ,8556    ,499.24,521.29,530
BEGIN DESCRIPTION:
8556
END DESCRIPTION:
XS GIS Cut Line= 4
      2161132.51      219578.771     2161111.967      218119.205
     2159754.572      216694.978     2156653.248      214268.157
#Sta/Elev= 30
       0    59.1  347.71   58.06   562.9   54.15  654.51   55.48  674.64   53.73
  792.37   55.97  793.73   57.81  801.01   56.26  925.24   55.66 1014.79   52.61
  1663.6   53.87 1905.78    47.9 2181.03   44.99 5225.27   44.04 5324.29   44.34
 5329.39   45.83 5465.99   43.85 5626.98   44.39 5641.22   41.22 5656.44   44.17
 6123.61   45.69 6294.74   44.18 6308.61   45.61 6406.45   44.04  6560.2   45.23
 6564.74   43.67 6782.63   44.94 6806.67   47.81 6999.83   49.28 7365.16   47.99
#Mann= 3 , 0 , 0
       0     .12       0 5626.98     .06       0 5656.44     .12       0
#XS Ineff= 2 , 0
       0    4303      48               0
Permanent Ineff=
       F       F
Bank Sta=5626.98,5656.44
XS Rating Curve= 0
Exp/Cntr=.3,.1

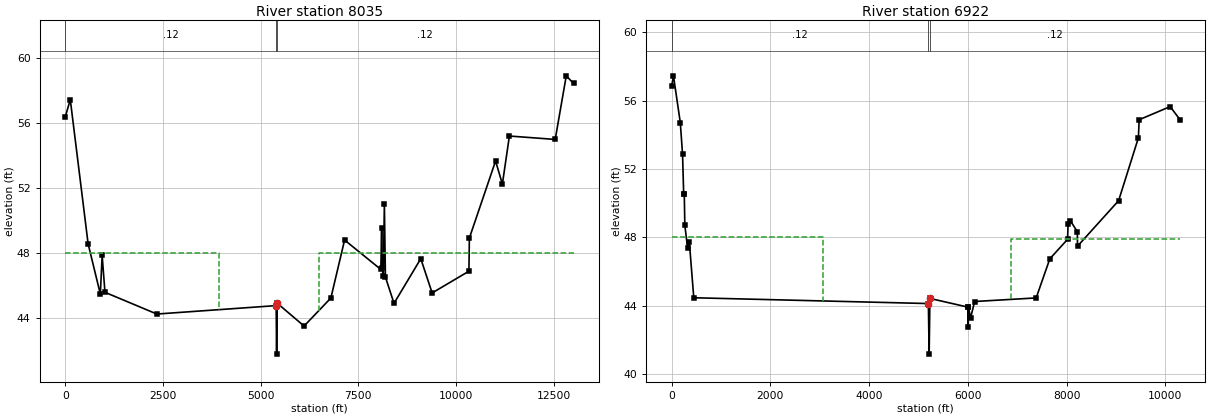
Type RM Length L Ch R = 1 ,8035    ,792.37,1112.85,1799.4
BEGIN DESCRIPTION:
8035
END DESCRIPTION:
XS GIS Cut Line= 6
     2162536.377      218271.492     2161805.087      217782.555
     2157448.613      214252.575     2156455.382      214222.202
     2154361.321      215409.856     2151625.703      213907.225
#Sta/Elev= 30
       0   56.39   130.1   57.46   586.2   48.58  899.27   45.48  945.43   47.86
  1017.4   45.59 2345.93   44.25  5399.4   44.77 5411.22   41.78 5425.42   44.92
 6113.92   43.51 6799.97   45.24  7150.6   48.81  8078.8      47 8099.45   49.56
 8109.79   47.07 8142.12   46.62 8168.94   51.01 8195.72   46.53 8415.95   44.91
 9100.75   47.66 9391.93   45.5510333.06   46.89 10344.3   48.9311015.09   53.68
11189.58   52.2611368.91   55.2212541.83   55.0112824.32   58.93 13010.6   58.46
#Mann= 3 , 0 , 0
       0     .12       0  5399.4     .06       0 5425.42     .12       0
#XS Ineff= 2 , 0
       0    3933      48    6492       0      48
Permanent Ineff=
       F       F
Bank Sta=5399.4,5425.42
XS Rating Curve= 0
Exp/Cntr=.3,.1

Type RM Length L Ch R = 1 ,6922    ,7067.99,6921.75,6304.42
BEGIN DESCRIPTION:
6922
END DESCRIPTION:
XS GIS Cut Line= 5
      2163125.32      217649.213     2160892.724      216047.865
     2160120.009      215256.379     2159106.276      214173.827
     2157805.767      209386.238
#Sta/Elev= 30
       0   56.85   36.21   57.45  174.94   54.71  220.48   52.85  243.29   50.52
  255.72   50.51  266.29   48.71   324.2   47.35     357   47.75  447.65   44.46
 5200.39   44.12    5216   41.16 5231.29   44.42 6003.65   43.91 6007.71   42.76
 6012.33   43.93 6054.88   43.27 6137.21   44.24 7383.86   44.45 7660.91   46.74
 8020.13   47.88 8030.58   48.79 8078.07   48.96 8217.46   48.33 8222.08   47.48
 9053.73   50.14 9454.91   53.82 9470.59   54.8810099.06   55.6510297.81   54.88
#Mann= 3 , 0 , 0
       0     .12       0 5200.39     .06       0 5231.29     .12       0
#XS Ineff= 2 , 0
       0 3071.67   47.99 6866.89       0   47.92
Permanent Ineff=
       F       F
Bank Sta=5200.39,5231.29
XS Rating Curve= 0
Exp/Cntr=.3,.1

Chan Stop Cuts=-1